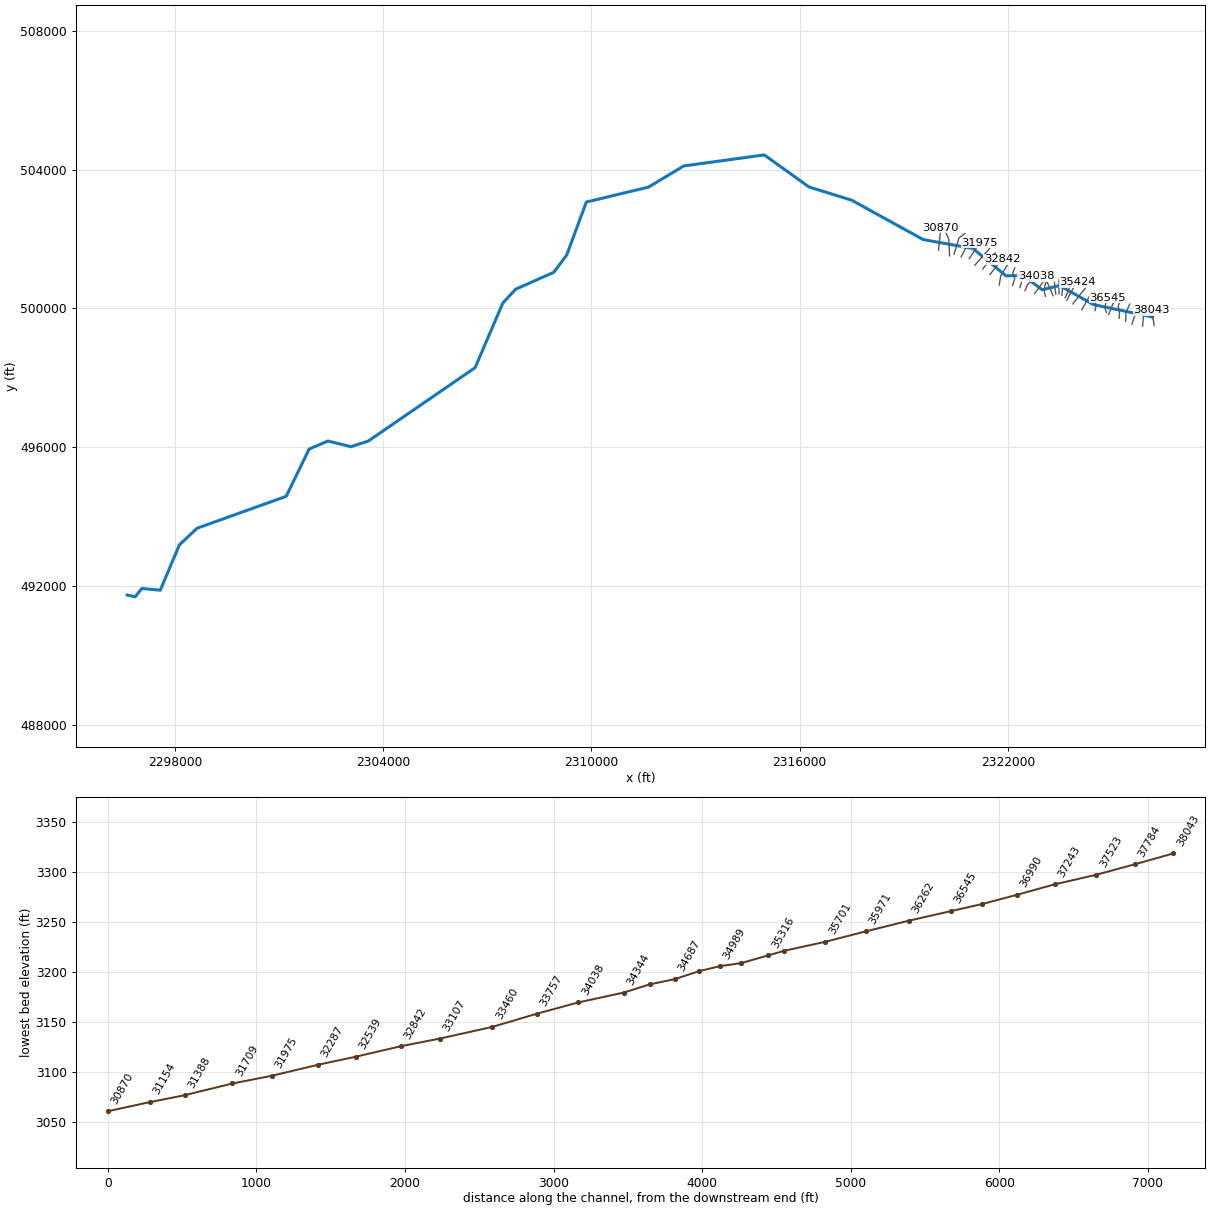
--- GALFRDRN.prj (project) ---

Proj Title=GALFRDRN
Current Plan=p01
Default Exp/Contr=0,0
English Units
Geom File=g01
Flow File=f01
Plan File=p01
Background Map Layer=Inundation Boundary (01pct Value_0)
BEGIN DESCRIPTION:
----------MODEL BY WOOD PLC 2021----------
Stream Name: Galford Run
Flood Zone: Enhanced Approximate
Pocahontas County, WV
HEC-RAS Version: RAS 6.1
Vertical Datum: NAVD88
Projection: NAD 1983 StatePlane West Virginia S FIPS 4702 (US Feet)
Terrain: 1-meter LIDAR (FEMA Region III 3DEP collected 2016-2018)
Land Use: 2019 NLCD
Hydrologic Method:
WV SIR2010-5033 regression equations
Model Notes:
normal depth tie in to Greenbrier River
END DESCRIPTION:
DSS Export Rating Curves= 0
DSS Export Rating Curve Sorted= 0
DSS Export Volume Flow Curves= 0
DXF OffsetX= 0
DXF OffsetY= 0
DXF ScaleX= 0
DXF ScaleY= 0

--- GALFRDRN.p01 (plan) ---

Plan Title=Floodplain
Program Version=6.10
Short Identifier=Floodplain
Geom File=g01
Flow File=f01
Subcritical Flow
K Sum by GR= 0
Std Step Tol= 0.01
Critical Tol= 0.01
Num of Std Step Trials= 20
Max Error Tol= 0.3
Flow Tol Ratio= 0.001
Split Flow NTrial= 30
Split Flow Tol= 0.02
Split Flow Ratio= 0.02
Log Output Level= 0
Friction Slope Method= 1
Unsteady Friction Slope Method= 2
Unsteady Bridges Friction Slope Method= 1
Parabolic Critical Depth
Global Vel Dist= 0 , 0 , 0
Global Log Level= 0
CheckData=True
Encroach Param=-1 ,0,0, 0
Mapping Interval=1HOUR
Computation Time Step Use Courant=        0
Computation Time Step Use Time Series=    0
Computation Time Step Count To Double=0
Computation Time Step Max Doubling=0
Computation Time Step Max Halving=0
Computation Time Step Residence Courant=0
Run HTab= 0
Run UNet= 0
Run Sediment= 0
Run PostProcess= 0
Run WQNet= 0
Run RASMapper=-1
UNET Theta= 0
UNET Theta Warmup= 0
UNET ZTol= 0
UNET ZSATol= 0
UNET MxIter= 0
UNET Max Iter WO Improvement= 0
UNET MaxInSteps= 0
UNET DtIC= 0
UNET DtMin= 0
UNET MaxCRTS= 0
UNET WFStab= 0
UNET SFStab= 0
UNET WFX= 1
UNET SFX= 1
UNET Gravity=32.174
UNET 1D Methodology=Finite Difference
UNET DSS MLevel= 1
UNET Pardiso=0
UNET DZMax Abort= 0
UNET Use Existing IB Tables= 0
UNET Froude Reduction=False
UNET Froude Limit= 0
UNET Froude Power= 0
UNET D1 Cores= 0
UNET WindReference=Eulerian
UNET WindDragFormulation=Hsu (1988)
UNET D2 Coriolis=0
UNET D2 Cores= 0
UNET D2 Theta= 1
UNET D2 Theta Warmup= 1
UNET D2 Z Tol= 0.01
UNET D2 Volume Tol= 0.01
UNET D2 Max Iterations= 20
UNET D2 Equation= 0
UNET D2 RampUpFraction=0.1
UNET D2 TimeSlices= 1
UNET D2 Turbulence Formulation=Non-Conservative (original)
UNET D2 Eddy Viscosity=0.3
UNET D2 Transverse Eddy Viscosity=0.1
UNET D2 Smagorinsky Mixing=0
UNET D2 BCVolumeCheck=0
UNET D2 Cores=0
UNET D2 SolverType=PARDISO (Direct)
UNET D2 Minimum Iterations= 2147483647
UNET D2 Maximum Iterations= 2147483647
UNET D2 Restart Number= 10
UNET D2 Relaxation Coeff=1.3
UNET D2 SOR Precondition Iterations= 10
UNET D2 ILUT Maximum Fill= 8
UNET D2 ILUT Tolerance=1E-08
UNET D1D2 MaxIter= 0
UNET D1D2 ZTol=0.01
UNET D1D2 QTol=0.1
UNET D1D2 MinQTol=1
Write IC File= 0
Write IC File at Fixed DateTime=0
Write IC File at Sim End=0
Echo Input=False
Echo Parameters=False
Echo Output=False
Write Detailed= 0
HDF Write Warmup=0
HDF Write Time Slices=0
HDF Flush=0
HDF Compression= 1
HDF Chunk Size= 1
HDF Spatial Parts= 1
HDF Use Max Rows=0
HDF Fixed Rows= 1
Calibration Method= 0
Calibration Iterations= 20
Calibration Max Change=0.05
Calibration Tolerance=0.2
Calibration Maximum=1.5
Calibration Minimum=0.5
Calibration Optimization Method= 1
WQ AD Non Conservative
WQ ULTIMATE=-1
WQ Max Comp Step=1HOUR
WQ Output Interval=15MIN
WQ Output Selected Increments= 0
WQ Output face flow=0
WQ Output face velocity=0
WQ Output face area=0
WQ Output face dispersion=0
WQ Output cell volume=0
WQ Output cell surface area=0
WQ Output cell continuity=0
WQ Output cumulative cell continuity=0
WQ Output face conc=0
WQ Output face dconc_dx=0
WQ Output face courant=0
WQ Output face peclet=0
WQ Output face adv mass=0
WQ Output face disp mass=0
WQ Output cell mass=0
WQ Output cell source sink temp=0
WQ Output nsm pathways=0
WQ Output nsm derived pathways=0
WQ Create Restart=0
WQ Fixed Restart=0
WQ System Summary=0
WQ Write To DSS=0
Sorting and Armoring Iterations= 10
XS Update Threshold= 0.02
Bed Roughness Predictor= 0
Hydraulics Update Threshold= 0.02
Energy Slope Method= 1
Volume Change Method= 1
Sediment Retention Method= 0
Sediment TS Multiplier= 1
Warm Up Method= 0
XS Weighting Method= 0
Number of US Weighted Cross Sections= 1
Number of DS Weighted Cross Sections= 1
Upstream XS Weight=0
Main XS Weight=1
Downstream XS Weight=0
Number of DS XS's Weighted with US Boundary= 1
Upstream Boundary Weight= 1
Weight of XSs Associated with US Boundary= 0
Number of US XS's Weighted with DS Boundary= 1
Downstream Boundary Weight= 0.5
Weight of XSs Associated with DS Boundary= 0.5
Percentile Method= 0
Sediment Output Level= 3
Mass or Volume Output= 0
Output Increment Type= 1
Profile and TS Output Increment= 1
Transport Output Increment 1
XS Output Flag= 0
XS Output Increment= 10
Read HDF5 Sediment Hotstart= 0
Sediment Hotstart Type= 0
Write Gradation File= 0
Read Gradation Hotstart= 0
Write HDF5 File= 1
Write Binary Output= 1
Write DSS Sediment File= 0
DSS Sediment Output Type= 1
SV Curve= 0
Specific Gage Flag= 0
Subcell Erosion Methods= 0
Subcell Deposition Methods= 0
Advection Scheme= 1
Matrix Solver= 0
Implicit Weighting Factor= 1
Maximum Outer Loop Convergence Iterations= 5
Convergence Maximum Absolute= 0.001
Convergence RMSE= 0.0001
Grain Fractions Max Abs Error= 0.001
Max Subgrid Regions= 1
Max Subgrid Length Scale= 3.402823E+38
Initial Layer Thickness= 3.402823E+38
Min Layer Thickness= 3.402823E+38
Max Layer Thickness= 3.402823E+38
Number of Layers= 5

--- GALFRDRN.f01 (steady flow) ---

Flow Title=Flow
Program Version=6.10
Number of Profiles= 6
Profile Names=01pct,10pct,04pct,02pct,0_2pct,01plus
River Rch & RM=GALFRDSITLNGTN,Main            ,38043
     642     341     452     544     895     950
River Rch & RM=GALFRDSITLNGTN,Main            ,34519
     736     393     520     624    1020    1090
River Rch & RM=GALFRDSITLNGTN,Main            ,30512
    1290     701     918    1100    1770    1900
River Rch & RM=GALFRDSITLNGTN,Main            ,28806
    1440     786    1030    1230    1970    2120
River Rch & RM=GALFRDSITLNGTN,Main            ,24553
    1630     895    1170    1390    2230    2410
River Rch & RM=GALFRDSITLNGTN,Main            ,16945
    2420    1350    1750    2070    3290    3570
River Rch & RM=GALFRDSITLNGTN,Main            ,11530
    2840    1600    2060    2440    3850    4210
River Rch & RM=GALFRDSITLNGTN,Main            ,8046
    3160    1780    2300    2710    4270    4670
River Rch & RM=GALFRDSITLNGTN,Main            ,0
    4900    2810    3590    4220    6570    7240
Boundary for River Rch & Prof#=GALFRDSITLNGTN,Main            , 1
Up Type= 0
Dn Type= 1
Dn Known WS=2523.6
Boundary for River Rch & Prof#=GALFRDSITLNGTN,Main            , 2
Up Type= 0
Dn Type= 1
Dn Known WS=2521.7
Boundary for River Rch & Prof#=GALFRDSITLNGTN,Main            , 3
Up Type= 0
Dn Type= 1
Dn Known WS=2522.5
Boundary for River Rch & Prof#=GALFRDSITLNGTN,Main            , 4
Up Type= 0
Dn Type= 1
Dn Known WS=2523.1
Boundary for River Rch & Prof#=GALFRDSITLNGTN,Main            , 5
Up Type= 0
Dn Type= 1
Dn Known WS=2524.8
Boundary for River Rch & Prof#=GALFRDSITLNGTN,Main            , 6
Up Type= 0
Dn Type= 1
Dn Known WS=2525.3
DSS Import GetInterval= 0
DSS Import GetPeak= 0
DSS Import FillOption= 0

--- GALFRDRN.g01 (geometry) ---

Geom Title=Geometry
Program Version=6.10

River Reach=GALFRDSITLNGTN  ,Main
Reach XY= 30
     2326170.243      499753.518     2324464.501      500112.672
     2323484.555      500661.048     2322989.614      500538.383
     2322438.894      500950.321     2321943.268      500941.738
     2320993.203      501729.355      2319559.39       501986.47
     2317498.757      503121.865     2316271.923      503501.563
     2314981.106      504426.744     2312663.451      504108.841
     2311642.961      503497.993     2309855.028      503067.881
     2309290.718      501542.182     2308917.142      501041.882
     2307819.582      500555.754     2307450.091      500158.095
     2306650.083      498292.925     2303573.648      496177.902
     2303072.645      496014.959     2302409.914      496179.159
     2301869.741      495946.679     2301207.171      494583.515
     2298640.378      493664.699     2298129.581      493182.776
     2297579.812      491876.491     2297049.336      491928.138
     2296856.768      491687.7742296625.24797946491737.666741308

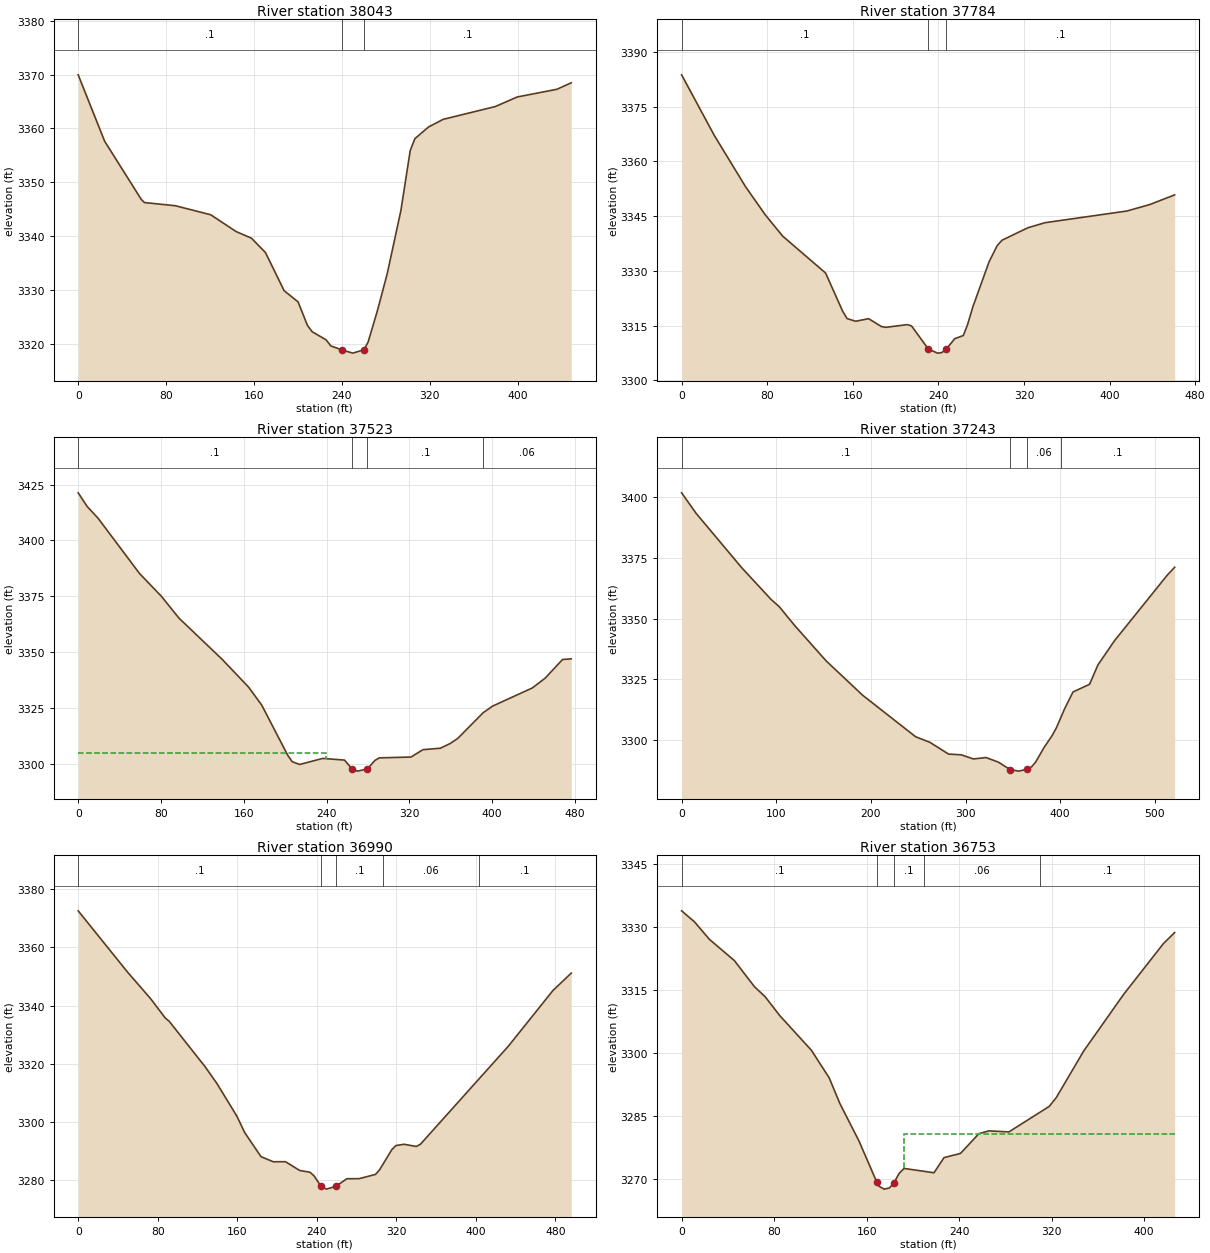
Type RM Length L Ch R = 1 ,38043   ,262.9,258.6,250.4
XS GIS Cut Line= 4
2326211.96953009499509.285964182 2326195.2141266499652.026528803
2326132.64284818499825.6236731752326134.22891897499946.300828907
#Sta/Elev= 30
       0 3369.96    24.1 3357.62    57.4 3346.83    60.3 3346.23    88.5 3345.64
   120.7 3343.96   143.7 3340.85   157.7 3339.62   170.5 3336.95   187.5 3329.86
   200.2 3327.78   208.7 3323.42     213 3322.24   225.7 3320.73     230  3319.6
   240.3 3318.84   250.1 3318.26   260.3  3318.9     264 3320.34   272.5  3326.2
   281.4 3333.05   293.8 3344.75   302.3 3355.89   306.5 3358.09   318.9 3360.26
   332.3 3361.69   379.8 3364.07   399.8 3365.85   435.8 3367.27   448.9 3368.48
#Mann= 3 ,-1,0
       0      .1       0   240.3    .045       0   260.3      .1       0
Bank Sta=240.3,260.3
XS Rating Curve= 0 ,0
Exp/Cntr=0.3,0.1

Type RM Length L Ch R = 1 ,37784   ,265.9,260.8,256
XS GIS Cut Line= 2
2325880.50250939499491.3387606722325929.13467034499949.696877641
#Sta/Elev= 30
       0 3383.76    30.5 3367.17    59.6 3353.16    78.3 3345.33    94.4 3339.55
   134.6  3329.4   150.7 3318.84   154.7 3316.91   162.7 3316.18   174.8 3316.89
   186.8 3314.73   190.9 3314.51     211 3315.26     215 3314.88   230.5 3308.62
   239.2 3307.44   243.2 3307.58   247.2 3308.49   255.3 3311.39   263.3 3312.26
   267.3 3315.25   272.4 3320.26   287.4 3332.46   294.9 3336.87   299.5  3338.4
   323.6 3341.81   339.7 3343.21   416.2 3346.41   437.8  3348.2   460.9 3350.84
#Mann= 3 ,-1,0
       0      .1       0   230.5    .045       0   247.2      .1       0
Bank Sta=230.5,247.2
XS Rating Curve= 0 ,0
Exp/Cntr(USF)=0,0
Exp/Cntr=0.3,0.1

Type RM Length L Ch R = 1 ,37523   ,282.6,280.1,279.1
XS GIS Cut Line= 2
2325574.14584066499544.8789765712325723.68973558499997.158073421
#Sta/Elev= 30
       0 3421.29     8.7 3415.17    19.2 3409.94    59.3 3385.21    80.4 3375.05
    97.2 3365.37   139.3 3346.78   164.6 3334.47   177.3 3326.45   202.5 3303.95
   206.8 3301.12     214 3299.88   236.2 3302.58   257.3 3301.84264.4407    3298
   269.9  3296.9279.40183297.853   286.8 3301.72     291 3302.83   321.6  3303.2
   333.1 3306.49     350 3307.15   359.6 3309.29   366.8 3311.55   391.3 3323.02
   400.5 3325.98   438.8 3334.08   451.1 3338.41     468  3346.8   476.4 3347.09
#Mann= 4 ,-1,0
       0      .1       0264.4407    .045       0279.4018      .1       0
   391.3     .06       0
#XS Ineff= 2 , 0
           239.3    3305
Permanent Ineff=
       F       F
Bank Sta=264.4407,279.4018
XS Rating Curve= 0 ,0
Exp/Cntr=0.3,0.1

Type RM Length L Ch R = 1 ,37243   ,238.5,253.2,269
XS GIS Cut Line= 3
2325394.18089988499629.9404193842325401.47572402499880.396048285
2325512.11389018500127.204265114
#Sta/Elev= 30
       0 3401.75    15.2 3393.38    63.4 3371.01    94.5 3357.94   103.3 3354.88
   119.3 3347.27   152.8 3332.62   191.3 3318.52   247.3 3301.45   262.3 3299.18
   282.1 3294.32   295.3 3294.04   308.4 3292.33   321.6  3292.9   334.7 3291.03
     347 3287.98   356.1 3287.32   365.4  3288.1   369.8 3289.09   374.2  3291.1
   382.9 3296.98   391.7 3302.05   396.1  3305.2   404.8 3313.03   413.6 3319.88
   431.1 3323.03   439.9 3330.97   457.4 3340.93   513.5 3368.05     521 3371.14
#Mann= 4 ,-1,0
       0      .1       0     347    .045       0   365.4     .06       0
  400.56      .1       0
Bank Sta=347,365.4
XS Rating Curve= 0 ,0
Exp/Cntr(USF)=0,0
Exp/Cntr=0.3,0.1

Type RM Length L Ch R = 1 ,36990   ,250.9,236.9,223.2
XS GIS Cut Line= 4
2325206.99295976499717.782488068 2325216.6735124499893.769892546
 2325178.2765626 500056.250633382325220.75719598500202.872215361
#Sta/Elev= 30
       0 3372.58    49.9  3351.4    72.7 3342.43    87.5 3335.75    91.4 3334.65
   127.6 3318.99   139.6 3313.17   159.6 3301.95   167.6 3296.24   183.9 3288.03
   196.2 3286.28   208.5  3286.3   222.7  3283.3   233.2 3282.67   237.3  3281.4
  244.063277.938   249.6 3276.87   259.3 3277.84   270.2 3280.45   282.6 3280.47
     299 3281.93   303.1 3283.48   315.4 3290.43   319.5 3291.85   327.7  3292.3
   340.1 3291.54   344.2  3292.3   432.7 3326.05   477.4 3345.14   495.9 3351.16
#Mann= 5 ,-1,0
       0      .1       0  244.06    .045       0   259.3      .1       0
  306.25     .06       0  403.21      .1       0
Bank Sta=244.06,259.3
XS Rating Curve= 0 ,0
Exp/Cntr=0.3,0.1

Type RM Length L Ch R = 1 ,36753   ,205.6,208.1,211.2
XS GIS Cut Line= 2
2324904.21187829499826.9006712382325064.69800943 500222.03697897
#Sta/Elev= 30
       0 3333.86    11.1 3331.25      24 3327.08    45.6 3322.02    63.1 3315.76
    72.3 3313.39    84.9  3308.9   112.3 3300.63   127.7 3294.05   136.8 3288.02
   153.6 3278.93  168.923269.168   170.8 3268.24   175.2 3267.56   179.8 3267.85
   183.8  3269.1   188.1 3271.29   192.4 3272.49   218.3 3271.46     227 3275.07
   241.2 3276.06   257.2 3280.78   265.8 3281.44   283.1 3281.19     318 3287.27
   324.1 3289.37   347.8 3300.46   382.4 3313.97   416.9  3326.1   426.5 3328.69
#Mann= 5 ,-1,0
       0      .1       0  168.92    .045       0   183.8      .1       0
     210     .06       0     310      .1       0
#XS Ineff= 2 , 0
                          192.78         3280.59
Permanent Ineff=
       F       F
Bank Sta=168.92,183.8
XS Rating Curve= 0 ,0
Exp/Cntr(USF)=0,0
Exp/Cntr=0.3,0.1

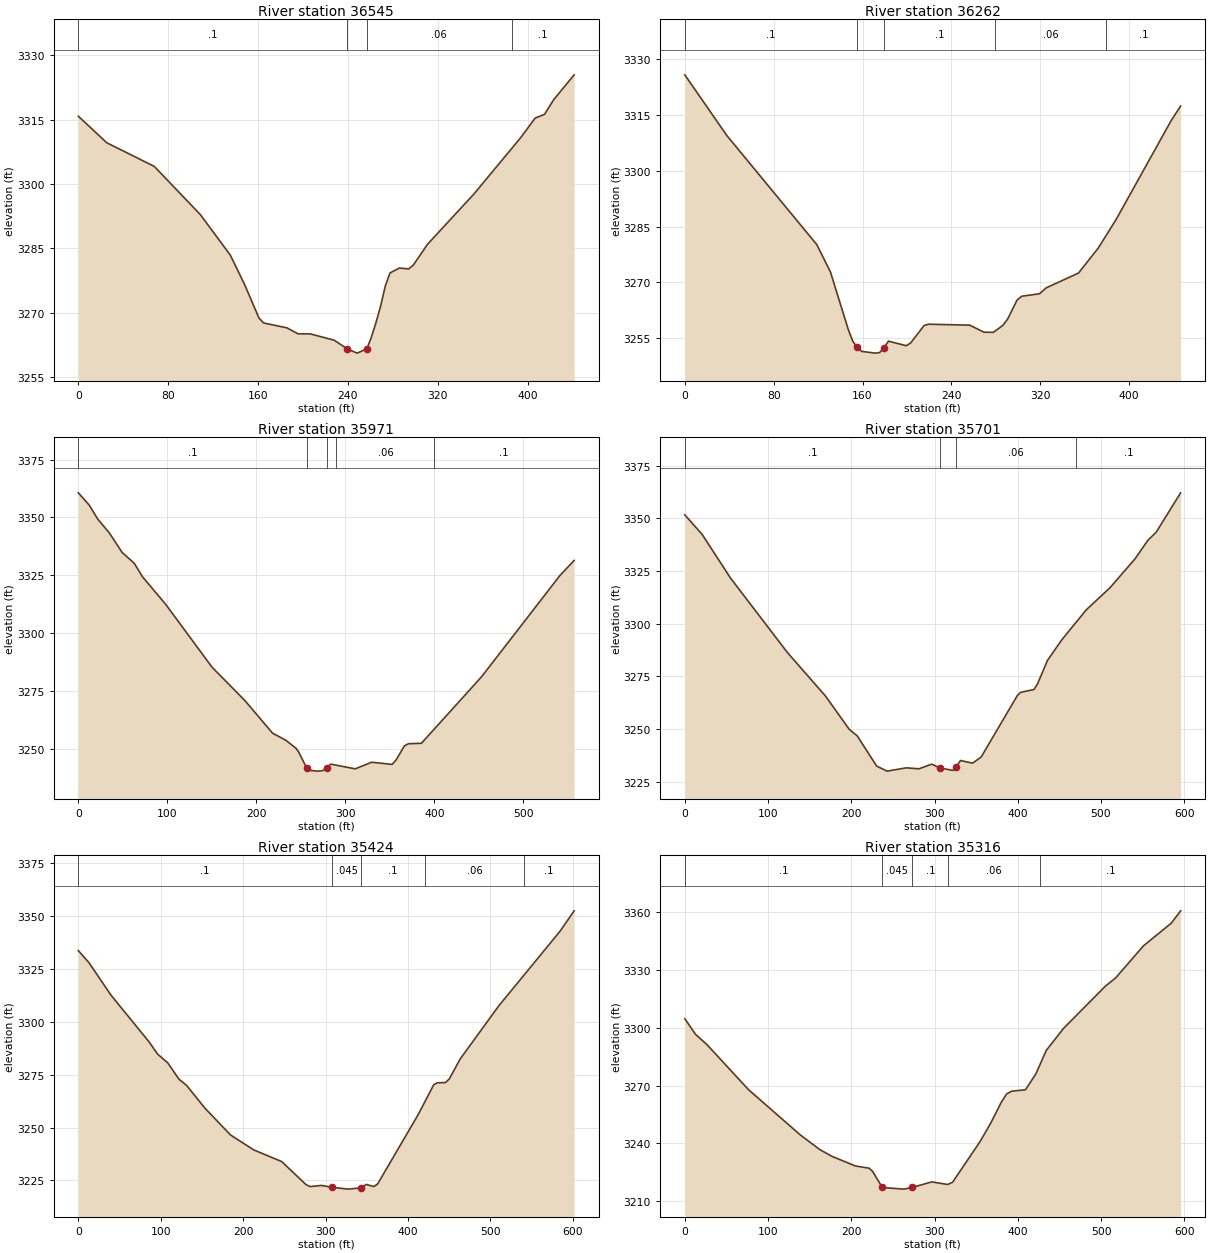
Type RM Length L Ch R = 1 ,36545   ,274.7,283.1,292.2
XS GIS Cut Line= 3
2324838.49440759499885.3069806152324787.49469201500032.371551258
2324867.70995455500306.475999266
#Sta/Elev= 30
       0 3315.81    25.3 3309.62    67.6 3304.11   108.6 3292.87   135.3 3283.41
     148 3276.56   160.7 3268.79   164.8 3267.61   185.7 3266.46   195.5 3265.08
   206.5 3265.05   227.8 3263.58239.36223261.551   248.2 3260.57   256.83261.572
   260.7 3264.19   264.9 3267.67     269 3271.48   273.2 3276.21   277.4 3279.26
   285.7 3280.41     294 3280.21   298.2 3281.11   310.7 3285.92   352.4 3297.76
   394.1 3310.94   406.6 3315.38   414.9 3316.24   423.2  3319.7   441.3 3325.46
#Mann= 4 ,-1,0
       0      .1       0239.3622    .045       0   256.8     .06       0
  385.66      .1       0
Bank Sta=239.3622,256.8
XS Rating Curve= 0 ,0
Exp/Cntr=0.3,0.1

Type RM Length L Ch R = 1 ,36262   ,306.1,290.5,274.1
XS GIS Cut Line= 4
2324511.50717861 499939.970445452324534.60745506500076.140496115
2324526.09682689500177.0522300892324596.61346027500371.580873896
#Sta/Elev= 30
       0 3325.82    37.7 3309.55   118.9 3280.14   131.1 3272.81   147.2 3257.31
   151.2 3254.19   155.2 3252.55   159.2 3251.46   171.3 3250.99   175.3 3251.12
   179.3 3252.46   183.3 3254.21   199.4 3252.98   203.4 3253.76   215.4 3258.41
   219.4 3258.77   256.5 3258.51   269.3 3256.62   277.8 3256.58   286.3 3258.46
   290.6 3260.15   299.1 3265.26   303.3 3266.29   319.2 3266.94   325.4 3268.56
   354.4 3272.52   372.3  3279.3   388.4    3287   437.8 3313.52   446.3 3317.43
#Mann= 5 ,-1,0
       0      .1       0   155.2    .045       0   179.3      .1       0
  279.39     .06       0  379.39      .1       0
Bank Sta=155.2,179.3
XS Rating Curve= 0 ,0
Exp/Cntr(USF)=0,0
Exp/Cntr=0.3,0.1

Type RM Length L Ch R = 1 ,35971   ,274.6,270.8,266.3
XS GIS Cut Line= 2
2324129.30832638499962.4501765912324404.15445752500447.117925472
#Sta/Elev= 30
       0 3360.63    12.3  3355.3    21.7 3349.35    35.3 3343.06    49.1  3334.9
    62.8 3330.19    72.1 3324.35      98  3312.5   150.3 3285.21   187.1 3270.84
   218.3  3256.7     233  3253.7   244.7 3250.14   247.7 3248.53   256.5 3241.69
   260.6 3240.62   268.2 3240.29   274.4 3240.47     279 3241.73   283.6 3243.32
   311.2 3241.28   329.6 3244.14   352.6  3243.2   357.2 3245.18   366.4 3251.21
     371 3252.13   385.6 3252.34   453.1 3281.07   541.3 3324.92   557.2  3331.4
#Mann= 5 ,-1,0
       0      .1       0   256.5    .045       0     279      .1       0
     290     .06       0     400      .1       0
Bank Sta=256.5,279
XS Rating Curve= 0 ,0
Exp/Cntr=0.3,0.1

Type RM Length L Ch R = 1 ,35701   ,269.4,276.9,280.4
XS GIS Cut Line= 2
2323871.99426209500132.067481209 2324240.3828813500600.152030368
#Sta/Elev= 30
       0 3351.72    20.9 3342.38      55 3321.62   123.4 3286.23     169 3265.63
   197.5 3249.83   207.3 3246.63   230.5 3232.33     243 3229.93   266.1 3231.49
   281.4 3231.03   296.6 3233.25   306.8  3231.4   322.1 3230.28   325.6 3231.74
   331.3 3234.98   345.6 3233.71     356 3236.59   399.7 3265.95   403.5 3267.37
   419.6 3268.72   423.9 3271.49   435.7 3282.51     453 3292.35   482.3 3306.55
   510.8 3317.05     541 3330.83   556.2 3339.53   566.4 3343.48   595.7 3362.16
#Mann= 4 ,-1,0
       0      .1       0   306.8    .045       0   325.6     .06       0
     470      .1       0
Bank Sta=306.8,325.6
XS Rating Curve= 0 ,0
Exp/Cntr(USF)=0,0
Exp/Cntr=0.3,0.1

Type RM Length L Ch R = 1 ,35424   ,95.4,107.5,108.7
XS GIS Cut Line= 3
2323697.24290462 500237.730583452323906.73213562500625.662427711
2324002.92729584500754.264798811
#Sta/Elev= 30
       0 3333.58      13 3327.82    39.8 3312.44    85.7 3290.53    96.2 3284.66
   108.5 3280.55   122.1 3272.82   131.2 3269.96   153.9 3259.02   184.8 3246.44
     213  3239.4   246.8 3233.91   276.3 3223.01   281.2 3222.11   294.9 3222.65
   307.6  3221.8   327.4 3220.91   342.9 3221.52   349.4 3223.12   358.5 3222.12
   363.1 3223.36   412.1 3255.98   431.2 3270.23   435.5 3271.13   445.3 3271.23
     450 3272.94   463.3 3282.42   510.2 3307.55   584.5 3342.79   601.5 3352.36
#Mann= 5 ,-1,0
       0      .1       0   307.6    .045       0   342.9      .1       0
     420     .06       0  540.88      .1       0
Bank Sta=307.6,342.9
XS Rating Curve= 0 ,0
Exp/Cntr=0.3,0.1

Type RM Length L Ch R = 1 ,35316   ,176.6,181.8,191.6
XS GIS Cut Line= 3
2323648.73551546500313.6953008192323730.56861242500470.087441668
2323848.77197469500871.978873384
#Sta/Elev= 30
       0  3304.6      13 3296.46    26.5 3291.24    76.4  3267.9   138.5 3244.48
   162.2  3236.8   176.5 3233.36   204.7 3228.34   221.4 3227.16   225.6 3225.49
  237.16 3217.18   263.1 3216.33   273.2 3217.21   296.5 3220.07   315.6 3218.74
   321.5 3219.85   354.3  3240.8   367.4 3250.51     380  3261.3   386.5 3265.64
   392.4 3267.06   409.1 3267.79   421.6 3276.04   434.1  3288.2   454.9 3299.63
   504.9  3321.4   517.5 3325.79   550.8 3342.35   584.2 3354.11   595.4 3360.48
#Mann= 5 ,-1,0
       0      .1       0  237.16    .045       0   273.2      .1       0
  316.51     .06       0  426.51      .1       0
Bank Sta=237.16,273.2
XS Rating Curve= 0 ,0
Exp/Cntr(USF)=0,0
Exp/Cntr=0.3,0.1

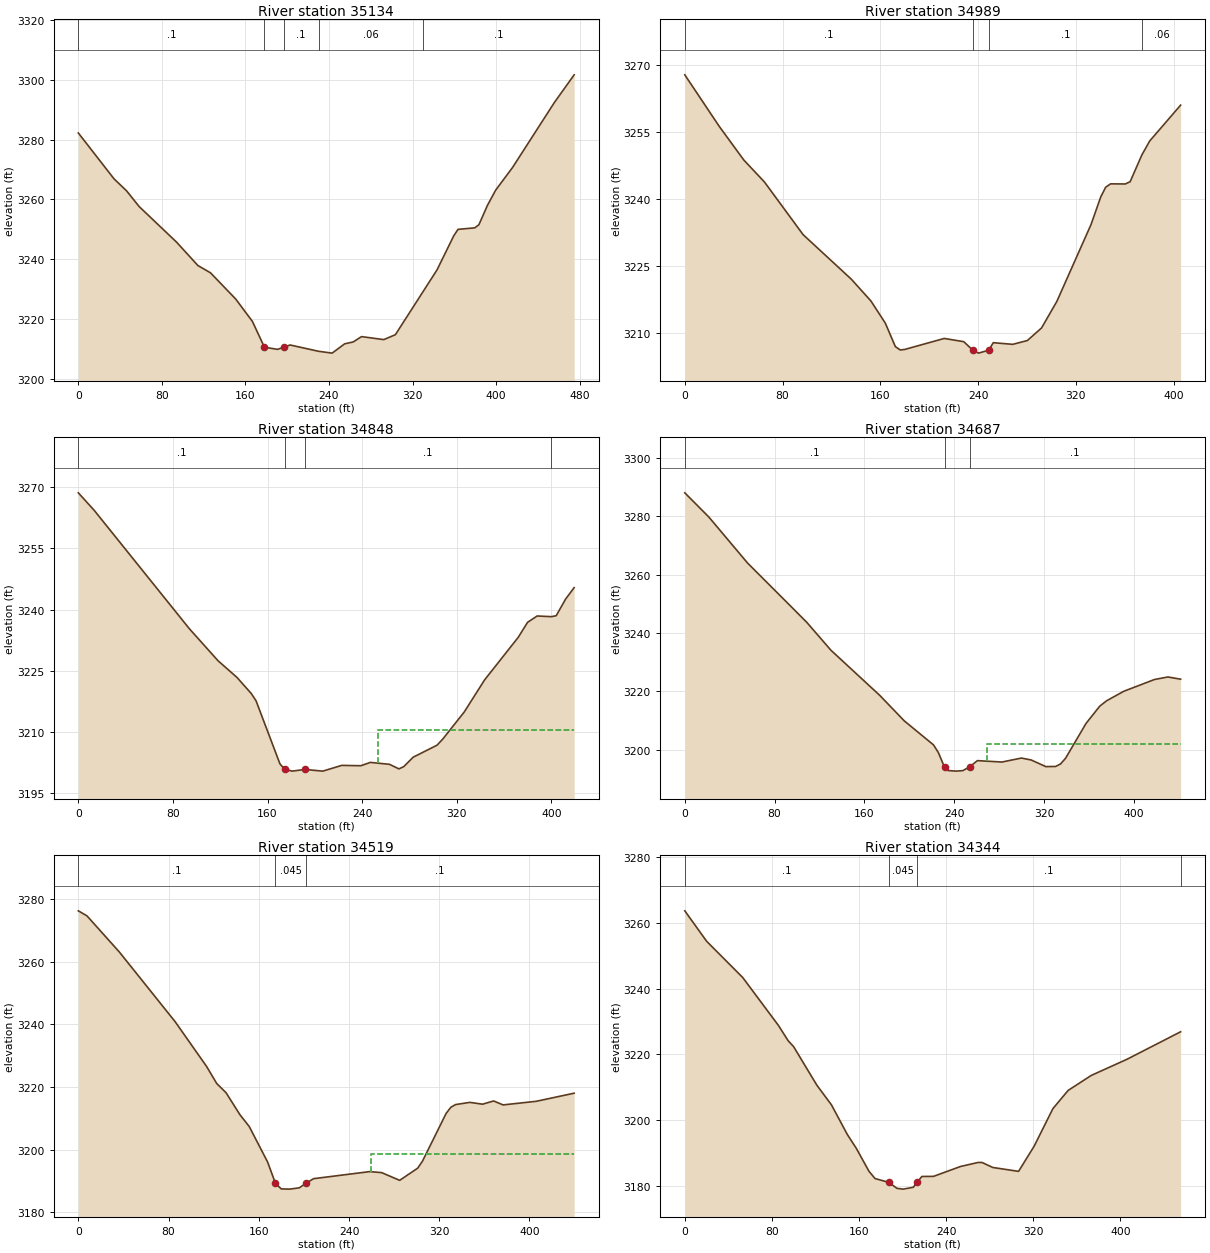
Type RM Length L Ch R = 1 ,35134   ,143.8,145.8,145.4
XS GIS Cut Line= 2
2323555.99133891500379.1617783842323599.63565729500851.975227462
#Sta/Elev= 30
       0 3282.22    34.2 3266.88    46.2 3262.88    58.3  3257.6      94 3245.75
   114.5 3237.91   126.6 3235.46   150.7 3226.71   166.7 3219.22  178.22 3210.59
   190.8 3209.88  196.59 3210.59   202.9 3211.34     230 3209.24     243 3208.62
   255.1 3211.74   263.1 3212.34   271.2 3214.14   292.5 3213.14   303.6 3214.78
   343.5 3236.46   359.5 3247.84   363.6    3250   379.6  3250.5   383.6 3251.55
   391.8 3258.05   399.7 3263.14   415.8 3270.68   455.9 3292.43   474.8 3301.66
#Mann= 5 ,-1,0
       0      .1       0  178.22    .045       0  196.59      .1       0
     230     .06       0     330      .1       0
Bank Sta=178.22,196.59
XS Rating Curve= 0 ,0
Exp/Cntr(USF)=0,0
Exp/Cntr=0.3,0.1

Type RM Length L Ch R = 1 ,34989   ,137.6,141,143.4
XS GIS Cut Line= 3
2323473.68618685500420.8502321082323471.45667747500630.244973018
2323474.30129732500826.523742574
#Sta/Elev= 30
       0 3267.84    28.3 3256.25    48.3 3248.75    65.2 3243.83    96.8 3232.04
   136.3 3222.05   152.3 3217.18   164.1 3212.21   172.3 3206.96   176.3 3206.21
   179.9 3206.32   212.3 3208.79   228.3 3208.06   235.53206.195   240.3  3205.5
   248.73206.154   252.4 3207.84   268.3 3207.47   280.3 3208.32   291.9 3211.14
   304.4 3217.07   332.4 3234.31   340.4 3240.53   344.4 3242.67   348.4 3243.42
   360.4 3243.39   364.4  3243.9     374  3249.9   380.4 3253.02   405.7 3261.05
#Mann= 4 ,-1,0
       0      .1       0   235.5    .045       0   248.7      .1       0
  374.45     .06       0
Bank Sta=235.5,248.7
XS Rating Curve= 0 ,0
Exp/Cntr(USF)=0,0
Exp/Cntr=0.3,0.1

Type RM Length L Ch R = 1 ,34848   ,152.6,160.1,167.6
XS GIS Cut Line= 2
2323379.59555214500411.8950171662323330.49569397500828.334555008
#Sta/Elev= 30
       0  3268.6    13.4 3264.32    93.9  3235.3   118.1 3227.47   134.2 3223.36
   146.3 3219.41   150.3 3217.64   170.5 3202.19   174.43200.895   180.8 3200.41
   191.6 3200.82   206.7 3200.41   222.8 3201.82   238.9 3201.73     247 3202.55
   263.1 3202.08   271.1 3200.96   275.2 3201.51   283.2 3203.83   303.3 3206.76
   308.1 3208.23   326.3 3214.88   343.6 3222.78     372 3233.19   379.9 3236.87
     388 3238.42     400 3238.26   404.1 3238.48   412.1 3242.58   419.3 3245.37
#Mann= 4 ,-1,0
       0      .1       0   174.4    .045       0   191.6      .1       0
     400     .06       0
#XS Ineff= 2 , 0
                          253.46         3210.42
Permanent Ineff=
       F       F
Bank Sta=174.4,191.6
XS Rating Curve= 0 ,0
Exp/Cntr(USF)=0,0
Exp/Cntr=0.3,0.1

Type RM Length L Ch R = 1 ,34687   ,183.8,168.7,153.5
XS GIS Cut Line= 2
2323301.78217493500365.5018537772323127.92219953500771.580397723
#Sta/Elev= 30
       0 3288.08    21.4 3279.79    55.8 3264.05   108.4 3243.77   130.2 3234.08
   173.7 3218.59   195.5 3209.86   221.6  3201.6   225.9 3198.96   230.3 3194.95
   232.2 3193.89   234.6 3192.81   241.7 3192.61   247.8 3192.79   253.9 3194.15
   260.7 3196.21   282.5 3195.73   299.9 3197.09   308.6 3196.43   321.6 3194.16
   330.3 3194.21   334.7 3195.06   339.2 3197.02   357.4 3208.95   369.6 3214.87
   375.7 3216.73     391 3219.99   418.4 3224.04   430.4 3224.91   441.7 3224.15
#Mann= 3 ,-1,0
       0      .1       0   232.2    .045       0   253.9      .1       0
#XS Ineff= 2 , 0
                           269.4         3201.89
Permanent Ineff=
       F       F
Bank Sta=232.2,253.9
XS Rating Curve= 0 ,0
Exp/Cntr(USF)=0,0
Exp/Cntr=0.3,0.1

Type RM Length L Ch R = 1 ,34519   ,188.5,174.9,161.4
XS GIS Cut Line= 4
2323081.35937657500353.7025926642323044.98911126500508.276220247
2323064.99275718500653.7572815022323106.81856229  500781.0532101
#Sta/Elev= 30
       0 3276.22     7.7  3274.6    36.4 3263.06    85.8 3240.84   113.7 3226.54
   122.7 3221.09     131 3218.13   143.3 3211.11   151.5 3207.37   167.8 3196.03
   174.8 3189.18   179.9 3187.43   187.3 3187.36     196 3187.78   201.5 3189.17
   208.6  3190.7   258.3 3192.95   268.9 3192.63   284.9 3190.17   300.9 3194.06
   305.1 3196.27   326.1 3211.54   330.3  3213.5   334.5 3214.36   347.1 3215.06
   358.4 3214.48   368.2 3215.51   376.6 3214.25   406.1 3215.41   439.6 3217.99
#Mann= 3 ,-1,0
       0      .1       0   174.8    .045       0   201.5      .1       0
#XS Ineff= 2 , 0
                          259.15         3198.59
Permanent Ineff=
       F       F
Bank Sta=174.8,201.5
XS Rating Curve= 0 ,0
Exp/Cntr(USF)=0,0
Exp/Cntr=0.3,0.1

Type RM Length L Ch R = 1 ,34344   ,310.4,306.2,300.7
XS GIS Cut Line= 2
2322772.90742459500432.3710750852323040.38430982500800.759694294
#Sta/Elev= 30
       0 3263.58    20.1 3254.33    53.2 3243.35      86 3228.81    94.9 3224.18
    99.9 3222.39   121.3 3210.68   134.7 3204.71   149.3 3195.71   157.6 3191.48
   169.1 3184.59   174.7 3182.37   187.4  3181.2   194.8  3179.4   200.5 3179.16
   209.8 3179.72   213.6 3181.33   217.7    3183   228.4 3183.03   253.1 3186.02
   269.3 3187.25   272.9 3187.25   282.8 3185.73   306.5 3184.55   320.8 3192.19
     338 3203.57     352  3209.1   373.2 3213.64   406.3 3218.59   455.3 3226.89
#Mann= 4 ,-1,0
       0      .1       0   187.4    .045       0   213.6      .1       0
  455.25     .06       0
Bank Sta=187.4,213.6
XS Rating Curve= 0 ,0
Exp/Cntr(USF)=0,0
Exp/Cntr=0.3,0.1

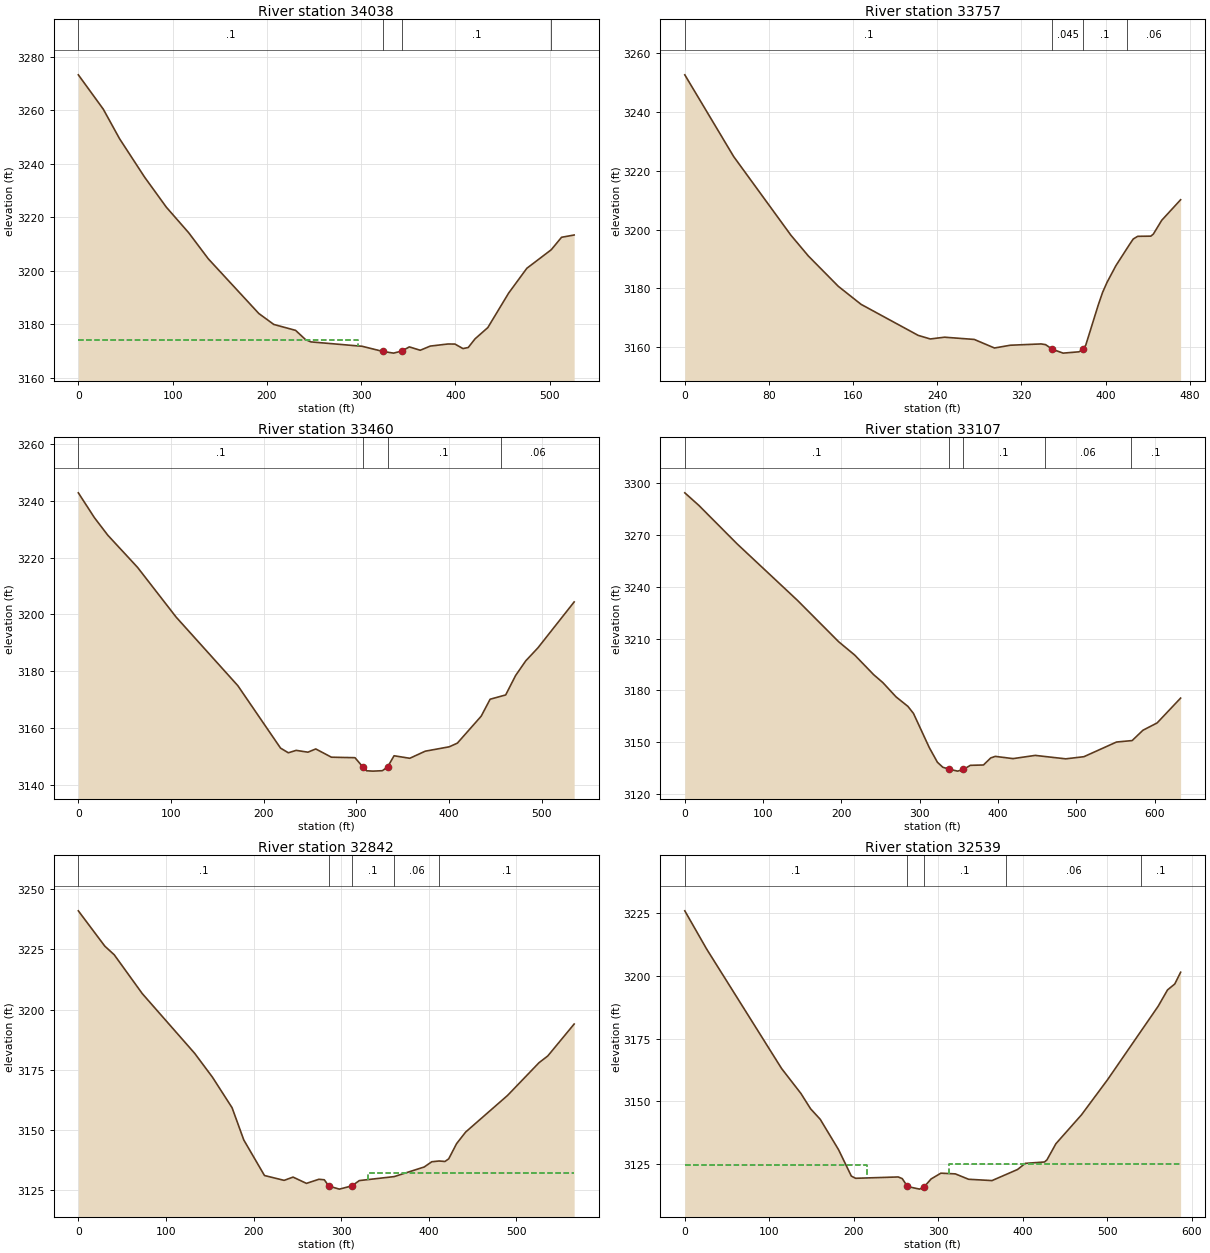
Type RM Length L Ch R = 1 ,34038   ,265.4,280.9,294.6
XS GIS Cut Line= 3
2322493.09665871500512.6620253322322565.00493652500690.121528129
2322806.23278838500922.006396431
#Sta/Elev= 30
       0 3273.29    26.5 3260.44    43.7 3249.44    70.3 3235.06    93.4 3223.82
   117.1 3214.27   137.9 3204.53   191.5 3184.09   207.4    3180   230.5 3177.79
   241.1 3174.33   246.8 3173.48   301.3 3171.83   322.9 3169.93   334.4 3169.28
     343 3170.03   351.2 3171.61   362.8 3170.35   373.4 3171.91   392.1 3172.69
   399.6 3172.67   408.1 3170.98   413.7 3171.38     421 3174.64   434.5 3178.83
   456.6 3191.72   475.9 3200.99   501.8 3207.92   512.7 3212.57   526.1 3213.43
#Mann= 4 ,-1,0
       0      .1       0   322.9    .045       0     343      .1       0
  501.47     .06       0
#XS Ineff= 2 , 0
          296.23 3174.11
Permanent Ineff=
       F       F
Bank Sta=322.9,343
XS Rating Curve= 0 ,0
Exp/Cntr=0.3,0.1

Type RM Length L Ch R = 1 ,33757   ,281.9,297.1,315.2
XS GIS Cut Line= 2
2322346.36532041500600.577510758 2322481.3080615501052.220590812
#Sta/Elev= 30
       0 3252.65    46.5 3224.82   100.8 3198.11   117.5 3190.99     146 3180.66
   167.6 3174.54   221.9 3163.98   233.4 3162.76   246.9 3163.36   275.2  3162.6
   294.4 3159.69   309.6 3160.63   338.8 3161.07     343 3160.83   349.5 3159.24
   359.7 3157.94   374.8 3158.39  378.43 3159.21   381.2 3160.65   393.1 3174.33
   397.2  3178.6   401.4    3182   409.8 3187.67     423 3195.01   426.4  3196.8
   430.6 3197.69   443.1 3197.75   445.5 3198.47   453.4 3203.13   471.4 3210.14
#Mann= 4 ,-1,0
       0      .1       0   349.5    .045       0  378.43      .1       0
     420     .06       0
Bank Sta=349.5,378.43
XS Rating Curve= 0 ,0
Exp/Cntr=0.3,0.1

Type RM Length L Ch R = 1 ,33460   ,375.3,352.4,329
XS GIS Cut Line= 4
2322137.04192014500664.5896436292322197.83212133500863.981503531
2322140.68933221501031.7624588142322199.04792536501169.148313502
#Sta/Elev= 30
       0 3242.82    17.3  3234.1    31.8  3227.9    63.9 3216.58   105.5 3199.08
   172.1 3174.93   218.2 3152.94   226.6  3151.3   235.1 3152.15   247.7 3151.51
   256.2 3152.65   273.1 3149.74   298.5 3149.57   306.9 3146.35   311.1 3144.96
   317.9 3144.84     328 3144.99   333.6 3146.27   340.7 3150.25   357.6 3149.36
   374.3 3151.86   400.3 3153.41     409  3154.7   434.7 3164.19   444.3 3170.15
   461.1 3171.66   471.8 3178.49   482.8 3183.68   495.9 3188.24     535 3204.41
#Mann= 4 ,-1,0
       0      .1       0   306.9    .045       0   333.6      .1       0
   455.7     .06       0
Bank Sta=306.9,333.6
XS Rating Curve= 0 ,0
Exp/Cntr(USF)=0,0
Exp/Cntr=0.3,0.1

Type RM Length L Ch R = 1 ,33107   ,267.7,265.5,264.3
XS GIS Cut Line= 3
2321749.03810133500675.5014470962321797.31884426500950.823678097
2321985.06641717501250.607183096
#Sta/Elev= 30
       0 3294.41    17.9 3287.15    66.7 3264.89   143.8 3232.15   196.6 3208.11
   216.9 3200.47   241.3 3189.03   252.9  3184.5   269.7 3176.25   284.9 3170.72
     292 3166.66   312.3 3146.77   322.6 3138.35   329.5 3135.45   337.7 3134.31
   348.4  3133.2   355.9 3134.18   364.6 3136.55   381.4 3136.76   390.7 3140.84
   396.5 3141.74   419.2 3140.45   447.5 3142.31   486.5 3140.32   509.7 3141.56
   551.3 3150.06   571.3  3150.9   585.1 3156.89   603.2 3161.12   633.2 3175.51
#Mann= 5 ,-1,0
       0      .1       0   337.7    .045       0   355.9      .1       0
  459.52     .06       0  569.52      .1       0
Bank Sta=337.7,355.9
XS Rating Curve= 0 ,0
Exp/Cntr=0.3,0.1

Type RM Length L Ch R = 1 ,32842   ,297.2,302.6,301
XS GIS Cut Line= 2
2321481.72355132500977.051277743 2321833.0909142501420.819746427
#Sta/Elev= 30
       0 3240.99    30.3  3226.3      41 3222.74      73 3206.62   132.8 3181.83
   153.2 3171.87   175.5 3159.25   188.9 3145.84   212.5  3131.1   234.9 3129.09
   245.1 3130.44   260.4 3127.84   274.6 3129.54   280.8 3129.33   285.9 3126.72
     298 3125.45   312.2 3126.79   320.8    3129   360.6 3130.65   394.8 3134.64
   403.5 3136.82   411.9 3137.13   418.5 3136.93   422.8 3138.03   431.8 3144.34
   442.1 3149.13     490 3164.36   525.9 3177.94   535.9 3180.74     566 3193.99
#Mann= 5 ,-1,0
       0      .1       0   285.9    .045       0   312.2      .1       0
   360.6     .06       0   411.9      .1       0
#XS Ineff= 2 , 0
                             331            3132
Permanent Ineff=
       F       F
Bank Sta=285.9,312.2
XS Rating Curve= 0 ,0
Exp/Cntr(USF)=0,0
Exp/Cntr=0.3,0.1

Type RM Length L Ch R = 1 ,32539   ,253.3,252.4,238.7
XS GIS Cut Line= 2
2321275.94395007501136.8125633312321632.74824591501602.246678097
#Sta/Elev= 30
       0 3225.96    25.7  3210.8   114.5 3163.08   137.4 3153.11   148.8 3147.02
   160.2 3142.83   181.9 3130.71     197 3120.19   202.1 3119.31   252.5 3119.84
   257.2 3119.18   263.4 3116.04   277.7 3114.99   283.1  3115.9   291.4 3119.06
   302.9 3121.35     320 3121.07   335.7 3118.92   363.4  3118.4   393.6 3122.82
   402.7 3125.26   425.5 3125.81   428.4 3126.67     439 3133.11   469.2  3144.6
   500.1 3158.64   559.9  3187.9     571 3194.42   579.6  3196.8   586.5 3201.47
#Mann= 5 ,-1,0
       0      .1       0   263.4    .045       0   283.1      .1       0
     380     .06       0     540      .1       0
#XS Ineff= 2 , 0
          215.94 3124.81  312.87         3124.85
Permanent Ineff=
       F       F
Bank Sta=263.4,283.1
XS Rating Curve= 0 ,0
Exp/Cntr=0.3,0.1

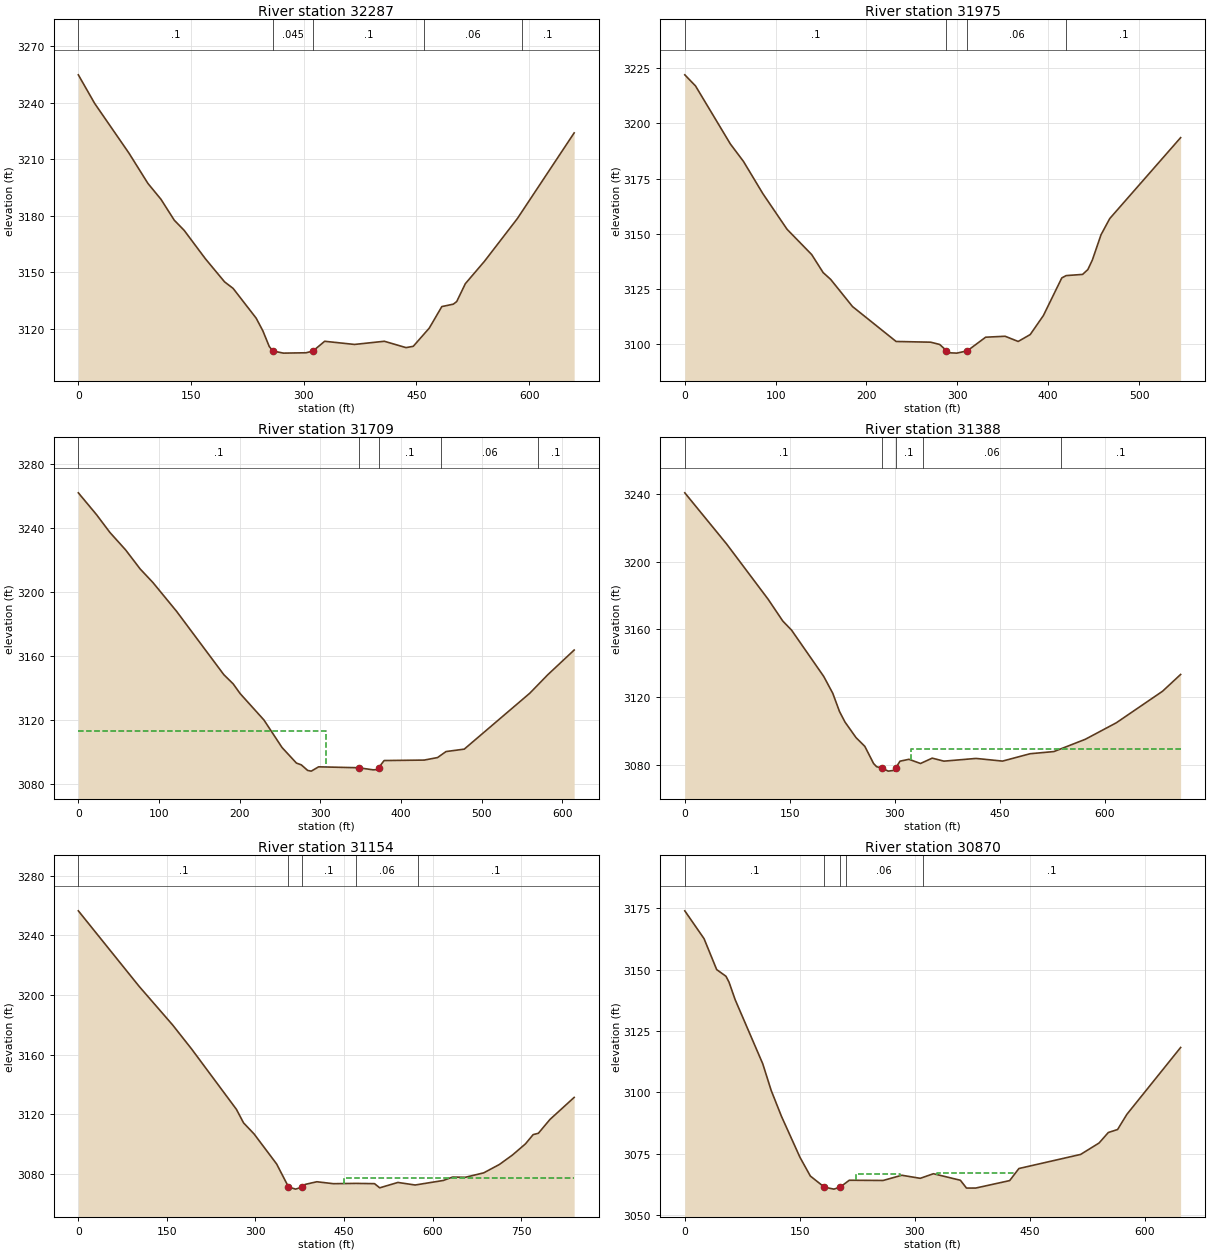
Type RM Length L Ch R = 1 ,32287   ,308.5,311.9,307.7
XS GIS Cut Line= 2
2321047.68151483501246.9597710252321484.15515937501741.792008707
#Sta/Elev= 30
       0 3254.76    21.8 3239.54    67.3 3213.23    92.6 3197.11     110 3188.66
   127.7 3177.56   140.8  3172.2   169.1 3157.09   194.6 3144.84     206 3141.36
   236.6 3125.59   245.6 3118.81   254.1 3110.47     259 3108.14   272.9    3107
   303.1 3107.19   312.3 3108.12   327.8 3113.29   367.5 3111.61   407.2  3113.3
   436.1 3109.92   445.7 3110.62     467 3120.29   483.7 3131.71     499    3133
   503.5 3134.37     515 3143.87   540.4 3155.74   584.3 3178.49   659.8 3223.93
#Mann= 5 ,-1,0
       0      .1       0     259    .045       0   312.3      .1       0
     460     .06       0     590      .1       0
Bank Sta=259,312.3
XS Rating Curve= 0 ,0
Exp/Cntr(USF)=0,0
Exp/Cntr=0.3,0.1

Type RM Length L Ch R = 1 ,31975   ,262.8,265.5,268.2
XS GIS Cut Line= 2
2320886.95251788501435.3557190692321188.71478159 501890.12009961
#Sta/Elev= 30
       0 3222.05    11.8 3217.02    50.2  3190.7    64.6 3182.81    85.9 3168.24
   112.6 3152.05   139.7  3140.6   152.3 3132.44   160.6 3129.35   184.6 3117.06
   232.6 3101.23   270.6 3100.91   280.6 3099.87   287.9 3097.13   290.8 3096.12
   299.4 3095.95     311    3097   331.2 3103.17   352.6 3103.59     367 3101.24
   380.2 3104.35   394.7 3112.95     415 3130.03   419.8 3131.08   437.9 3131.62
   443.7 3133.83   448.6  3138.1   458.2 3149.61   467.8 3156.93   545.8 3193.59
#Mann= 4 ,-1,0
       0      .1       0   287.9    .045       0     311     .06       0
     420      .1       0
Bank Sta=287.9,311
XS Rating Curve= 0 ,0
Exp/Cntr=0.3,0.1

Type RM Length L Ch R = 1 ,31709   ,312.4,321.6,324.6
XS GIS Cut Line= 2
2320651.32940307501485.2573596882320935.82754464502029.937562346
#Sta/Elev= 30
       0 3261.72    22.5 3248.14    39.1 3237.04    58.6 3226.15    76.6 3214.28
    92.5 3205.77   121.8 3187.83   180.4 3148.32   191.9 3142.64   200.5  3136.6
   230.1 3120.08   252.5 3102.93   270.3 3093.26   276.3 3092.16   284.2 3088.68
   288.7 3088.24   297.8 3090.92   347.4 3090.35   347.4 3090.34   365.4 3089.05
     370 3089.17  372.24  3090.4     379 3094.84   428.6 3095.12   445.2  3096.7
   455.7 3100.44   478.3 3101.95   559.5  3136.8   581.6 3148.22   614.5 3163.72
#Mann= 5 ,-1,0
       0      .1       0   347.4    .045       0  372.24      .1       0
     450     .06       0     570      .1       0
#XS Ineff= 2 , 0
          307.53 3113.52
Permanent Ineff=
       F       F
Bank Sta=347.4,372.24
XS Rating Curve= 0 ,0
Exp/Cntr(USF)=0,0
Exp/Cntr=0.3,0.1

Type RM Length L Ch R = 1 ,31388   ,225.2,234,242.9
XS GIS Cut Line= 3
2320445.97849181 501559.424764522320591.70197467502034.242412806
2320761.65622131502159.771657978
#Sta/Elev= 30
       0 3240.48    59.7 3210.34     119 3177.78   139.9 3164.96   152.5 3159.55
   198.4  3132.3   211.3 3122.36   220.9 3111.65   228.7 3105.46   244.5 3096.26
   257.1 3091.08   269.6 3080.98   273.8 3079.15   282.2 3078.12   290.5 3076.51
   298.9 3076.96   300.9 3078.22   307.3 3082.37   320.1 3083.48   336.6 3081.01
   353.3 3084.16     370 3082.39   415.9 3083.99   453.7 3082.42     493 3086.75
   527.1 3088.04   571.9 3095.27   616.1 3104.97   682.2 3123.58     708 3133.46
#Mann= 5 ,-1,0
       0      .1       0   282.2    .045       0   300.9      .1       0
     340     .06       0  536.68      .1       0
#XS Ineff= 2 , 0
                           322.7          3089.4
Permanent Ineff=
       F       F
Bank Sta=282.2,300.9
XS Rating Curve= 0 ,0
Exp/Cntr=0.3,0.1

Type RM Length L Ch R = 1 ,31154   ,287.1,283.2,279.7
XS GIS Cut Line= 3
2320320.21649776501517.6947339752320297.53043215502001.974069798
     2320148.875      502324.176
#Sta/Elev= 30
       0 3256.49   102.8 3205.86   159.7 3179.86   191.7 3163.79   267.8 3123.16
   279.8 3114.12   297.7 3106.65   335.9 3086.48   355.9 3071.12   367.9 3069.63
   378.2 3070.92   383.9 3072.77   403.9 3074.58     432 3073.28     470 3073.48
   501.6  3073.3   510.4  3070.5   541.2 3074.12   570.4  3072.4   617.9 3075.43
   633.7 3077.72   655.7  3077.6   686.6 3080.57     713 3086.16     735 3092.46
   757.1 3099.97   770.3 3106.24   779.1 3107.13   798.7 3116.41   839.7 3131.21
#Mann= 5 ,-1,0
       0      .1       0   355.9    .045       0   378.2      .1       0
     470     .06       0  574.81      .1       0
#XS Ineff= 2 , 0
                          449.81            3077
Permanent Ineff=
       F       F
Bank Sta=355.9,378.2
XS Rating Curve= 0 ,0
Exp/Cntr=0.3,0.1

Type RM Length L Ch R = 1 ,30870   ,365.3,358.6,352.2
XS GIS Cut Line= 2
2320002.09005437501679.7860034942320067.74347165502322.946332079
#Sta/Elev= 30
       0    3174    25.1 3162.65    41.6 3150.02    53.7 3147.31    57.7 3144.89
    65.7 3137.73   101.7 3111.58   112.6 3100.78     126 3090.22   150.2 3073.46
   163.7 3065.84   181.9 3061.32   194.4  3060.5   202.4  3061.3   214.5 3064.12
   258.6 3064.03   282.9 3066.16     307 3064.91   324.2 3066.78   359.3 3064.12
   367.3 3060.93   379.4 3060.94   423.6 3063.98   435.6  3068.9   516.1 3074.65
   540.2 3079.32   552.2 3083.59   564.3 3084.81   576.4 3090.99   646.5 3118.27
#Mann= 5 ,-1,0
       0      .1       0   181.9    .045       0   202.4      .1       0
     210     .06       0     310      .1       0
#XS Ineff= 2 ,-1
  223.19  280.81 3066.56  328.99  429.14 3066.89
Permanent Ineff=
       F       F
Bank Sta=181.9,202.4
XS Rating Curve= 0 ,0
Exp/Cntr(USF)=0,0
Exp/Cntr=0.3,0.1