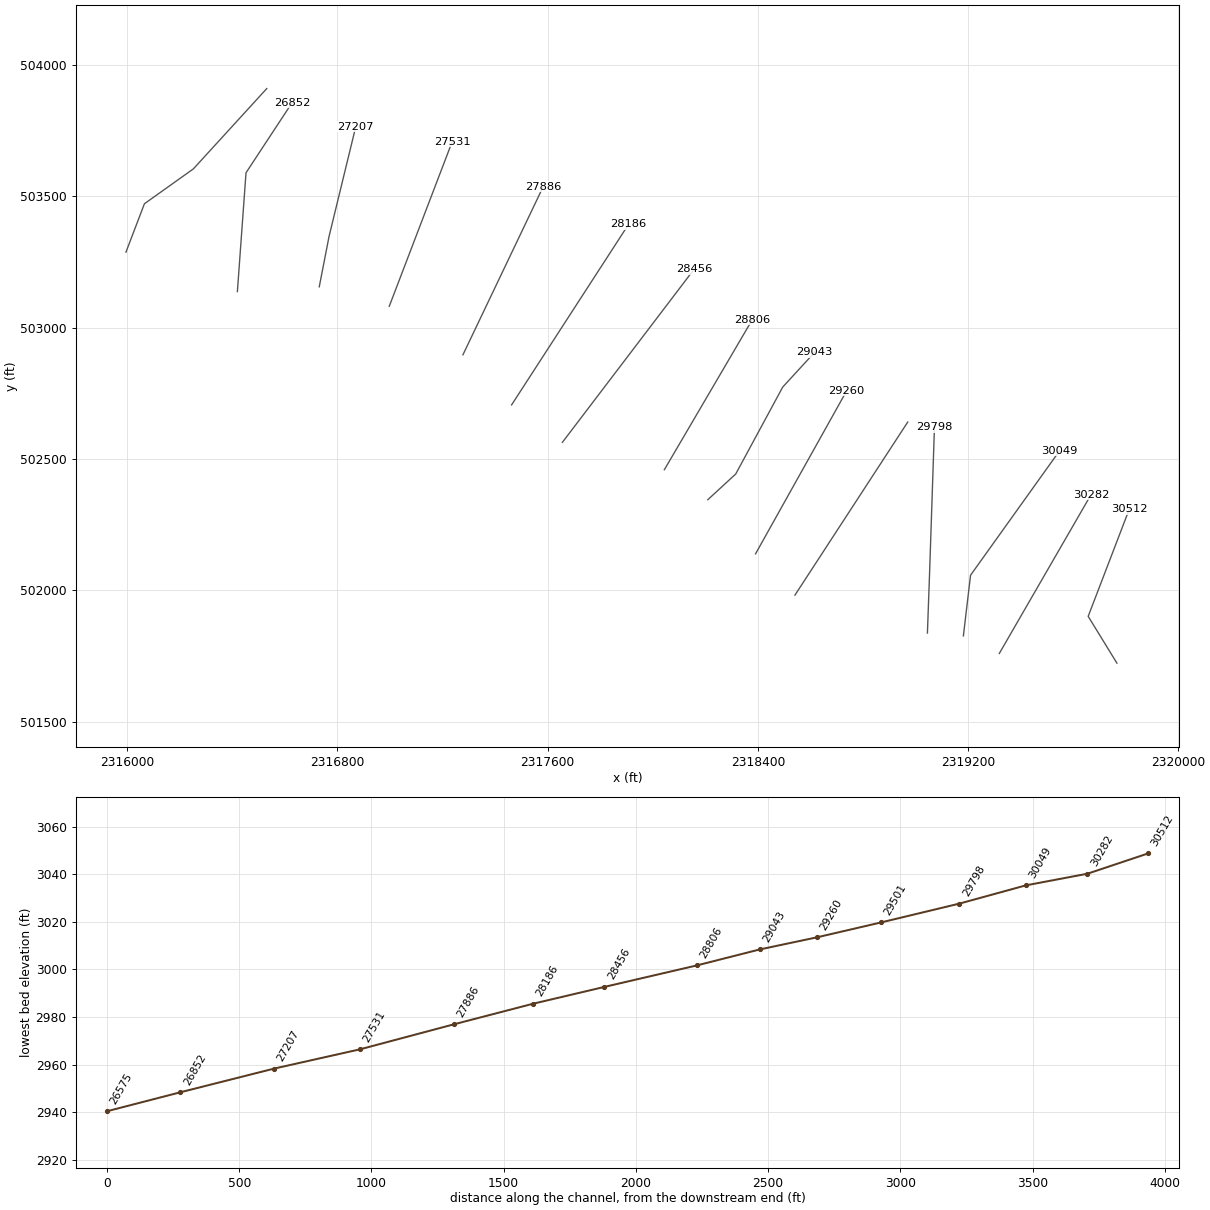
HEC-RAS study GALFRDRN.prj: GALFRDRN

--- GALFRDRN.g01 (geometry) --- (continued)

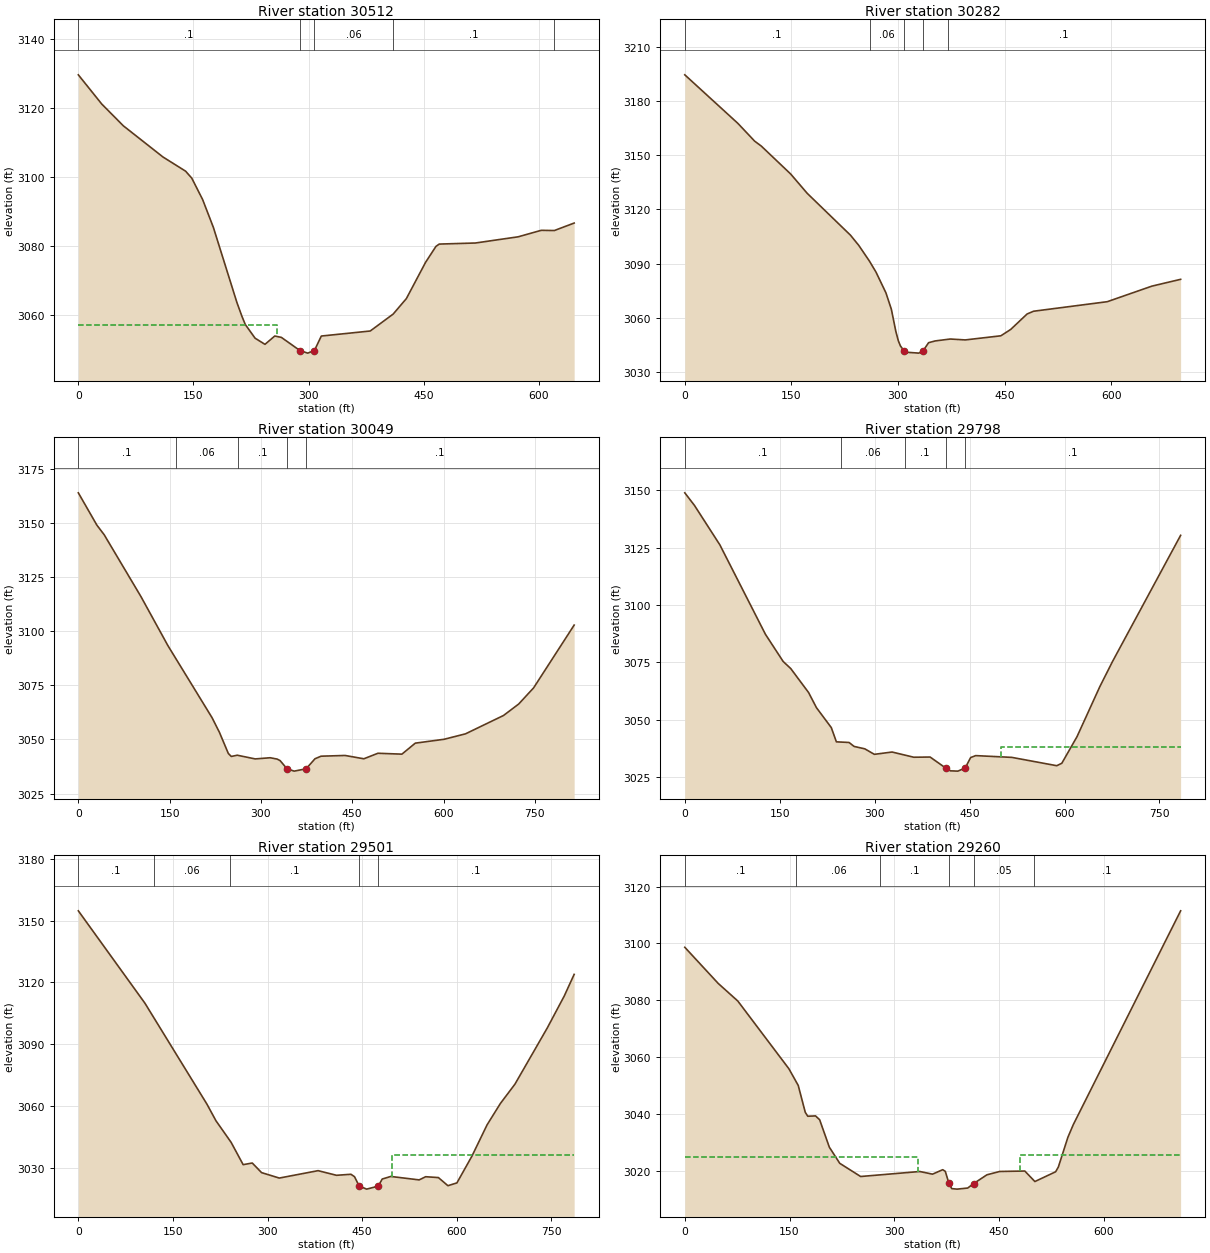
Type RM Length L Ch R = 1 ,30512   ,232.4,229.8,221.8
XS GIS Cut Line= 3
2319766.40723174501723.2254679492319657.08399479501901.393758573
2319813.43518555502309.253602834
#Sta/Elev= 30
       0 3129.56    30.4 3121.11    58.6 3114.77   110.2 3105.72   139.7  3101.6
   147.8 3099.56   161.9 3093.36   175.9 3085.28   206.6 3063.44   213.1 3059.47
   217.4 3057.12   230.2 3053.13   243.1 3051.34   255.9 3053.76   264.5 3053.35
   288.7 3049.53   298.8 3048.79   307.5 3049.54   316.5 3053.75   380.2 3055.21
   410.1 3060.13   427.3 3064.63   452.3 3075.15   465.8 3079.77   470.1 3080.44
   517.2 3080.75   572.9 3082.55   602.9 3084.43     620 3084.37   645.8 3086.54
#Mann= 5 ,-1,0
       0      .1       0   288.7    .045       0   307.5     .06       0
   410.1      .1       0     620     .06       0
#XS Ineff= 2 , 0
           258.5    3057
Permanent Ineff=
       F       F
Bank Sta=288.7,307.5
XS Rating Curve= 0 ,0
Exp/Cntr=0.3,0.1

Type RM Length L Ch R = 1 ,30282   ,235.7,232.9,229.8
XS GIS Cut Line= 2
  2319318.808193501760.0290690642319667.74394783502364.283668888
#Sta/Elev= 30
       0 3194.77    74.7 3167.82    98.3 3157.95   107.6 3155.23   149.1 3139.67
   172.2 3129.01   233.2 3105.72   244.9 3100.04     260 3091.26   269.2 3085.15
   283.1 3073.69   290.7 3064.62   296.9 3052.51   300.5 3047.13   303.4 3044.29
  308.283041.648   312.2 3040.74   329.3 3040.25   335.6 3041.65   343.1 3046.04
   352.4 3047.02   373.7 3048.08   394.7 3047.58   444.8 3049.87   458.7 3053.41
   481.7 3061.97   490.8 3063.51   594.6 3068.81   657.2 3077.43   697.8 3081.23
#Mann= 5 ,-1,0
       0      .1       0     260     .06       0  308.28    .045       0
   335.6     .06       0     370      .1       0
Bank Sta=308.28,335.6
XS Rating Curve= 0 ,0
Exp/Cntr(USF)=0,0
Exp/Cntr=0.3,0.1

Type RM Length L Ch R = 1 ,30049   ,232.7,251,268.5
XS GIS Cut Line= 3
2319182.11273919501827.0107287612319209.38583086502057.901054893
     2319547.996      502531.359
#Sta/Elev= 30
       0 3163.88    30.4 3148.99    42.5 3144.51   102.9 3115.95   147.2  3093.3
   219.7 3060.03   231.8 3053.28   246.4 3043.52   251.3 3042.12   261.1  3042.7
   290.6 3040.99   315.2 3041.53   326.7 3040.91   331.5 3040.21   342.9 3036.41
   354.6 3035.35   374.2 3036.42   388.8 3041.06   398.8 3042.25   438.2 3042.58
   469.1 3041.05   492.2  3043.6   531.6 3043.19   553.6 3048.27     601 3050.06
   636.1 3052.57   698.5 3061.04   723.4 3066.32     748 3073.81   814.6  3102.8
#Mann= 5 ,-1,0
       0      .1       0     160     .06       0   262.5      .1       0
   342.9    .045       0   374.2      .1       0
Bank Sta=342.9,374.2
XS Rating Curve= 0 ,0
Exp/Cntr=0.3,0.1

Type RM Length L Ch R = 1 ,29798   ,312.6,297.4,279.6
XS GIS Cut Line= 3
2319045.25228764501837.8405265872319053.76291581502074.922311226
2319071.99997617502620.818317907
#Sta/Elev= 30
       0 3148.81    15.3 3143.32    55.4 3126.17   127.4 3087.25   155.4 3075.42
   167.4 3072.33   195.6 3061.89     208 3055.31   231.5 3046.62   239.5 3040.44
   259.5 3040.16   267.5 3038.44   284.4 3037.39   299.5    3035   327.5    3036
   361.8 3033.74   387.6 3033.82   412.2 3029.04   419.6 3027.82   431.5 3027.69
   443.1 3029.09   451.6 3033.59   459.6 3034.44   516.7 3033.67   587.7 3030.05
   595.7 3031.12   619.7 3042.69   655.7 3064.43   675.7 3075.35   783.4 3130.31
#Mann= 5 ,-1,0
       0      .1       0  247.23     .06       0  347.23      .1       0
   412.2    .045       0   443.1      .1       0
#XS Ineff= 2 , 0
                          499.06         3038.29
Permanent Ineff=
       F       F
Bank Sta=412.2,443.1
XS Rating Curve= 0 ,0
Exp/Cntr(USF)=0,0
Exp/Cntr=0.3,0.1

Type RM Length L Ch R = 1 ,29501   ,239,240.8,242.7
XS GIS Cut Line= 2
      2318541.07      501982.1482318970.34111029502640.916678097
#Sta/Elev= 30
       0 3154.76   105.6 3109.95   203.9    3061   218.3 3052.89   242.3 3042.44
   261.4 3031.61   275.8 3032.41   290.6 3027.75   318.7 3025.11   380.2  3028.7
   409.4 3026.45   432.3 3026.94     438 3025.77   445.3 3021.25   457.2 3019.74
   475.6 3021.19   481.9 3024.63   495.4 3025.89   540.5 3024.22   550.8 3025.76
     571 3025.34   586.1  3021.4   600.4 3022.77   624.3 3035.81   648.1 3050.87
   669.3 3061.29   692.4 3070.67   743.6 3097.89   770.5 3113.38   786.3 3123.92
#Mann= 5 ,-1,0
       0      .1       0     120     .06       0     240      .1       0
   445.3    .045       0   475.6      .1       0
#XS Ineff= 2 , 0
                          497.13         3036.38
Permanent Ineff=
       F       F
Bank Sta=445.3,475.6
XS Rating Curve= 0 ,0
Exp/Cntr=0.3,0.1

Type RM Length L Ch R = 1 ,29260   ,216.6,217.1,217.1
XS GIS Cut Line= 2
2318391.14972285502139.3599244862318737.65386963502759.419976619
#Sta/Elev= 30
       0 3098.63    47.9  3085.9    75.9 3079.73   149.1 3055.89   162.5 3050.02
   172.6 3040.53   176.2 3039.17   187.3 3039.29   193.2 3037.93   207.1 3028.26
     222  3022.6   251.9 3017.96   336.6 3019.72   354.9 3018.79   369.5 3020.36
   373.2 3019.77   378.3 3015.61   382.4  3013.7   390.1 3013.52   405.3 3013.91
   413.6 3015.44   432.8 3018.56   451.1 3019.73   487.1 3019.89   501.5 3016.19
   531.2 3019.62   535.1 3021.27   548.8 3031.76   556.5  3036.2   710.3 3111.46
#Mann= 6 ,-1,0
       0      .1       0     160     .06       0     280      .1       0
   378.3    .045       0   413.6     .05       0     500      .1       0
#XS Ineff= 2 , 0
          333.52 3024.72     480         3025.48
Permanent Ineff=
       F       F
Bank Sta=378.3,413.6
XS Rating Curve= 0 ,0
Exp/Cntr(USF)=0,0
Exp/Cntr=0.3,0.1

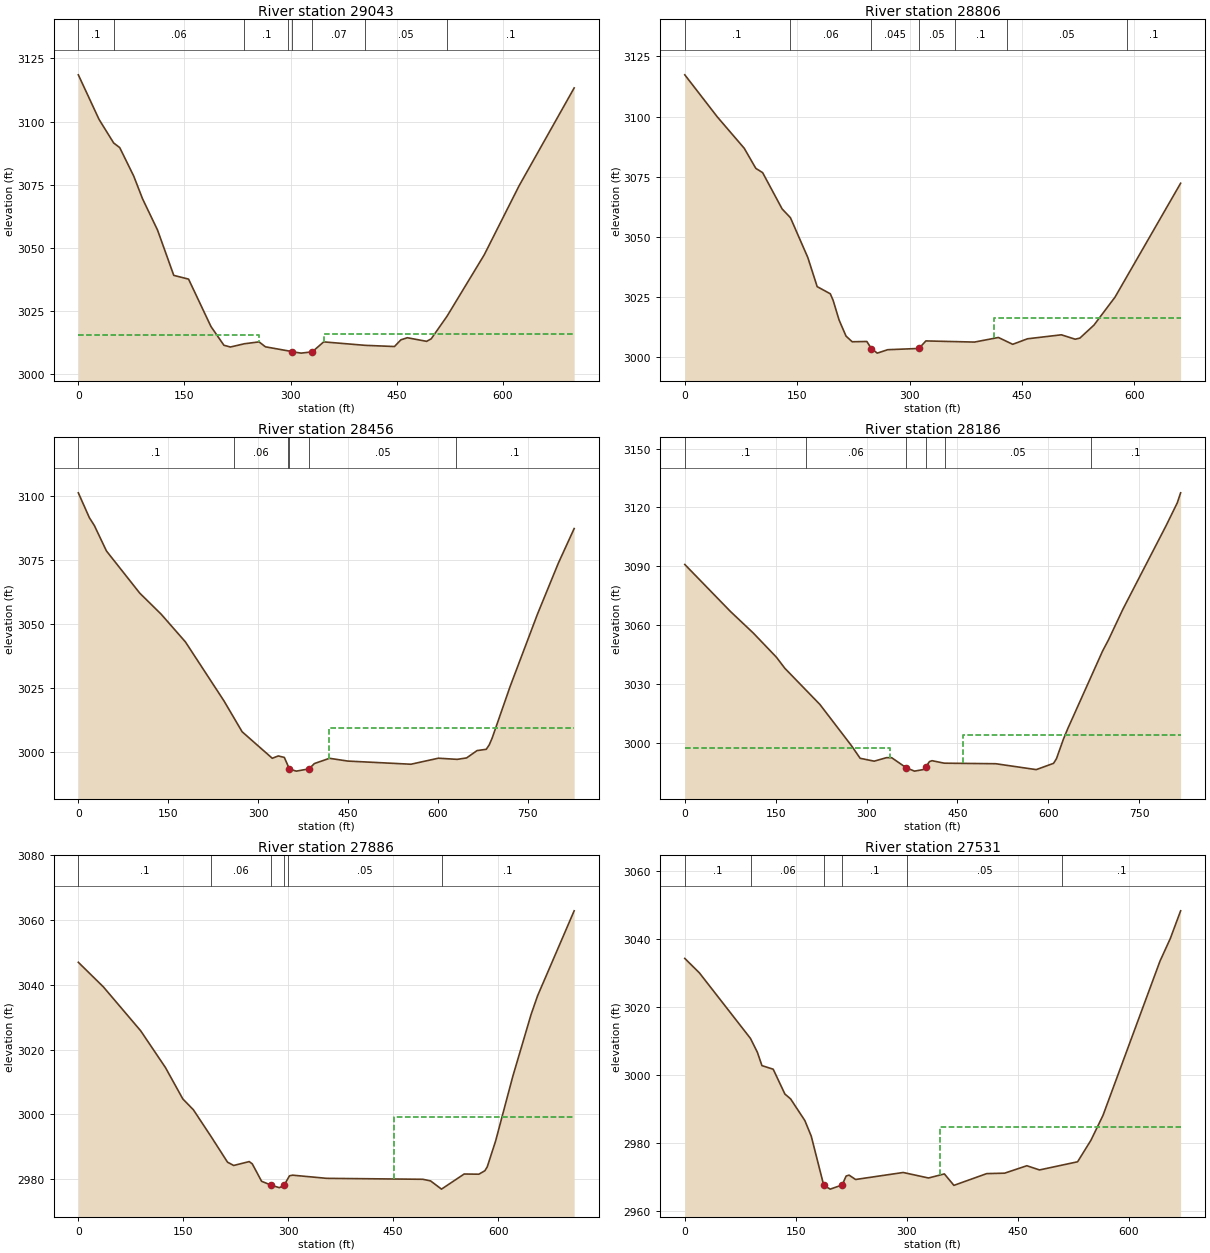
Type RM Length L Ch R = 1 ,29043   ,240.2,236.7,235.7
XS GIS Cut Line= 4
2318209.42910059502345.3038949262318315.76987337502443.310930434
2318494.49306487502774.0096249052318616.38419598502906.782914311
#Sta/Elev= 30
       0 3118.51    29.3 3100.87      50 3091.53    58.5 3089.73    78.3 3078.45
    90.8 3069.45     112 3057.07   134.9 3039.17   155.8 3037.69   187.5 3018.92
   205.8 3011.52   214.9 3010.83   234.8 3012.12   255.5 3012.86   264.4 3010.91
   296.6  3009.3   302.7 3008.93     315 3008.41   330.6 3008.92   346.8 3012.86
   405.5 3011.49   446.8 3011.02   455.9 3013.67     465  3014.5   492.3 3013.07
   498.8 3014.09   521.1    3023   573.7  3047.3     623 3074.63   700.8 3113.32
#Mann= 8 ,-1,0
       0      .1       0      50     .06       0   234.8      .1       0
   296.6     .07       0   302.7    .045       0   330.6     .07       0
   405.5     .05       0   521.1      .1       0
#XS Ineff= 2 , 0
           255.5 3015.76   346.8         3015.95
Permanent Ineff=
       F       F
Bank Sta=302.7,330.6
XS Rating Curve= 0 ,0
Exp/Cntr=0.3,0.1

Type RM Length L Ch R = 1 ,28806   ,349.7,350.5,345.7
XS GIS Cut Line= 2
2318044.07763062502459.5409543262318378.68407151503030.554119751
#Sta/Elev= 30
       0 3117.31    43.6 3099.76    79.3 3086.82    94.8 3078.46   103.9 3076.68
   129.9 3061.62     141 3057.97   164.2 3041.44   176.7 3029.34   194.2 3026.37
     198 3023.64   205.9  3015.5   215.2  3008.8   223.4 3006.44     243 3006.56
  249.04 3003.59   256.9 3001.72   270.8 3003.14   312.5 3003.66   321.8 3006.79
   386.7 3006.31   418.6 3008.22   437.7 3005.38   457.3 3007.67   502.6 3009.33
   521.1  3007.5   527.4 3007.98   546.1 3013.35   574.2 3024.96   661.8 3072.28
#Mann= 7 ,-1,0
       0      .1       0     140     .06       0  249.04    .045       0
   312.5     .05       0     360      .1       0     430     .05       0
     590      .1       0
#XS Ineff= 2 , 0
                           412.9         3016.28
Permanent Ineff=
       F       F
Bank Sta=249.04,312.5
XS Rating Curve= 0 ,0
Exp/Cntr(USF)=0,0
Exp/Cntr=0.3,0.1

Type RM Length L Ch R = 1 ,28456   ,267.2,269.6,271.8
XS GIS Cut Line= 2
2317655.95683384502563.645779426     2318156.863      503222.085
#Sta/Elev= 30
       0 3101.19    18.4  3091.5    26.8 3088.41    46.9 3078.52   102.4  3062.1
   138.3 3053.84   178.7 3043.05   243.2 3019.98   273.3 3008.01   323.6 2997.67
   333.6 2998.58   343.7 2998.01   352.3 2993.46   363.7 2992.66     385 2993.54
   393.9 2995.62   419.1 2997.66   449.6 2996.58     555 2995.35   600.7  2997.7
   632.1 2997.25   647.8 2997.81   665.3 3000.67   680.6 3001.17   685.5 3002.85
   690.5 3005.57   720.6 3025.77   766.2 3053.95     801 3073.81   827.3 3087.25
#Mann= 6 ,-1,0
       0      .1       0     260     .06       0     350     .05       0
   352.3    .045       0     385     .05       0     630      .1       0
#XS Ineff= 2 , 0
                          417.82          3009.6
Permanent Ineff=
       F       F
Bank Sta=352.3,385
XS Rating Curve= 0 ,0
Exp/Cntr=0.3,0.1

Type RM Length L Ch R = 1 ,28186   ,296.4,300.2,304.4
XS GIS Cut Line= 2
2317462.68181445502706.1968442622317907.69987481503393.252657978
#Sta/Elev= 30
       0 3090.95    75.5 3066.95   113.2 3055.96   151.3 3043.66   165.2 3038.01
   223.1 3019.57   275.2 2998.55   289.5 2992.13   312.7 2990.67     333 2992.45
   341.6 2992.42   365.8 2987.27   379.2 2985.59   393.7 2986.38   397.4 2987.48
   403.9 2990.45   408.2 2990.91   428.4 2989.64   513.5 2989.36   580.2 2986.36
   608.8 2989.56   613.6 2991.93   625.1  3001.9   632.6 3007.48   689.8 3046.85
   699.4 3052.46   723.4  3068.2   794.7 3110.79   813.1 3122.39   818.6 3127.48
#Mann= 6 ,-1,0
       0      .1       0     200     .06       0   365.8    .045       0
   397.4      .1       0     430     .05       0     670      .1       0
#XS Ineff= 2 , 0
          338.03 2997.29  459.29         3003.82
Permanent Ineff=
       F       F
Bank Sta=365.8,397.4
XS Rating Curve= 0 ,0
Exp/Cntr=0.3,0.1

Type RM Length L Ch R = 1 ,27886   ,352.4,354.6,356.3
XS GIS Cut Line= 2
2317277.47323705502896.8058313082317582.64004703503536.318747821
#Sta/Elev= 30
       0 3046.98    35.9 3039.36    89.1 3025.82   124.5 3014.47   149.3 3004.78
   164.4 3001.43     190 2993.06   213.2 2985.24     222 2984.22   244.2 2985.42
   248.6 2984.71   261.9 2979.34   275.2 2978.16   287.3 2977.36   294.2 2978.18
   301.8 2981.03   306.2 2981.22     355 2980.24   492.4 2979.95   503.4 2979.45
     519 2976.91   551.4 2981.58   572.4 2981.52     581 2982.59   584.4  2983.8
   596.4 2991.82   620.9 3011.74   647.1  3030.9   656.4 3036.67   708.6 3062.88
#Mann= 6 ,-1,0
       0      .1       0     190     .06       0   275.2    .045       0
   294.2     .06       0     300     .05       0     520      .1       0
#XS Ineff= 2 , 0
                             451         2999.12
Permanent Ineff=
       F       F
Bank Sta=275.2,294.2
XS Rating Curve= 0 ,0
Exp/Cntr(USF)=0,0
Exp/Cntr=0.3,0.1

Type RM Length L Ch R = 1 ,27531   ,319.9,324.8,329.1
XS GIS Cut Line= 2
2316997.13923621503081.6548449962317236.27452757503707.214608048
#Sta/Elev= 30
       0 3034.36    19.7 3030.11    88.7  3010.8      98 3006.73   104.2 3002.79
   119.4 3001.73   135.2 2994.42   142.9 2992.99   162.2 2986.59   170.8 2982.01
   187.7 2967.51   196.5 2966.41   212.6 2967.65   217.9 2970.27   221.9 2970.53
   230.7 2969.25     295 2971.31   329.2 2969.69   350.6 2970.89   363.5 2967.52
   407.8 2970.98     432 2971.11     462  2973.3   479.1 2972.06   530.5 2974.46
   548.5 2980.78   564.8 2988.11   641.8 3033.55   655.7 3040.19   669.7 3048.38
#Mann= 6 ,-1,0
       0      .1       0      90     .06       0   187.7    .045       0
   212.6      .1       0     300     .05       0     510      .1       0
#XS Ineff= 2 , 0
                          345.16         2984.68
Permanent Ineff=
       F       F
Bank Sta=187.7,212.6
XS Rating Curve= 0 ,0
Exp/Cntr=0.3,0.1

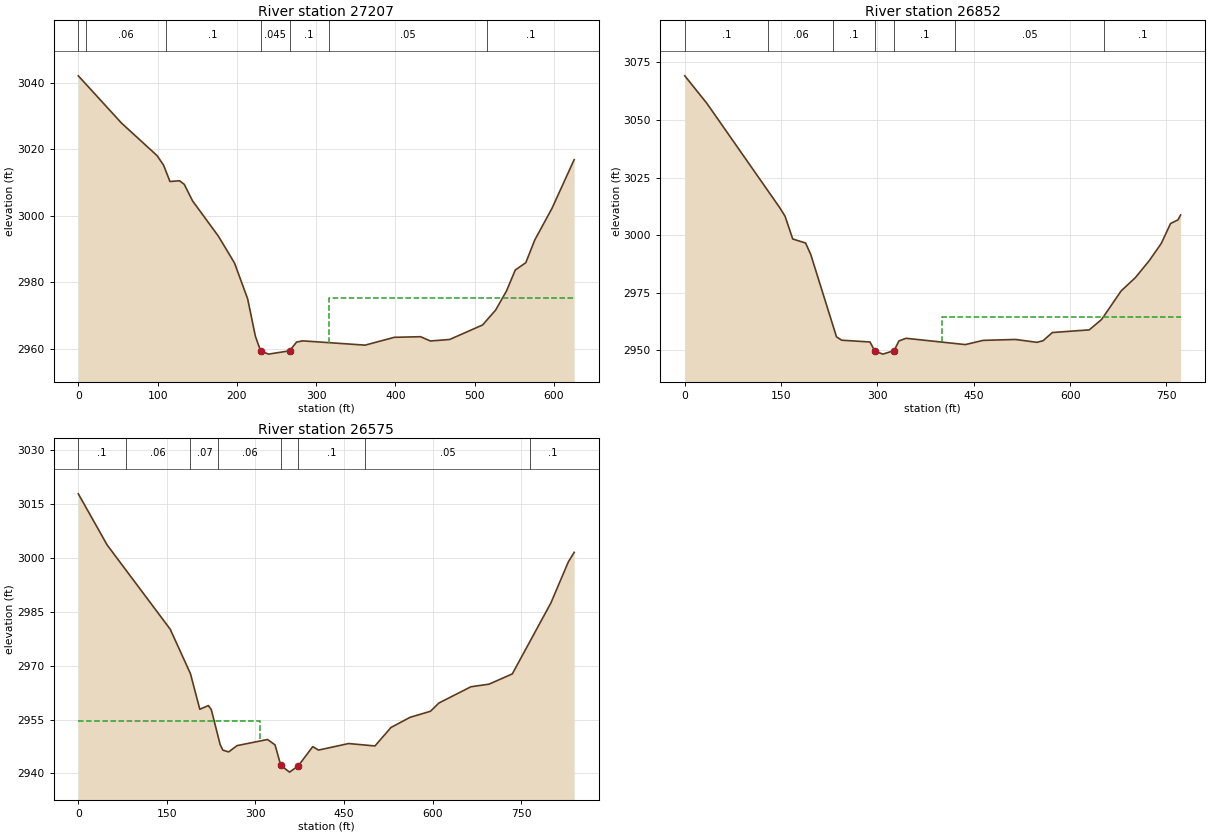
Type RM Length L Ch R = 1 ,27207   ,346.6,354.5,358
XS GIS Cut Line= 3
2316730.66565871 503155.701583452316768.05135109503347.869124134
2316869.67780476503765.395850209
#Sta/Elev= 30
       0 3042.19    54.5 3027.94    99.3 3018.15   107.5 3015.28   115.6 3010.34
   127.8 3010.56   133.6 3009.49   144.1  3004.5   176.7 2993.86     197 2985.79
   213.6 2974.98   223.4 2963.67     230 2959.24     240 2958.31   266.5 2959.31
   275.3 2961.94     283 2962.31   361.8 2961.02   398.7 2963.38   431.8 2963.56
   444.1 2962.27   468.5 2962.73     510  2967.1   526.5 2971.61   540.2 2977.37
   551.2 2983.66   564.5 2985.87   575.9 2992.76   597.6 3002.28   625.5 3016.92
#Mann= 7 ,-1,0
       0      .1       0      10     .06       0     110      .1       0
     230    .045       0   266.5      .1       0  315.77     .05       0
  515.77      .1       0
#XS Ineff= 2 , 0
                          316.13         2975.36
Permanent Ineff=
       F       F
Bank Sta=230,266.5
XS Rating Curve= 0 ,0
Exp/Cntr=0.3,0.1

Type RM Length L Ch R = 1 ,26852   ,305.1,277.3,252.6
XS GIS Cut Line= 3
2316419.11559626503137.535028018 2316451.9423049503589.814124868
2316627.01808433503856.075206078
#Sta/Elev= 30
       0 3069.19    34.3 3057.27     148 3011.88   156.1 3008.24   168.1 2998.34
   188.1  2996.6   196.2 2991.56   236.2 2955.87   244.3  2954.4   288.4 2953.62
     296 2949.64   308.5 2948.35     326 2949.88   333.4 2954.07   344.5 2955.23
   436.8 2952.49   464.4 2954.32   514.9 2954.72   548.5 2953.47     558  2954.2
   572.4 2957.73   629.8 2958.88     649 2963.39   679.6 2975.84   701.6 2981.55
   723.3 2988.96     742 2996.44   756.4 3005.06     768 3006.64   772.1 3008.77
#Mann= 7 ,-1,0
       0      .1       0     130     .06       0     230      .1       0
     296    .045       0     326      .1       0     420     .05       0
  653.47      .1       0
#XS Ineff= 2 , 0
                          399.77         2964.62
Permanent Ineff=
       F       F
Bank Sta=296,326
XS Rating Curve= 0 ,0
Exp/Cntr(USF)=0,0
Exp/Cntr=0.3,0.1

Type RM Length L Ch R = 1 ,26575   ,345.6,361.8,377.1
XS GIS Cut Line= 4
2315995.03003576503287.7370149062316065.31662534 503471.88113456
2316251.56763338503604.5560402382316530.91333681503910.332271239
#Sta/Elev= 30
       0 3017.78    48.6 3003.61   155.7 2980.11   189.9 2967.77   205.8 2957.86
   220.2 2958.89   225.2 2957.79   240.2 2948.07   244.8  2946.5   254.6    2946
   268.9 2947.75   320.5 2949.46   333.2 2947.96     343 2942.23   357.8 2940.38
   372.5 2942.11   397.1 2947.47   406.9 2946.51   457.8 2948.33   502.5 2947.66
   529.6  2952.8   562.1 2955.63   596.5 2957.31   610.8  2959.6     665 2964.12
   695.6 2964.84   735.1 2967.69   800.4  2987.4     830 2998.83   839.9 3001.51
#Mann= 8 ,-1,0
       0      .1       0      80     .06       0     190     .07       0
   237.1     .06       0     343    .045       0   372.5      .1       0
  485.78     .05       0  765.78      .1       0
#XS Ineff= 2 , 0
          307.04 2954.67
Permanent Ineff=
       F       F
Bank Sta=343,372.5
XS Rating Curve= 0 ,0
Exp/Cntr=0.3,0.1