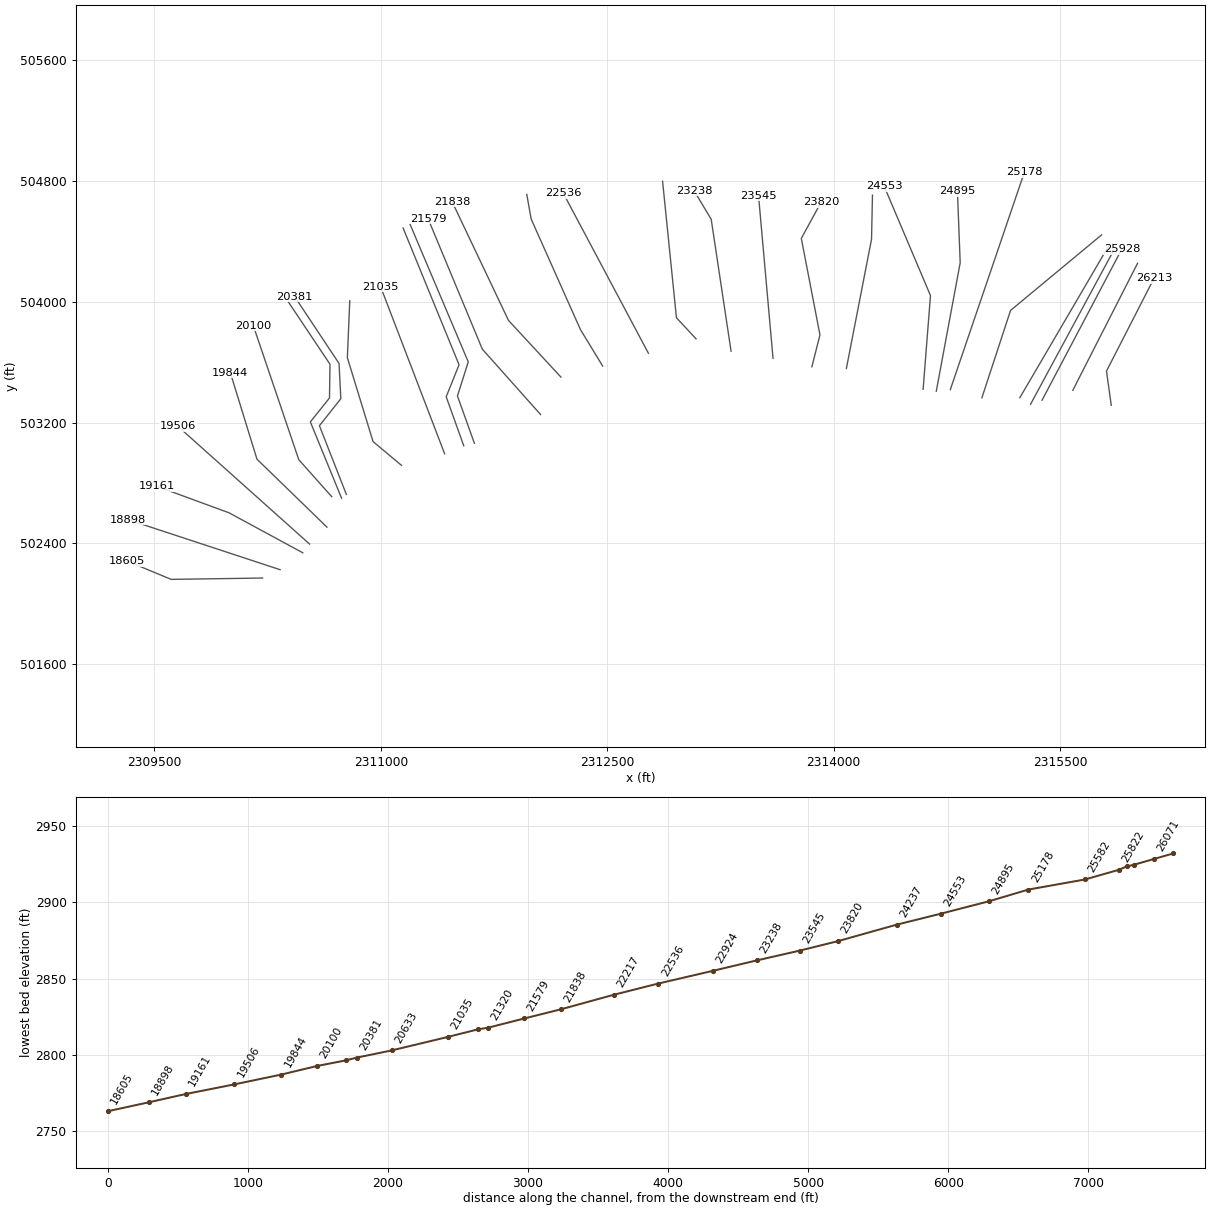
HEC-RAS study GALFRDRN.prj: GALFRDRN

--- GALFRDRN.g01 (geometry) --- (continued)

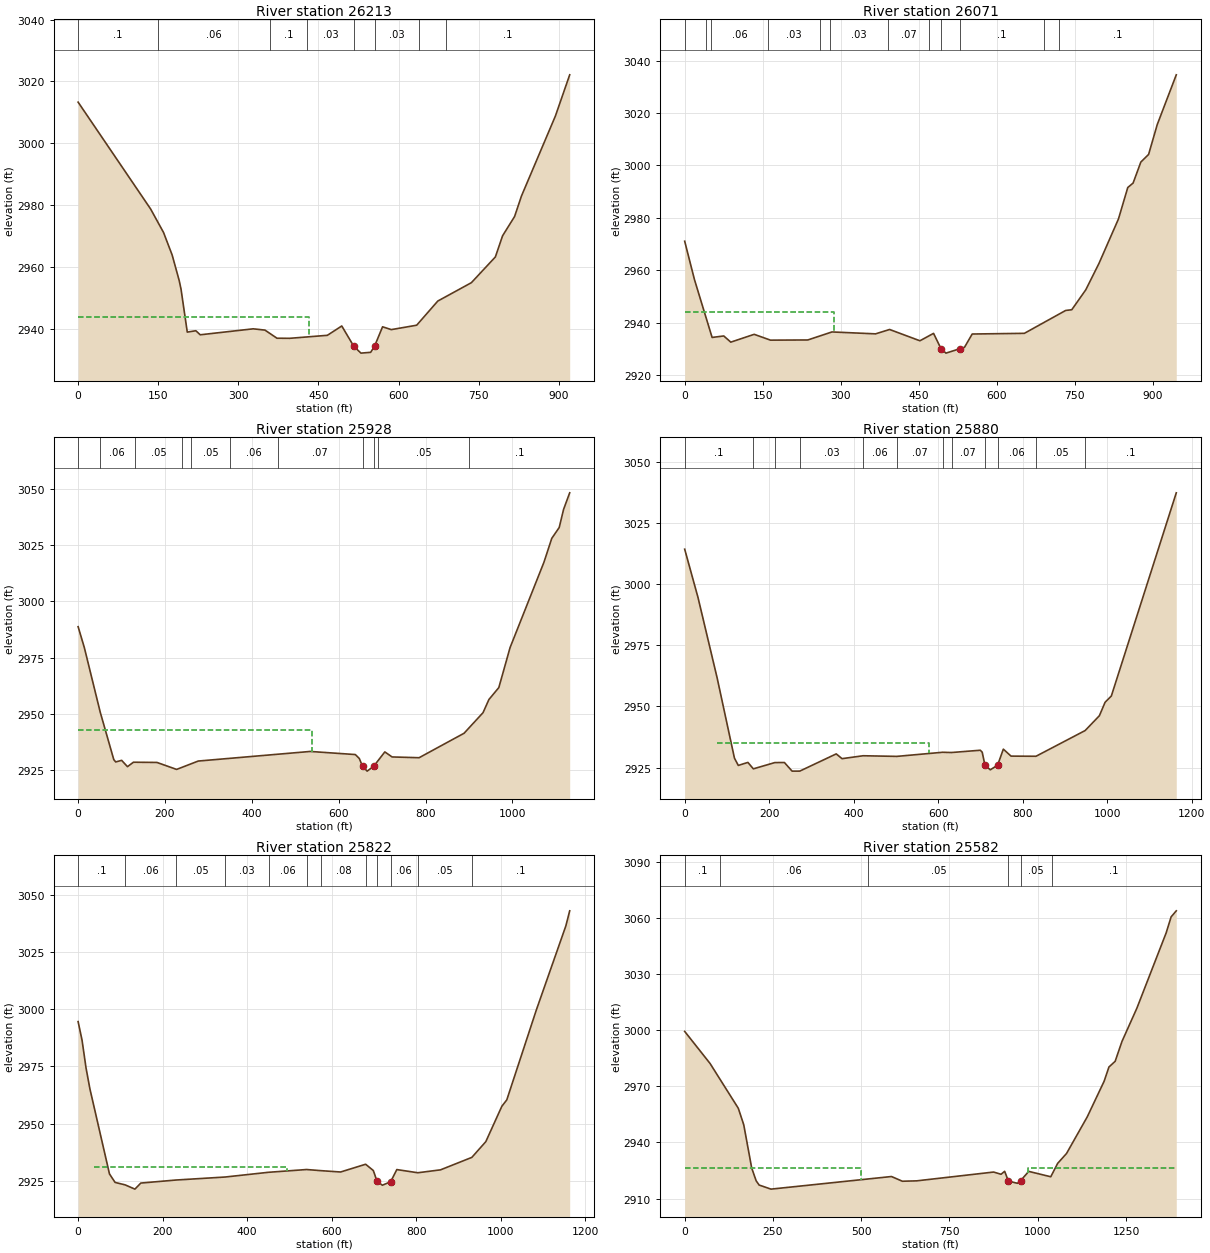
Type RM Length L Ch R = 1 ,26213   ,141.9,142.2,142.1
XS GIS Cut Line= 3
2315838.36320536503314.7905822852315806.67558334503541.607245159
2316121.88403395504157.014220164
#Sta/Elev= 30
       0 3013.28   135.7 2978.75   159.9 2971.16   176.1 2963.85   189.3 2955.58
   192.7 2952.82   204.4 2938.92   220.5 2939.36   228.6 2938.05   327.9 2939.98
   349.9 2939.56   372.4 2936.94   396.2 2936.91   466.7 2937.88   493.7  2940.9
   516.2 2934.33   529.6 2932.12   547.8 2932.38  555.022934.326   570.1 2940.64
   586.4 2939.72     634 2941.15   673.5 2948.96   736.4  2954.9   781.3 2963.22
   794.8 2970.06   817.3  2976.3   830.1 2982.89   893.7 3008.79   920.5 3022.12
#Mann= 8 ,-1,0
       0      .1       0     150     .06       0  359.02      .1       0
  429.02     .03       0   516.2    .045       0  555.02     .03       0
  639.02     .05       0  689.02      .1       0
#XS Ineff= 2 , 0
          431.55 2943.82
Permanent Ineff=
       F       F
Bank Sta=516.2,555.02
XS Rating Curve= 0 ,0
Exp/Cntr(USF)=0,0
Exp/Cntr=0.3,0.1

Type RM Length L Ch R = 1 ,26071   ,143.3,142.5,141.9
XS GIS Cut Line= 2
2315583.62918215503414.2604188112316012.79831286504256.232060823
#Sta/Elev= 30
       0 2971.07    18.8 2956.43    52.7 2934.37    75.1 2934.94    88.6 2932.58
   133.6 2935.56   164.9 2933.34   236.7 2933.41   283.1 2936.47   366.9 2935.74
   393.9 2937.41   452.2  2933.1   478.4 2935.93   492.6 2930.14   502.2 2928.39
   529.7 2930.11   537.9 2930.62   552.7 2935.68     653 2935.94   732.3 2944.66
   744.1 2944.94     771 2952.53   796.6 2962.69   833.9 2979.59   851.8 2991.58
     862 2993.26   876.9 3001.28   891.8 3004.18   908.4 3015.56     945 3034.55
#Mann= 12 ,-1,0
       0     .06       0      40      .1       0      50     .06       0
     160     .03       0     260      .1       0     280     .03       0
     390     .07       0     470      .1       0   492.6    .045       0
   529.7      .1       0     690     .05       0     720      .1       0
#XS Ineff= 2 , 0
           286.2 2943.97
Permanent Ineff=
       F       F
Bank Sta=492.6,529.7
XS Rating Curve= 0 ,0
Exp/Cntr(USF)=0,0
Exp/Cntr=0.3,0.1

Type RM Length L Ch R = 1 ,25928   ,48.4,48,47.7
BEGIN DESCRIPTION:
structure xs 4
END DESCRIPTION:
XS GIS Cut Line= 2
2315379.77334177503348.6056584332315908.29405562504349.701322358
#Sta/Elev= 30
       0 2988.71    14.2 2979.53      51 2950.71    82.1 2929.74    86.6 2928.69
   100.2  2929.4   113.7  2926.6   127.3 2928.57   181.6 2928.47   226.8 2925.38
   276.6 2929.09   534.4 2933.35   638.4 2931.97   647.5 2930.23     655 2926.71
   665.6 2924.62   680.7 2926.78   706.3 2933.15     723 2930.91   785.2 2930.57
   888.8 2941.43   932.4 2950.55     946  2956.4   968.8 2961.69   994.7 2979.44
  1072.7 3017.31  1090.7  3027.9  1107.9 3032.74  1117.9 3040.76    1132 3048.11
#Mann= 11 ,-1,0
       0      .1       0      50     .06       0     130     .05       0
     240     .03       0     260     .05       0     350     .06       0
     460     .07       0     655    .045       0   680.7     .07       0
     690     .05       0     900      .1       0
#XS Ineff= 2 , 0
          538.14 2942.86
Permanent Ineff=
       F       F
Bank Sta=655,680.7
XS Rating Curve= 0 ,0
Exp/Cntr=0.5,0.3

Type RM Length L Ch R = 1 ,25880   ,59.4,58.5,57.4
BEGIN DESCRIPTION:
structure xs 3
END DESCRIPTION:
XS GIS Cut Line= 2
2315303.57813924503321.5162422612315856.40617201504345.339210842
#Sta/Elev= 30
       0 3014.24    31.4 2994.59    76.9  2961.6   117.8 2928.88   126.9 2925.93
   149.6 2927.16   162.5 2924.53   213.3 2927.09     236 2927.12   254.2  2923.6
   272.4 2923.61   358.7 2930.64   372.4 2928.69   422.3 2929.88     502 2929.62
   610.4  2931.3   631.5  2931.2   699.7 2932.13   704.2 2931.31  710.69 2926.02
   723.4 2924.14   740.6 2926.04   754.2 2932.58   772.4 2929.73   831.5 2929.67
   947.8 2940.17   981.5 2946.23     995 2951.71  1009.8 2954.28  1163.5 3037.26
#Mann= 12 ,-1,0
       0      .1       0   162.5     .06       0   213.3     .05       0
   272.4     .03       0   422.3     .06       0     502     .07       0
   610.4     .08       0   631.5     .07       0  710.69    .045       0
   740.6     .06       0   831.5     .05       0   947.8      .1       0
#XS Ineff= 3 ,-1
   76.39     579    2935     579  690.79 2929.01   760.5  1163.5    2929
Permanent Ineff=
       F       F       F
Bank Sta=710.69,740.6
XS Rating Curve= 0 ,0
Exp/Cntr(USF)=0,0
Exp/Cntr=0.5,0.3

Type RM Length L Ch R = 1 ,25822   ,251.1,240.3,229.1
BEGIN DESCRIPTION:
structure xs 2
END DESCRIPTION:
XS GIS Cut Line= 2
2315232.65612188503365.1605606382315820.03590669504368.979883296
#Sta/Elev= 30
       0 2994.58     9.3 2986.48    18.6 2974.47    27.8 2965.26    74.2 2927.99
    87.4 2924.28   111.2  2923.2   134.4 2921.34   148.3 2923.99   231.7 2925.32
   347.7 2926.63   450.5  2928.7   540.5 2929.91   575.6  2929.4     621 2928.83
   680.2 2932.22   698.4 2929.47   707.2 2924.78   719.8 2923.05   739.4 2924.56
     754 2929.89   803.7  2928.5   857.4 2929.77   931.5 2935.22   964.5 2942.09
  1002.5 2957.57  1014.2 2960.38  1084.1 2999.69    1154 3036.49    1163 3043.03
#Mann= 12 ,-1,0
       0      .1       0   111.2     .06       0   231.7     .05       0
   347.7     .03       0   450.5     .06       0   540.5     .07       0
   575.6     .08       0   680.2     .05       0   707.2    .045       0
   739.4     .06       0   803.7     .05       0   931.5      .1       0
#XS Ineff= 3 ,-1
   38.54  494.87    2931  494.87   698.6  2927.4     748    1163  2927.4
Permanent Ineff=
       F       F       F
Bank Sta=707.2,739.4
XS Rating Curve= 0 ,0
Exp/Cntr(USF)=0,0
Exp/Cntr=0.5,0.3

Type RM Length L Ch R = 1 ,25582   ,384.5,403.8,420.2
XS GIS Cut Line= 3
2314981.43875596503364.8503518932315171.25537337503943.539713929
2315774.21108286504443.717456301
#Sta/Elev= 30
       0 2999.38    71.9 2982.23   151.9 2958.27   167.3 2949.44   189.8 2926.32
   202.4 2919.51   210.8 2917.24   244.5 2915.05   585.7 2921.79   616.5 2919.27
     657 2919.47     875 2924.18   896.1    2923   906.3 2924.58   916.9 2919.34
   942.8 2918.16   951.7  2919.6   974.4 2924.54  1036.9 2921.66  1056.4 2928.82
  1081.5 2934.09  1140.3 2953.71    1188 2972.71  1201.7 2980.35  1219.3  2983.4
  1238.6 2994.02  1280.7 3011.75  1363.8 3052.09  1377.8 3060.63  1392.4 3063.86
#Mann= 6 ,-1,0
       0      .1       0     100     .06       0     520     .05       0
   916.9    .045       0   951.7     .05       0 1039.03      .1       0
#XS Ineff= 2 , 0
          499.13 2926.55  971.02         2926.34
Permanent Ineff=
       F       F
Bank Sta=916.9,951.7
XS Rating Curve= 0 ,0
Exp/Cntr=0.3,0.1

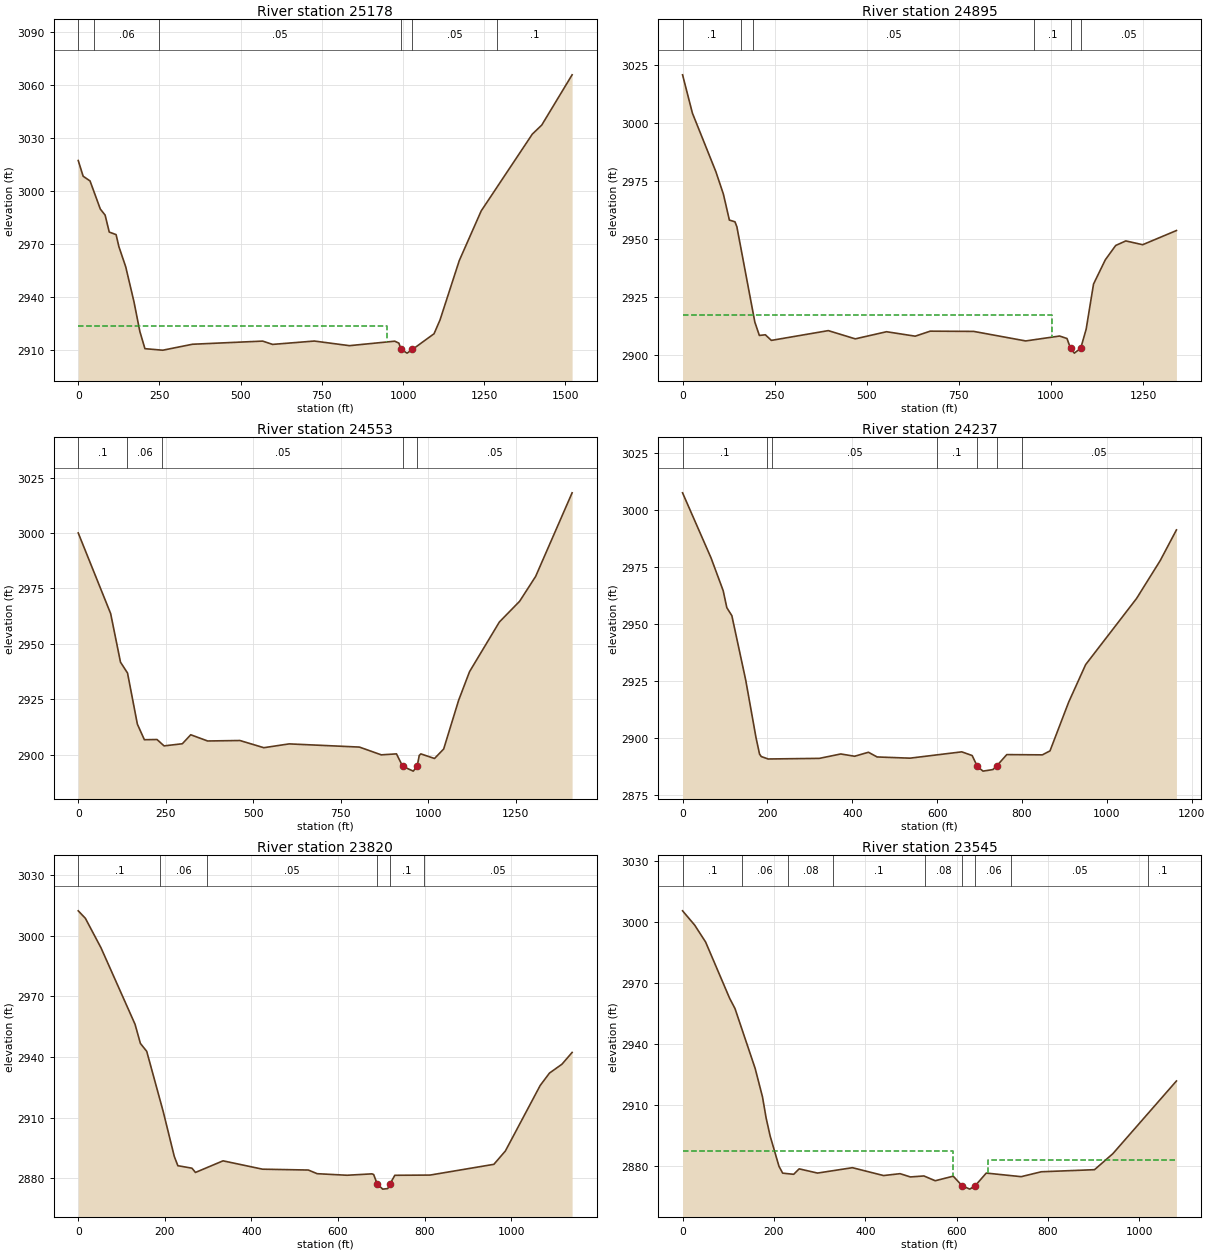
Type RM Length L Ch R = 1 ,25178   ,273.4,282.8,294.5
XS GIS Cut Line= 2
2314772.23220318503418.7898081932315262.71757094 504858.14246084
#Sta/Elev= 30
       0 3017.33    15.2 3008.43    36.3  3005.8      68  2989.9    82.8 2986.48
    95.5 2976.88   116.6 2975.44   125.1 2968.69   146.2 2957.26   171.6 2937.49
   189.8 2920.61   205.4 2910.96   260.3 2910.09   351.7 2913.46     568 2915.24
   598.4 2913.37   726.8 2915.27     835 2912.66   974.5 2915.19   987.2 2914.09
   994.12910.558  1012.5 2908.44  1029.1 2910.54  1095.5 2919.39  1113.9 2927.19
  1173.1 2960.72  1240.7 2988.85  1398.1 3032.27    1427 3037.34  1520.6 3065.78
#Mann= 6 ,-1,0
       0      .1       0      50     .06       0     250     .05       0
   994.1    .045       0  1029.1     .05       0    1290      .1       0
#XS Ineff= 2 , 0
          951.89 2923.97
Permanent Ineff=
       F       F
Bank Sta=994.1,1029.1
XS Rating Curve= 0 ,0
Exp/Cntr=0.3,0.1

Type RM Length L Ch R = 1 ,24895   ,332.4,342.4,353.5
XS GIS Cut Line= 3
2314679.26334728503408.1856787622314837.70145738504258.748164542
  2314819.355992 504734.06249483
#Sta/Elev= 30
       0  3020.9    26.8 3004.34    90.5 2979.06   110.9 2969.39   127.1 2958.19
   142.3 2957.45   147.5 2955.28   196.3 2914.11   208.5 2908.38   224.8 2908.66
   241.1 2906.24   395.7 2910.46   468.9  2906.9   553.8 2909.98   631.7 2908.06
   672.4 2910.22   790.5 2910.12   931.7    2906  1023.7 2908.12  1043.8 2907.05
  1053.5 2902.76  1063.8 2900.74    1081 2902.85  1095.8 2911.07  1115.8 2930.56
  1147.8 2941.03  1175.9 2947.21  1203.4 2949.19  1249.2 2947.55  1340.9 2953.67
#Mann= 6 ,-1,0
       0      .1       0     160     .06       0     190     .05       0
  955.19      .1       0  1053.5    .045       0    1081     .05       0
#XS Ineff= 2 , 0
         1003.27 2917.24
Permanent Ineff=
       F       F
Bank Sta=1053.5,1081
XS Rating Curve= 0 ,0
Exp/Cntr(USF)=0,0
Exp/Cntr=0.3,0.1

Type RM Length L Ch R = 1 ,24553   ,336.9,315.5,292.6
XS GIS Cut Line= 3
2314592.15013394503420.8293564322314640.90464694504041.938119147
     2314333.689      504766.919
#Sta/Elev= 30
       0 3000.02    92.6 2963.66   120.7 2941.77   140.8 2936.86   168.9 2913.81
   188.9  2906.8     225 2906.89   245.1 2904.02   297.3 2904.98   321.3 2909.04
   369.5 2906.23   461.8 2906.44     530  2903.2   602.2 2904.92     803 2903.48
   865.5 2899.98   908.9 2900.42   926.3 2894.85   956.7 2892.64   967.8 2894.74
   973.9 2899.73   978.4 2900.41  1017.5 2898.34  1043.6 2902.61  1086.2 2924.51
  1117.4 2937.46  1202.7 2959.88  1260.5 2969.21  1306.3 2980.44  1410.4 3018.11
#Mann= 5 ,-1,0
       0      .1       0     140     .06       0     240     .05       0
   926.3    .045       0   967.8     .05       0
Bank Sta=926.3,967.8
XS Rating Curve= 0 ,0
Exp/Cntr=0.3,0.1

Type RM Length L Ch R = 1 ,24237   ,403.9,417.2,430.6
XS GIS Cut Line= 3
2314083.90177866503559.1520193072314250.46950623504415.366640177
2314256.59691599504707.021147561
#Sta/Elev= 30
       0 3007.41    67.3 2978.81    95.8  2964.5   104.3  2957.1   116.2 2953.57
   148.8  2925.4   173.2 2900.07   181.4 2892.96   185.4 2891.85   201.7 2890.77
   322.6 2891.04   372.9 2892.97   405.5 2891.97   438.1 2893.72   458.5 2891.66
   535.9 2891.13   658.1  2893.9   682.6 2892.28   694.8  2887.5   708.1 2885.45
   731.5 2886.14   740.9 2887.82   764.1 2892.69     848 2892.58     866 2894.32
   910.1 2915.72     950 2932.12  1070.1 2961.13  1125.8 2977.73    1164 2991.16
#Mann= 7 ,-1,0
       0      .1       0     200     .06       0     210     .05       0
     600      .1       0   694.8    .045       0   740.9      .1       0
     800     .05       0
Bank Sta=694.8,740.9
XS Rating Curve= 0 ,0
Exp/Cntr=0.3,0.1

Type RM Length L Ch R = 1 ,23820   ,277.6,274.7,271.4
XS GIS Cut Line= 4
2313855.38517478503569.9593280182313908.75380134503781.766064673
2313785.33885243504420.5218137982313915.42487966504659.012863732
#Sta/Elev= 30
       0 3012.32    16.5 3008.62    52.7 2993.98   131.2 2956.24   143.6 2946.75
   158.2 2942.84   196.4 2912.96   221.8 2890.92   230.1 2886.29   262.6 2885.07
   270.8 2882.96   334.5  2888.7   425.6 2884.57   531.5 2884.15   551.9 2882.34
   620.9 2881.57   678.2 2882.26   682.3 2881.95   690.4 2877.34   703.2 2874.71
   714.9 2874.98   720.3 2877.33   731.2 2881.55   812.6 2881.66     960 2886.97
   986.6 2893.58    1067 2925.98  1088.4 2932.09  1117.2 2936.47  1140.7 2942.29
#Mann= 6 ,-1,0
       0      .1       0     190     .06       0  298.43     .05       0
   690.4    .045       0   720.3      .1       0  798.43     .05       0
Bank Sta=690.4,720.3
XS Rating Curve= 0 ,0
Exp/Cntr(USF)=0,0
Exp/Cntr=0.3,0.1

Type RM Length L Ch R = 1 ,23545   ,305.5,307.2,308.5
XS GIS Cut Line= 2
2313597.85669126503626.874733264     2313501.895      504703.776
#Sta/Elev= 30
       0 3005.56    26.4 2998.57    50.5 2990.18   103.2  2962.4   114.8 2957.41
   158.9 2927.94     175 2913.88     183 2903.43   191.7 2894.67   211.1 2879.69
   219.2 2876.32   243.3 2875.75   255.3 2878.44   295.5 2876.36   371.8 2879.01
     440 2875.14   476.2 2876.06   498.9 2874.45   528.4 2874.94   553.1 2872.58
   592.6 2874.83   612.1  2870.1   628.8 2868.45   640.8 2870.16   664.9 2876.36
   741.3 2874.59   785.4    2877   901.9 2878.03     942 2885.91  1081.2 2921.73
#Mann= 9 ,-1,0
       0      .1       0     130     .06       0     230     .08       0
     330      .1       0     530     .08       0   612.1    .045       0
   640.8     .06       0     720     .05       0    1020      .1       0
#XS Ineff= 2 , 0
          591.71 2887.35  669.12         2882.94
Permanent Ineff=
       F       F
Bank Sta=612.1,640.8
XS Rating Curve= 0 ,0
Exp/Cntr=0.3,0.1

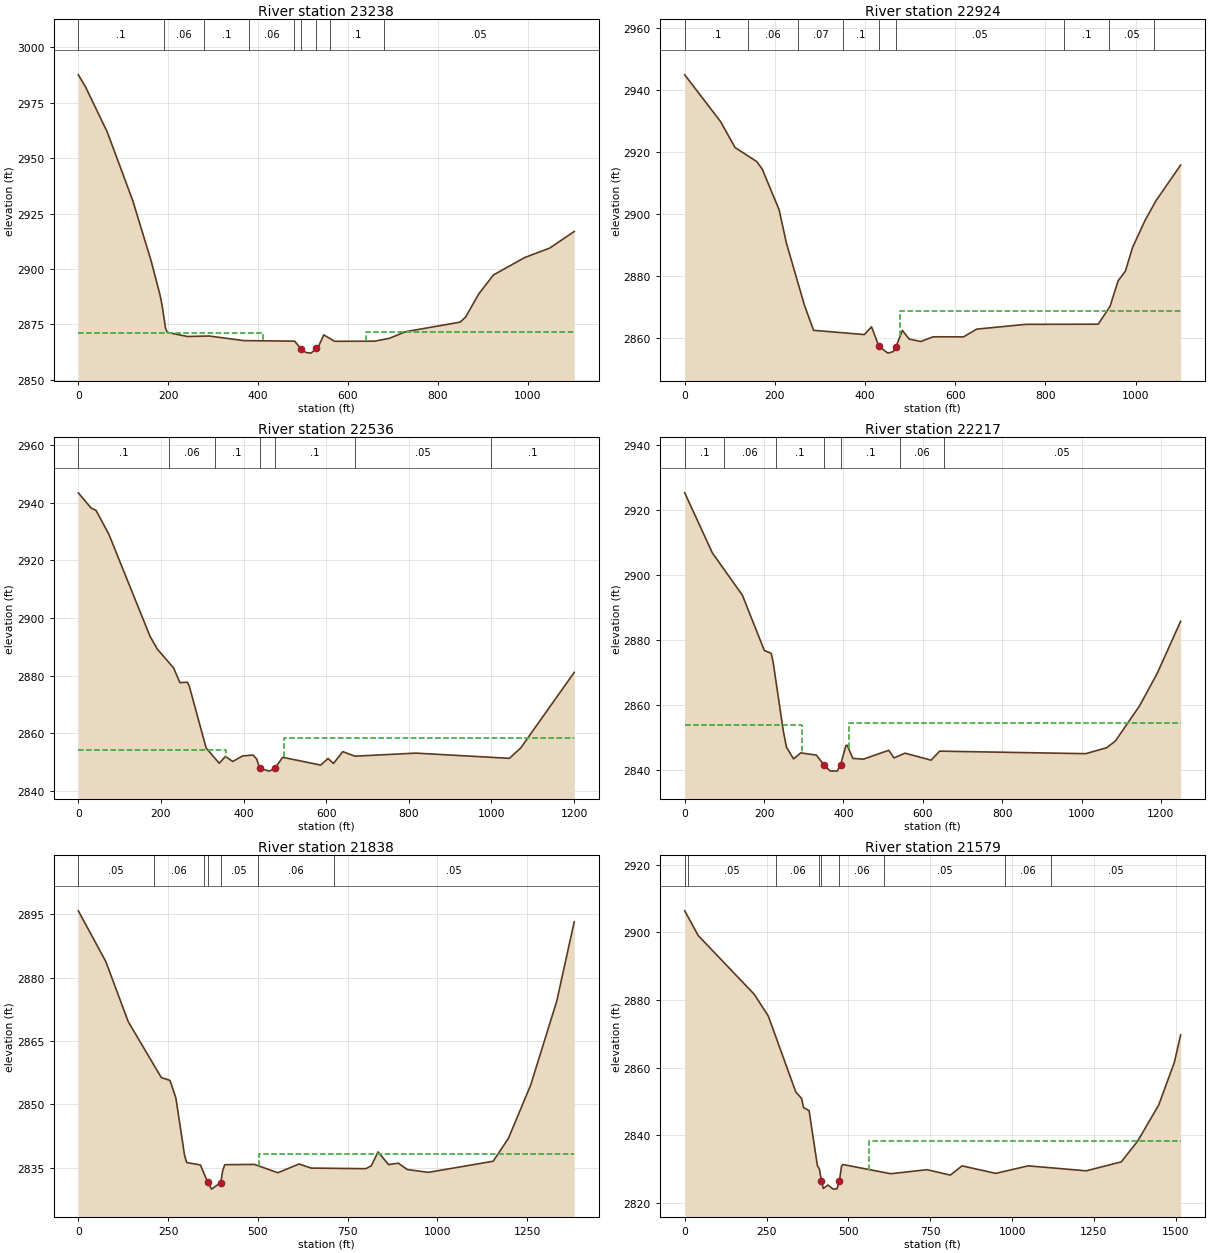
Type RM Length L Ch R = 1 ,23238   ,315.2,313.9,312.2
XS GIS Cut Line= 3
2313320.03113962503673.3610419762313188.38710556 504547.49385129
2313075.55200908504735.258718497
#Sta/Elev= 30
       0 2987.55      16 2982.11    64.5 2961.67   121.2 2930.74   161.9 2903.67
   181.8 2888.18   185.9 2884.06     194 2873.24     198 2871.37   242.5 2869.54
   291.1 2869.75   367.9 2867.68   481.2 2867.42   495.2 2864.03     506 2862.34
   517.6 2862.03   529.7 2864.13   533.8 2864.79   545.9 2870.26   570.2 2867.37
   659.2 2867.42   692.3 2868.73   727.9  2871.7   849.3 2876.01   861.4 2878.27
   890.6 2888.68   923.3 2897.28   993.1 2905.15  1048.6 2909.41  1103.1  2916.9
#Mann= 9 ,-1,0
       0      .1       0     190     .06       0     280      .1       0
     380     .06       0     480     .08       0   495.2    .045       0
   529.7     .08       0     560      .1       0     680     .05       0
#XS Ineff= 2 , 0
          411.39 2870.96  639.91         2871.77
Permanent Ineff=
       F       F
Bank Sta=495.2,529.7
XS Rating Curve= 0 ,0
Exp/Cntr=0.3,0.1

Type RM Length L Ch R = 1 ,22924   ,375.1,387.9,401.2
XS GIS Cut Line= 3
  2313088.211168503755.0817513942312958.12514077 503895.17439611
2312866.39781387504799.105508448
#Sta/Elev= 30
       0    2945    79.3 2929.94   111.7 2921.53     160 2916.98   172.1 2914.51
   209.3 2901.44   225.4 2890.75   265.6 2870.59   285.7 2862.55   398.2 2861.18
   414.3 2863.69   430.4 2857.44   450.5 2855.19   462.6 2855.69   468.5 2857.27
   482.7 2862.51   497.7 2859.73   523.3 2858.95     551 2860.46   618.2 2860.44
   647.4 2862.93   756.1 2864.48   916.9 2864.53     943 2870.22   961.1 2878.52
   977.2 2881.64   993.3 2889.37  1021.4 2898.19  1045.5 2904.47  1099.7 2915.87
#Mann= 9 ,-1,0
       0      .1       0     140     .06       0  251.18     .07       0
  351.18      .1       0   430.4    .045       0   468.5     .05       0
  841.18      .1       0  941.18     .05       0 1041.18      .1       0
#XS Ineff= 2 , 0
                          477.42         2868.68
Permanent Ineff=
       F       F
Bank Sta=430.4,468.5
XS Rating Curve= 0 ,0
Exp/Cntr(USF)=0,0
Exp/Cntr=0.3,0.1

Type RM Length L Ch R = 1 ,22536   ,321.4,318.7,316
XS GIS Cut Line= 2
     2312772.381      503659.9742312208.79266402504719.779515314
#Sta/Elev= 30
       0 2943.47    30.6 2938.25      43 2937.33    73.9 2929.09   173.5  2893.7
   191.6 2889.16   230.5 2882.73     246  2877.6   264.1 2877.75   268.7 2876.32
   309.4  2854.9   341.2 2849.62     356 2852.01   373.7 2850.25   397.4 2852.16
   422.7 2852.49   431.8 2851.12   438.8 2847.86   462.4  2846.9  475.682847.865
   494.6  2851.7   586.7    2849   604.4 2851.28   617.5 2849.56   640.2 2853.66
   669.5 2852.09   816.8 2853.15  1043.4 2851.34  1070.5 2854.89  1200.3 2881.16
#Mann= 7 ,-1,0
       0      .1       0     220     .06       0     330      .1       0
   438.8    .045       0  475.68      .1       0     670     .05       0
    1000      .1       0
#XS Ineff= 2 , 0
          356.59 2854.13  496.77         2858.31
Permanent Ineff=
       F       F
Bank Sta=438.8,475.68
XS Rating Curve= 0 ,0
Exp/Cntr=0.3,0.1

Type RM Length L Ch R = 1 ,22217   ,370,378.9,390.4
XS GIS Cut Line= 4
2312469.48750623503574.8728796762312322.27988876503816.755760501
2311995.82209313504548.940071455 2311967.0256731 504711.39323835
#Sta/Elev= 30
       0 2925.18    69.6 2906.69   145.3 2893.68   200.6 2876.67   218.1 2875.76
   222.8 2873.06   248.7 2851.68   256.4 2846.88   274.3 2843.29   292.4 2845.15
   331.8 2844.45     351 2841.41   366.8 2839.53   384.4 2839.58392.66362841.371
   406.2 2847.41   409.3 2847.51   423.8 2843.45     450 2843.21   514.2 2845.94
   527.4  2843.6   555.2 2845.06   620.8  2842.9   642.5 2845.68  1010.6  2844.9
  1063.2 2846.73  1085.1 2848.75    1146 2859.56  1190.7 2869.58  1249.8 2885.64
#Mann= 7 ,-1,0
       0      .1       0     100     .06       0     230      .1       0
     351    .045       0392.6636      .1       0  543.16     .06       0
  653.16     .05       0
#XS Ineff= 2 , 0
          296.77 2853.59   412.9         2854.19
Permanent Ineff=
       F       F
Bank Sta=351,392.6636
XS Rating Curve= 0 ,0
Exp/Cntr=0.3,0.1

Type RM Length L Ch R = 1 ,21838   ,262.2,259.8,259.1
XS GIS Cut Line= 3
 2312193.1300603503501.8534693642311845.81207696503877.183650292
2311472.65360175504662.621097015
#Sta/Elev= 30
       0 2895.83    76.6 2883.81   138.9 2869.61   231.1 2856.37   255.2  2855.7
   271.6 2851.56   295.9 2837.94   301.8 2836.25   339.9  2835.7  360.552831.567
     371 2829.97   396.5 2831.51   402.1 2834.39   407.8 2835.75   490.2 2835.82
   555.7 2833.85   614.7 2835.92   648.7 2834.95   800.8 2834.81   815.8 2835.49
   834.6 2838.78   863.9 2835.77   890.9 2836.11     916 2834.61   974.9 2833.94
  1155.1 2836.57  1197.8 2842.01  1259.8 2854.63  1332.2 2874.44  1380.9 2893.25
#Mann= 7 ,-1,0
       0     .05       0     210     .06       0     350     .05       0
  360.55    .045       0   396.5     .05       0     500     .06       0
  711.37     .05       0
#XS Ineff= 2 , 0
                          501.73         2838.34
Permanent Ineff=
       F       F
Bank Sta=360.55,396.5
XS Rating Curve= 0 ,0
Exp/Cntr(USF)=0,0
Exp/Cntr=0.3,0.1

Type RM Length L Ch R = 1 ,21579   ,296.2,258.9,227
BEGIN DESCRIPTION:
structure xs 4
END DESCRIPTION:
XS GIS Cut Line= 3
     2312057.734      503254.4192311672.36404065503687.057918177
 2311313.1175857504551.001127105
#Sta/Elev= 30
       0  2906.4    41.2 2899.08   212.7 2881.66   255.5 2875.21   339.1 2852.81
   357.2 2850.82   362.9 2848.16   379.9 2847.25   405.4 2830.91   411.3 2830.03
  417.74  2826.4   423.3 2824.21   437.6 2825.23   453.4 2824.01   465.4 2824.13
  472.52 2826.43     479  2830.8   483.4 2831.29   629.3 2828.57   740.3 2829.77
   811.3 2828.16   847.3  2830.9   949.9 2828.67  1049.3  2830.9  1226.8 2829.43
  1333.8 2832.09  1383.9 2838.24  1448.1 2848.92    1496 2861.58    1515 2869.69
#Mann= 9 ,-1,0
       0      .1       0      10     .05       0     280     .06       0
     410      .1       0  417.74    .045       0  472.52     .06       0
  609.38     .05       0  979.38     .06       0 1119.38     .05       0
#XS Ineff= 2 , 0
                          563.38         2838.22
Permanent Ineff=
       F       F
Bank Sta=417.74,472.52
XS Rating Curve= 0 ,0
Exp/Cntr=0.5,0.3

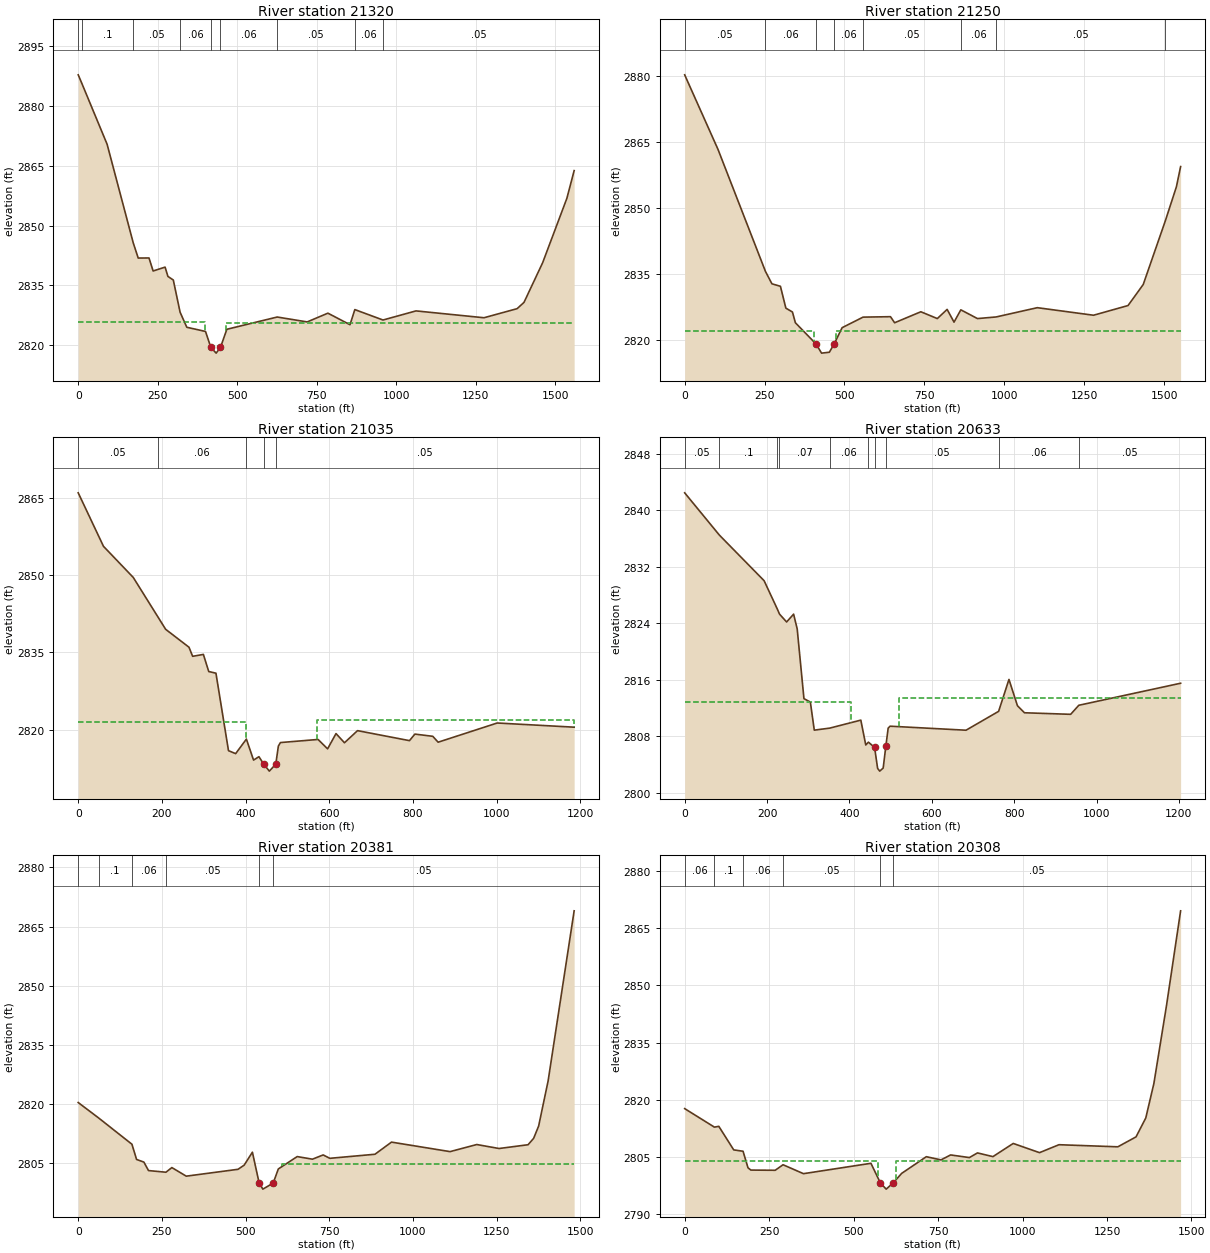
Type RM Length L Ch R = 1 ,21320   ,79.1,69.6,62.9
BEGIN DESCRIPTION:
structure xs 3
END DESCRIPTION:
XS GIS Cut Line= 4
 2311619.7675564503063.5469460552311507.64340754503376.954205521
2311579.24075561503602.5533966022311193.54392075 504514.40435547
#Sta/Elev= 30
       0 2887.88    10.7 2885.87    90.9 2870.43     173 2845.67   188.7 2841.84
   222.6 2841.86   235.6 2838.59   273.2 2839.56   282.1 2837.23   299.1 2836.31
   320.4 2828.23   341.5 2824.45   400.4 2823.39     417  2819.4   433.8 2817.95
  447.432819.392   467.4 2823.94   625.8 2827.02   720.1 2825.79   785.2 2827.99
   854.7 2825.09   869.9 2828.89   958.5 2826.27  1062.2 2828.56    1276 2826.84
  1380.2 2829.12  1401.9  2830.7  1460.5 2840.66  1536.6 2856.82  1559.6 2863.81
#Mann= 9 ,-1,0
       0     .05       0    10.7      .1       0     173     .05       0
   320.4     .06       0     417    .045       0  447.43     .06       0
   625.8     .05       0   869.9     .06       0   958.5     .05       0
#XS Ineff= 2 , 0
           398.4 2825.65  466.03         2825.58
Permanent Ineff=
       F       F
Bank Sta=417,447.43
XS Rating Curve= 0 ,0
Exp/Cntr(USF)=0,0
Exp/Cntr=0.5,0.3

Type RM Length L Ch R = 1 ,21250   ,185.3,215.6,243.6
BEGIN DESCRIPTION:
structure xs 2
END DESCRIPTION:
XS GIS Cut Line= 4
2311549.29955601503047.1286810792311433.12272707503371.343087423
2311518.22900873503583.4333449062311147.61354652504489.382252538
#Sta/Elev= 30
       0 2880.33   104.2 2863.36   252.7 2835.56     273 2832.73   299.6 2832.16
   316.6 2827.19   337.2 2826.31   346.4 2823.86  411.16 2819.01   428.3 2816.94
   452.7 2817.14   467.7 2819.03   492.7 2822.74   558.2 2825.14     644 2825.24
   656.9 2823.86     739 2826.36   790.5 2824.81   821.2  2826.9   842.8    2824
   864.1  2826.8   916.2 2824.81   974.6 2825.18  1103.4 2827.29  1279.3 2825.57
  1387.3 2827.78  1434.8 2832.57    1504 2847.08  1538.6 2854.82  1551.8 2859.43
#Mann= 8 ,-1,0
       0     .05       0   252.7     .06       0  411.16    .045       0
   467.7     .06       0   558.2     .05       0   864.1     .06       0
   974.6     .05       0    1504      .1       0
#XS Ineff= 2 , 0
           404.2    2822   474.7            2822
Permanent Ineff=
       F       F
Bank Sta=411.16,467.7
XS Rating Curve= 0 ,0
Exp/Cntr(USF)=0,0
Exp/Cntr=0.5,0.3

Type RM Length L Ch R = 1 ,21035   ,404.1,402.1,400.1
XS GIS Cut Line= 2
     2311422.775      502993.8122310998.58513034504100.664774007
#Sta/Elev= 30
       0 2865.91    60.4 2855.54   131.6  2849.5     209 2839.45   264.8 2835.97
   273.5 2834.21   299.2 2834.58     312 2831.26   329.2 2830.94   359.2 2815.92
   376.3 2815.34     402 2818.16   419.1 2814.09     432 2814.75   443.2 2813.33
   456.8 2811.95   472.2 2813.29   478.4  2816.8   483.4 2817.49   573.3 2818.09
   596.1 2816.27   616.2 2819.23   636.4 2817.45   667.6  2819.8   791.8 2817.86
   804.7 2819.13   847.5  2818.7   860.3 2817.56  1001.5 2821.28  1185.4 2820.47
#Mann= 5 ,-1,0
       0     .05       0     190     .06       0     400     .05       0
   443.2    .045       0   472.2     .05       0
#XS Ineff= 2 , 0
          400.23 2821.38  571.94         2821.83
Permanent Ineff=
       F       F
Bank Sta=443.2,472.2
XS Rating Curve= 0 ,0
Exp/Cntr=0.3,0.1

Type RM Length L Ch R = 1 ,20633   ,283.9,251.1,215
BEGIN DESCRIPTION:
structure xs 4
END DESCRIPTION:
XS GIS Cut Line= 4
2311136.67058001502917.2729398382310948.55204295503074.986482332
2310778.43954579503630.3537524582310794.36917934504007.923524393
#Sta/Elev= 30
       0 2842.48    84.2  2836.5   192.9 2830.04   225.1 2826.01   230.2 2825.32
   247.5  2824.2   264.5 2825.31   273.2 2823.22   289.6 2813.35   305.2 2812.86
   314.7 2808.89   352.4 2809.18   427.7 2810.31   439.7 2806.79   446.1 2807.19
   461.1 2806.45   468.5 2803.47   473.7 2803.09     482 2803.53  488.542806.643
   494.1 2809.18   498.8 2809.45   683.1 2808.88   762.3 2811.55   787.4 2816.07
     808 2812.35   825.1 2811.35   937.2 2811.13     957 2812.41  1204.2 2815.53
#Mann= 10 ,-1,0
       0     .05       0    84.2      .1       0   225.1     .06       0
   230.2     .07       0   352.4     .06       0   446.1     .05       0
   461.1    .045       0  488.54     .05       0   762.3     .06       0
     957     .05       0
#XS Ineff= 2 , 0
             403 2812.81  520.43         2813.51
Permanent Ineff=
       F       F
Bank Sta=461.1,488.54
XS Rating Curve= 0 ,0
Exp/Cntr=0.5,0.3

Type RM Length L Ch R = 1 ,20381   ,71.8,73.1,77.1
BEGIN DESCRIPTION:
structure xs 3
END DESCRIPTION:
XS GIS Cut Line= 5
2310771.76846747 502724.754870542310593.31712241503180.055965869
2310735.07753671503358.5073109252310723.40314965503591.995052119
2310429.87570358504033.953990808
#Sta/Elev= 30
       0 2820.33    60.6 2816.44   160.5 2809.74   174.3 2805.88   196.2 2805.21
   209.9 2803.06     262 2802.64   279.7 2803.82   322.7 2801.64   477.3 2803.38
   495.6 2804.43   520.3 2807.72   540.3 2799.96   551.6 2798.35   582.4 2799.89
   597.7 2803.47   654.1 2806.61   699.7 2805.95   731.6 2807.03   751.6 2806.17
   886.3  2807.2   935.8 2810.28  1110.6 2807.87  1190.5 2809.67  1256.9 2808.66
  1343.7 2809.62  1360.3 2811.25  1375.2 2814.35  1403.5 2825.79  1481.3 2868.99
#Mann= 6 ,-1,0
       0     .06       0    60.6      .1       0   160.5     .06       0
     262     .05       0   540.3    .045       0   582.4     .05       0
#XS Ineff= 2 , 0
             513 2804.51     609         2804.77
Permanent Ineff=
       F       F
Bank Sta=540.3,582.4
XS Rating Curve= 0 ,0
Exp/Cntr(USF)=0,0
Exp/Cntr=0.5,0.3

Type RM Length L Ch R = 1 ,20308   ,170.4,208.6,244.3
BEGIN DESCRIPTION:
structure xs 2
END DESCRIPTION:
XS GIS Cut Line= 5
2310740.08084545502699.7383268412310533.27741754503205.072509568
2310660.02790561503363.5106196652310663.36344477503586.991743379
2310388.18146408503998.930829629
#Sta/Elev= 30
       0 2817.72      88 2812.87     101 2813.08   145.2  2806.9   172.8 2806.55
   187.4 2802.21     196 2801.61   267.9 2801.56   291.1 2803.01   351.6 2800.67
   551.3 2803.39   579.5 2798.19   596.5 2796.62   617.9 2798.33   642.1 2800.74
   715.2 2805.12   758.6 2804.28     787 2805.58   842.6 2804.89   866.6 2806.11
   912.3 2805.14   972.4 2808.59  1050.2 2806.18  1107.8 2808.26    1282 2807.71
  1335.8 2810.31  1364.7 2815.27  1388.7 2824.31  1426.2 2844.83  1467.8 2869.56
#Mann= 6 ,-1,0
       0     .06       0      88      .1       0   172.8     .06       0
   291.1     .05       0   579.5    .045       0   617.9     .05       0
#XS Ineff= 2 , 0
           571.5    2804   625.9            2804
Permanent Ineff=
       F       F
Bank Sta=579.5,617.9
XS Rating Curve= 0 ,0
Exp/Cntr(USF)=0,0
Exp/Cntr=0.5,0.3

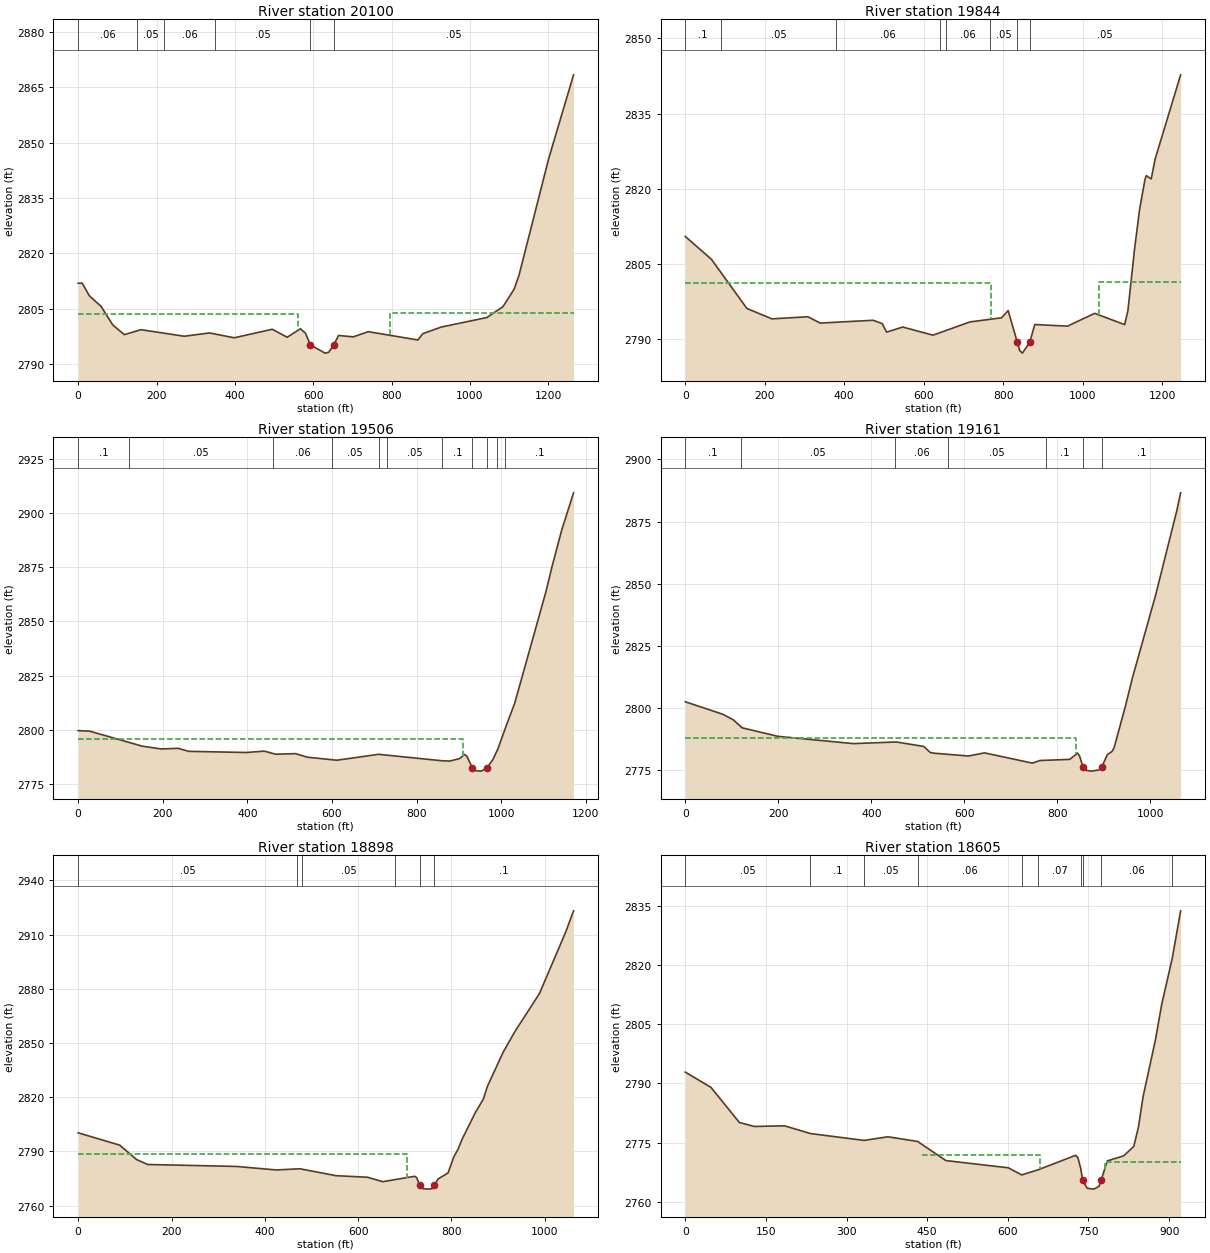
Type RM Length L Ch R = 1 ,20100   ,257.1,255.8,254.9
XS GIS Cut Line= 3
2310675.03783183502709.7449443212310456.56001686502954.907072575
 2310155.7975437503841.339658335
#Sta/Elev= 30
       0 2811.86    10.3 2811.89    28.4 2808.47    58.3  2805.6    88.5 2800.52
   117.8 2797.91   160.3 2799.26   270.8 2797.48     335 2798.38   398.4 2797.06
   495.5 2799.38   533.5 2797.21   567.3 2799.51     580 2798.34   592.7 2795.14
   630.1  2792.9   639.6 2793.13   652.2 2795.07   664.5 2797.69   702.2 2797.31
   740.4 2798.72   867.2 2796.47   879.9 2798.19   926.6 2799.97  1043.3 2802.56
  1084.3  2805.5  1112.6 2810.22  1125.3 2814.03    1201 2845.65  1264.5 2868.41
#Mann= 6 ,-1,0
       0     .06       0     150     .05       0     220     .06       0
  348.39     .05       0   592.7    .045       0   652.2     .05       0
#XS Ineff= 2 , 0
          561.01 2803.59  796.27         2803.71
Permanent Ineff=
       F       F
Bank Sta=592.7,652.2
XS Rating Curve= 0 ,0
Exp/Cntr=0.3,0.1

Type RM Length L Ch R = 1 ,19844   ,321,338.4,355.4
XS GIS Cut Line= 3
2310643.35020981502507.9448251462310179.71026659502958.242611735
2310002.92669111503531.955347241
#Sta/Elev= 30
       0 2810.53    65.8 2805.98     155 2796.18   218.1  2794.1   308.6 2794.52
   339.7 2793.26   472.6 2793.82   495.5 2793.17   506.6 2791.46   547.2 2792.47
   623.4 2790.85   716.4 2793.49   795.9 2794.31   812.6 2795.75  835.352789.519
   841.9 2787.74   848.5 2787.27     867 2789.45   879.6 2792.97   961.9 2792.65
  1030.3  2795.2  1105.8 2792.95    1114 2795.75  1130.7    2808  1143.3 2815.89
    1157 2821.91  1160.2 2822.66  1172.6 2821.99  1182.6 2825.99  1246.7 2842.75
#Mann= 8 ,-1,0
       0      .1       0      90     .05       0     380     .06       0
     640     .05       0  656.32     .06       0  766.32     .05       0
  835.35    .045       0     867     .05       0
#XS Ineff= 2 , 0
          770.59 2801.19 1041.92         2801.46
Permanent Ineff=
       F       F
Bank Sta=835.35,867
XS Rating Curve= 0 ,0
Exp/Cntr(USF)=0,0
Exp/Cntr=0.3,0.1

Type RM Length L Ch R = 1 ,19506   ,332.1,344.3,356.2
XS GIS Cut Line= 2
2310528.10207263502395.9236322472309655.21772304503176.426963684
#Sta/Elev= 30
       0  2799.5    26.7 2799.29     151 2792.35   196.3 2791.03     236 2791.34
   261.5 2789.93   397.9  2789.4     440 2790.03   466.7  2788.6   513.6 2788.87
   541.9 2787.22   611.6 2785.82     710 2788.56     860 2785.57     878 2785.43
   901.7 2786.58     913  2788.5   918.7 2787.67     932 2782.18   938.5 2781.01
   952.7 2780.78   965.8 2782.22     980 2786.05     992 2791.03    1010 2800.84
    1032 2812.32  1105.3 2863.55  1119.8 2875.23  1142.8 2892.19  1170.9 2909.52
#Mann= 11 ,-1,0
       0      .1       0     120     .05       0     460     .06       0
     600     .05       0     710     .06       0     730     .05       0
     860      .1       0     932    .045       0   965.8      .1       0
     990     .05       0    1010      .1       0
#XS Ineff= 2 , 0
          909.97 2795.65
Permanent Ineff=
       F       F
Bank Sta=932,965.8
XS Rating Curve= 0 ,0
Exp/Cntr=0.3,0.1

Type RM Length L Ch R = 1 ,19161   ,261.9,263.5,264.7
XS GIS Cut Line= 3
2310482.99192507502338.1893507442309994.58784321502603.007691203
2309516.31498523502778.324861518
#Sta/Elev= 30
       0 2802.44    80.6 2797.43   103.3 2795.16   122.3 2791.96     199 2788.53
   361.3  2785.6   453.7 2786.25   512.8 2784.46   526.5 2782.03   535.6 2781.72
     609 2780.61   643.4 2781.87   746.2 2777.74   762.6  2778.8   826.5 2779.25
   843.6 2781.78   847.8 2780.55   855.3 2776.09   860.6 2774.88   873.4 2774.52
   889.6 2775.02   895.8 2776.31   907.5 2781.18   917.7 2782.46   922.2 2784.13
   946.1 2800.53   961.3 2812.04  1011.2 2845.37  1056.6 2879.27    1065 2886.56
#Mann= 7 ,-1,0
       0      .1       0     120     .05       0     450     .06       0
  565.58     .05       0  775.58      .1       0   855.3    .045       0
   895.8      .1       0
#XS Ineff= 2 , 0
          841.01 2787.96
Permanent Ineff=
       F       F
Bank Sta=855.3,895.8
XS Rating Curve= 0 ,0
Exp/Cntr=0.3,0.1

Type RM Length L Ch R = 1 ,18898   ,293.2,292.3,290.8
BEGIN DESCRIPTION:
structure xs 4
END DESCRIPTION:
XS GIS Cut Line= 2
2310333.07804367502226.0337973572309324.64155418502557.911821731
#Sta/Elev= 30
       0 2800.27    88.8 2793.48   125.2 2785.46     149 2782.74   339.1 2781.66
   424.6 2779.71   475.3 2780.37   552.6 2776.54     620 2775.68   652.7 2773.21
     721 2776.21   725.3 2775.51   731.9 2771.29   737.9 2769.41   750.5  2769.1
   758.9 2769.37   763.6 2771.45   771.6  2774.8   792.6 2778.04   805.3 2787.11
   814.3 2791.28   822.1 2796.38   851.6 2811.73   868.2 2818.91   876.8 2825.86
   910.5  2844.8   935.8 2856.29   988.6 2877.42  1045.3 2911.76  1061.6 2923.17
#Mann= 6 ,-1,0
       0     .05       0     470     .07       0     480     .05       0
     680      .1       0   731.9    .045       0   763.6      .1       0
#XS Ineff= 2 , 0
          703.77 2788.49
Permanent Ineff=
       F       F
Bank Sta=731.9,763.6
XS Rating Curve= 0 ,0
Exp/Cntr(USF)=0,0
Exp/Cntr=0.5,0.3

Type RM Length L Ch R = 1 ,18605   ,65.2,67.7,68.8
BEGIN DESCRIPTION:
structure xs 3
END DESCRIPTION:
XS GIS Cut Line= 3
2310216.87149508502170.8849268382309611.21872063502162.021715504
2309319.71754788502283.152270395
#Sta/Elev= 30
       0 2792.88    47.7 2789.02   100.7 2780.12   128.5 2779.12   184.7 2779.28
   232.7 2777.33   332.7 2775.59   376.9 2776.51   432.1 2775.33   484.7 2770.49
   600.8 2768.66   625.8 2766.86   656.4 2768.16     726 2771.81   730.3 2771.22
   735.9 2768.31   738.9 2765.54   747.6 2763.47   759.9 2763.26   769.6 2763.97
  773.72  2765.6   784.9 2770.41   815.5 2771.68   834.3 2774.08   842.9 2778.97
   851.6 2786.71   874.5 2801.03   886.2 2810.03   905.8  2821.7   921.4  2833.7
#Mann= 10 ,-1,0
       0     .05       0   232.7      .1       0   332.7     .05       0
   432.1     .06       0   625.8      .1       0   656.4     .07       0
   735.9     .06       0   738.9    .045       0  773.72     .06       0
   905.8      .1       0
#XS Ineff= 3 ,-1
     440  659.72    2772  659.72   731.9 2768.07  780.32   921.4 2770.17
Permanent Ineff=
       F       F       F
Bank Sta=738.9,773.72
XS Rating Curve= 0 ,0
Exp/Cntr(USF)=0,0
Exp/Cntr=0.5,0.3