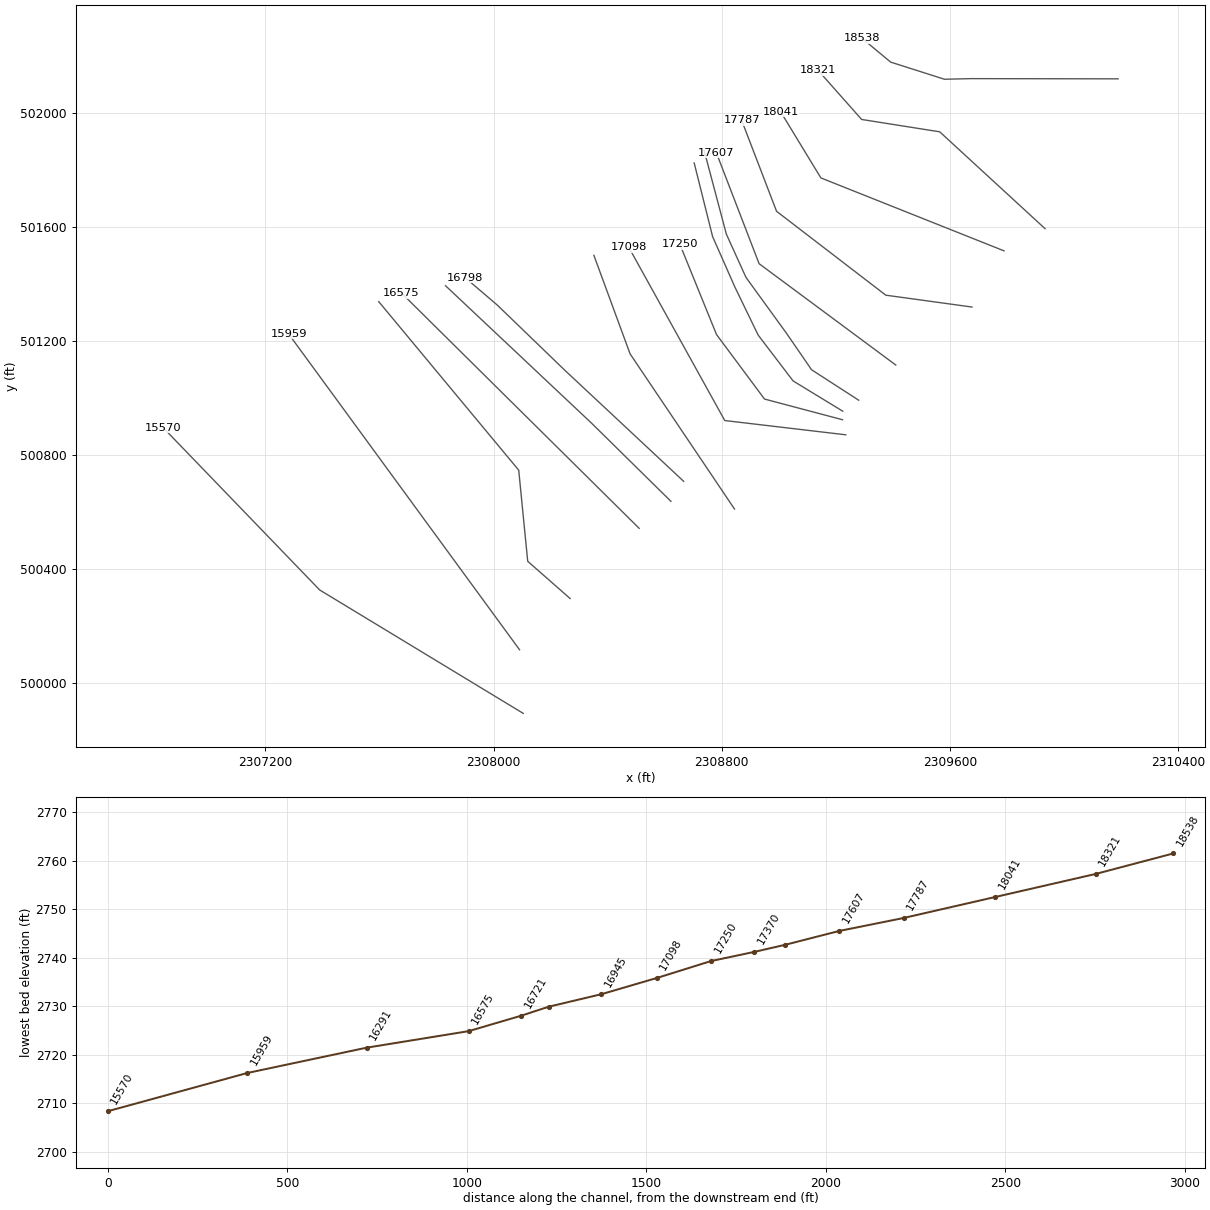
HEC-RAS study GALFRDRN.prj: GALFRDRN

--- GALFRDRN.g01 (geometry) --- (continued)

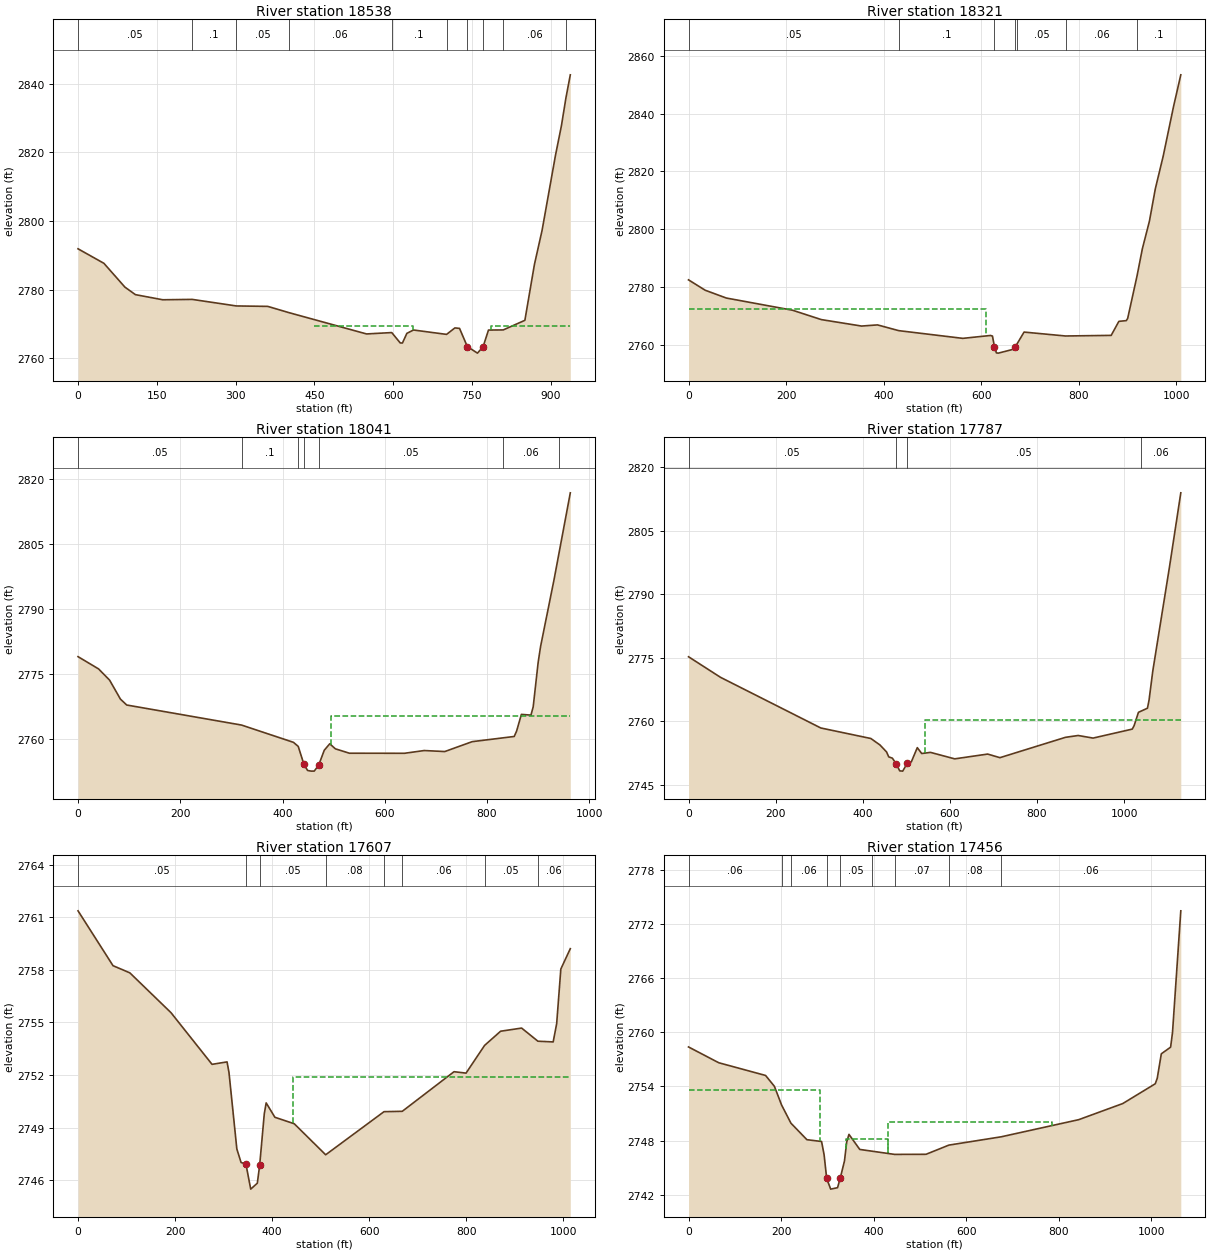
Type RM Length L Ch R = 1 ,18538   ,209.1,216.3,217
BEGIN DESCRIPTION:
structure xs 2
END DESCRIPTION:
XS GIS Cut Line= 5
2310189.46054454502118.4466460912309673.64076425 502119.15905042
2309580.63175643502116.9706031782309391.83119577502177.194843947
2309291.68133931502260.545369647
#Sta/Elev= 30
       0 2791.88    49.3 2787.65    89.3 2780.71   109.3 2778.52   161.3 2777.03
   217.3 2777.14   301.3 2775.23   361.3  2775.1   401.3 2773.29   549.3 2767.07
   597.3 2767.47   613.5 2764.45   617.7 2764.43   626.1 2767.24   638.7 2768.22
   701.7 2766.94   717.6 2768.83   726.4 2768.69   741.2  2763.4   760.5 2761.48
  771.192763.313   781.5  2768.2   809.6 2768.24   850.8 2771.04     869 2787.32
   883.5 2797.22     909 2819.06   920.4 2827.75   928.9  2835.8   937.3 2842.58
#Mann= 10 ,-1,0
       0     .05       0   217.3      .1       0   301.3     .05       0
   401.3     .06       0   597.3      .1       0   701.7     .05       0
   741.2    .045       0  771.19     .05       0   809.6     .06       0
   928.9      .1       0
#XS Ineff= 3 ,-1
  449.76  638.39 2769.29  638.39  729.01 2766.91  785.65   937.3 2769.29
Permanent Ineff=
       F       F       F
Bank Sta=741.2,771.19
XS Rating Curve= 0 ,0
Exp/Cntr=0.5,0.3

Type RM Length L Ch R = 1 ,18321   ,285.8,280.2,272.3
XS GIS Cut Line= 4
2309933.24873241501592.8065876462309563.94826018501932.563022094
 2309290.1735101501975.8942775022309137.52931492502148.234497875
#Sta/Elev= 30
       0 2782.56    34.1 2778.98    77.5 2776.28   213.2 2772.07   272.3 2768.83
   354.8  2766.6   387.4    2767   430.8 2765.02   562.3 2762.35     619 2763.35
   623.1 2763.14   627.1 2759.53   631.2 2757.33   635.2 2757.25   663.6 2758.48
     670 2759.47     674 2760.59   687.9 2764.52   772.9 2763.17   866.5 2763.38
   882.2 2768.22   897.5 2768.48   900.3 2769.25   919.6 2784.01   930.3 2793.23
   944.9 2802.85     957 2814.03   973.1 2825.29   994.4  2842.5  1009.2 2853.38
#Mann= 7 ,-1,0
       0     .05       0   430.8      .1       0   627.1    .045       0
     670      .1       0     674     .05       0   772.9     .06       0
   919.6      .1       0
#XS Ineff= 2 , 0
          609.13 2772.41
Permanent Ineff=
       F       F
Bank Sta=627.1,670
XS Rating Curve= 0 ,0
Exp/Cntr(USF)=0,0
Exp/Cntr=0.3,0.1

Type RM Length L Ch R = 1 ,18041   ,262.5,254.8,246.5
XS GIS Cut Line= 3
     2309789.478      501514.837 2309147.3121344501770.748195608
2309006.15774642502002.963188891
#Sta/Elev= 30
       0 2778.91    40.2 2776.08    61.7  2773.5    82.9 2769.12    95.2 2767.75
     320 2763.12   421.5 2759.13   430.8 2758.19     442 2754.02   449.1 2752.64
   456.3 2752.49   462.1  2752.5   470.8 2753.88   481.7 2757.31   492.4  2758.8
   503.4 2757.64     531 2756.62   638.7 2756.61   677.1 2757.24   717.5 2757.01
     771 2759.29   853.3 2760.49     858 2761.75   867.3 2765.58     886 2765.42
   890.4 2767.32   900.1 2777.59   904.9 2781.29   931.2 2796.69     963 2816.72
#Mann= 7 ,-1,0
       0     .05       0     320      .1       0     430     .05       0
     442    .045       0   470.8     .05       0  831.28     .06       0
  941.28      .1       0
#XS Ineff= 2 , 0
                          494.62         2765.31
Permanent Ineff=
       F       F
Bank Sta=442,470.8
XS Rating Curve= 0 ,0
Exp/Cntr=0.3,0.1

Type RM Length L Ch R = 1 ,17787   ,179.1,179.6,180
XS GIS Cut Line= 4
2309676.91636716501317.7396163432309374.91064765501359.320113957
2308991.93238016501653.6662681172308869.37933456501973.179565569
#Sta/Elev= 30
       0  2775.2    73.4 2770.34   303.6 2758.37   418.6 2755.88   439.5 2754.35
   454.6 2752.71   459.7 2751.53   467.9 2751.24   476.4 2749.95   484.9 2748.23
   491.7 2748.17   502.1 2750.02   511.4 2750.34   525.2 2753.72   535.3 2752.33
   555.5  2752.6     611 2751.07   686.7  2752.2   714.9 2751.35   865.4 2756.16
   894.5 2756.59   928.7 2755.98  1018.7  2758.1    1023 2758.94  1032.9 2762.07
  1053.6 2763.04  1057.3 2765.01  1065.8 2771.83  1104.4 2796.61  1130.1 2813.94
#Mann= 4 ,-1,0
       0     .05       0   476.4    .045       0   502.1     .05       0
 1037.88     .06       0
#XS Ineff= 2 , 0
                          541.94         2760.15
Permanent Ineff=
       F       F
Bank Sta=476.4,502.1
XS Rating Curve= 0 ,0
Exp/Cntr(USF)=0,0
Exp/Cntr=0.3,0.1

Type RM Length L Ch R = 1 ,17607   ,163.2,151.4,143.2
BEGIN DESCRIPTION:
structure xs 4
IFA placed conservatively to uncross profile
END DESCRIPTION:
XS GIS Cut Line= 3
2309409.92580353501114.2140227612308930.65585736501469.836699719
2308780.74722122501859.380308942
#Sta/Elev= 30
       0 2761.37    72.1 2758.24   106.8 2757.83   191.5 2755.56   276.1 2752.61
     307 2752.75     311 2752.15   327.2 2747.78   335.9 2747.01   345.9 2746.92
   355.8 2745.49   369.4 2745.83   374.2 2746.85   383.7 2749.78   387.6 2750.41
   405.6 2749.59   445.5 2749.22   510.2 2747.45   630.4 2749.91     668 2749.93
   774.6 2752.19   799.4 2752.11   837.6 2753.69   870.6  2754.5   913.9 2754.68
   947.5 2753.93   978.9 2753.89   986.1 2754.93   994.7 2758.05  1014.2 2759.21
#Mann= 8 ,-1,0
       0     .05       0   345.9    .045       0   374.2     .05       0
   510.2     .08       0   630.4     .05       0     668     .06       0
   837.6     .05       0   947.5     .06       0
#XS Ineff= 2 , 0
                          442.14         2751.91
Permanent Ineff=
       F       F
Bank Sta=345.9,374.2
XS Rating Curve= 0 ,0
Exp/Cntr(USF)=0,0
Exp/Cntr=0.5,0.3

Type RM Length L Ch R = 1 ,17456   ,82.7,86,86.7
BEGIN DESCRIPTION:
structure xs 3
terrain IFAs placed on the ROB to uncross 500 and 101 profiles
END DESCRIPTION:
XS GIS Cut Line= 6
2309280.02684107500990.7133590942309114.48542575501097.800668439
2309027.14602996501225.0561606582308884.69846526501421.690860377
2308815.76237711501573.7879437532308738.15683934501866.450149387
#Sta/Elev= 30
       0 2758.38    65.3 2756.63   166.6 2755.22   185.6 2754.02   201.2 2751.94
   221.4 2749.93   255.9  2748.1   287.6  2747.9   293.1 2746.42  298.63  2743.8
   307.3 2742.62   322.1 2742.78   327.8 2743.81   337.1 2745.74   341.9 2747.83
   346.8 2748.69   370.2 2747.02   396.1 2746.83   445.4 2746.47   513.4 2746.48
   562.8  2747.5   675.9 2748.42   843.5 2750.32   938.8 2752.11  1008.9  2754.3
  1013.2 2754.91    1022 2757.62  1042.1 2758.36  1046.2 2759.99  1064.1 2773.47
#Mann= 9 ,-1,0
       0     .06       0   201.2     .05       0   221.4     .06       0
  298.63    .045       0   327.8     .05       0   396.1     .06       0
   445.4     .07       0   562.8     .08       0   675.9     .06       0
#XS Ineff= 3 ,-1
       0   284.2 2753.63   340.2  431.51 2748.19  431.51  786.18 2750.04
Permanent Ineff=
       F       F       F
Bank Sta=298.63,327.8
XS Rating Curve= 0 ,0
Exp/Cntr=0.5,0.3

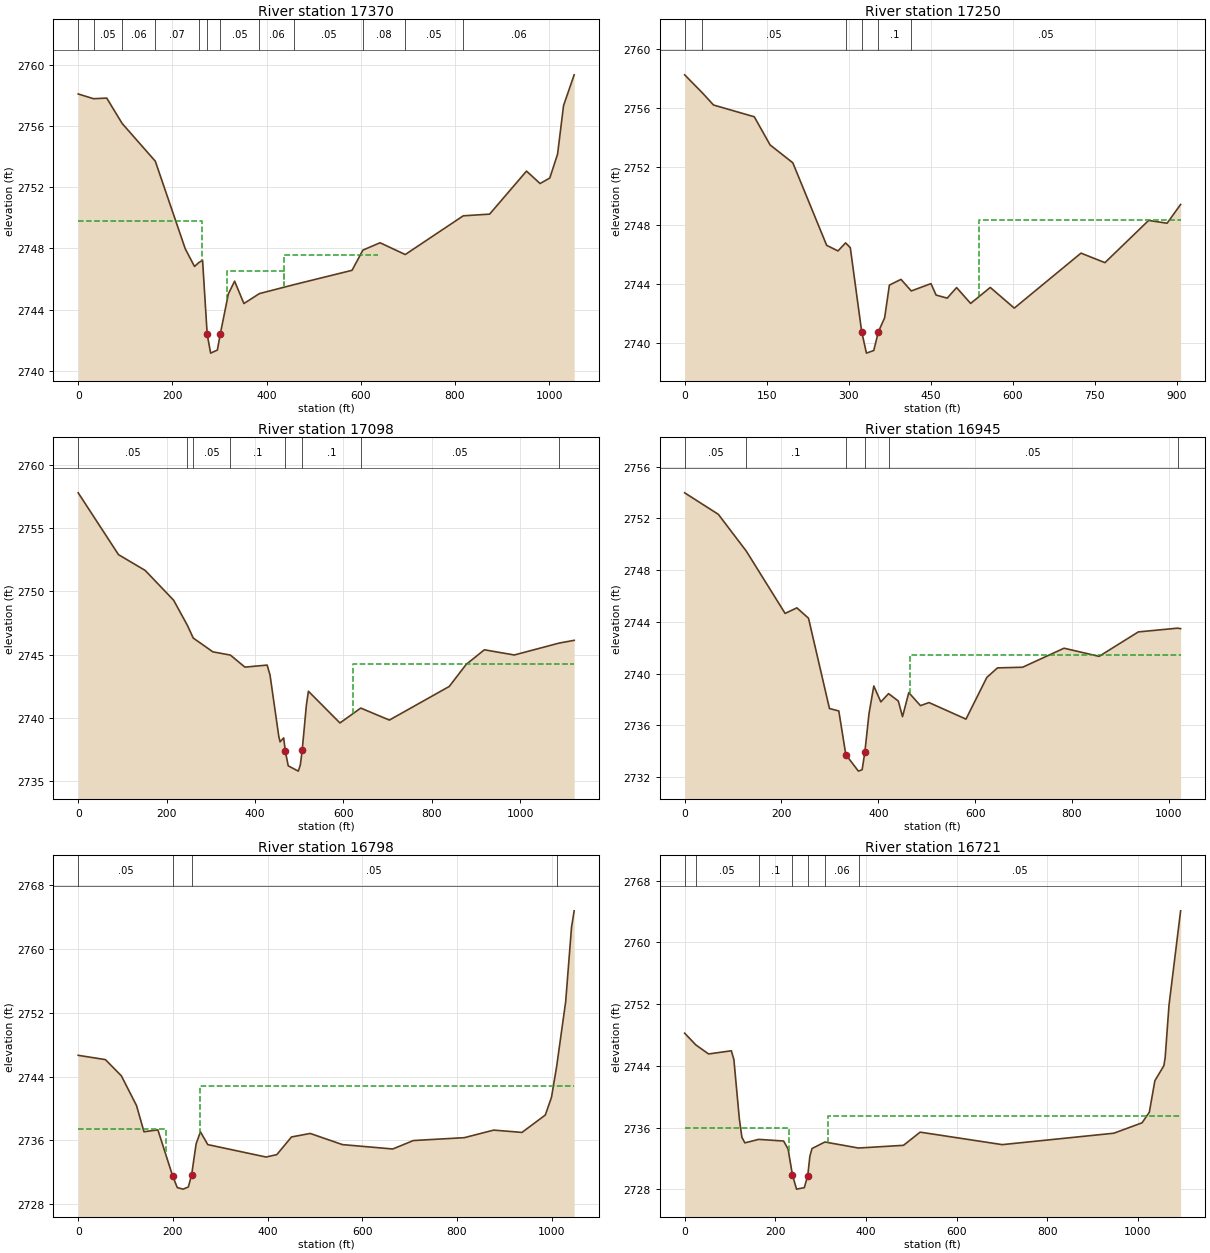
Type RM Length L Ch R = 1 ,17370   ,119.8,119.5,118.9
BEGIN DESCRIPTION:
structure xs 2
terrain IFAs placed on the ROB to uncross 500 and 101 profiles
END DESCRIPTION:
XS GIS Cut Line= 6
2309223.90778789500952.2689267922309049.92623209501058.408618069
2308927.37318649501219.2594904162308845.30641489501388.864151735
2308767.61653777501565.034154782 2308703.0573441501823.270929435
#Sta/Elev= 30
       0 2758.09    32.5 2757.78    60.6 2757.82    93.4 2756.16   163.7  2753.7
   227.4 2747.97     247 2746.82   255.5 2747.06   264.1 2747.23  273.89  2742.4
   281.2 2741.16   295.5 2741.36  301.65  2742.4   318.9 2745.03   332.1 2745.86
   351.9  2744.4   384.9 2745.05   457.8 2745.63   581.5 2746.57   604.6 2747.89
     641 2748.37   694.5  2747.6   817.7 2750.13   873.7 2750.24     952 2753.05
   980.9 2752.24  1001.5  2752.6    1018 2754.16  1030.7 2757.33  1053.2 2759.34
#Mann= 12 ,-1,0
       0     .06       0    32.5     .05       0    93.4     .06       0
   163.7     .07       0   255.5     .06       0  273.89    .045       0
  301.65     .05       0   384.9     .06       0   457.8     .05       0
   604.6     .08       0   694.5     .05       0   817.7     .06       0
#XS Ineff= 3 ,-1
       0  262.99 2749.77  316.39     437  2746.5     437  637.19 2747.58
Permanent Ineff=
       F       F       F
Bank Sta=273.89,301.65
XS Rating Curve= 0 ,0
Exp/Cntr(USF)=0,0
Exp/Cntr=0.5,0.3

Type RM Length L Ch R = 1 ,17250   ,155.8,151.6,148.1
XS GIS Cut Line= 4
2309223.18778875500922.2740688812308949.58045489500994.863769702
2308781.26807167501221.4074513852308652.84013945501538.089992329
#Sta/Elev= 30
       0 2758.27    32.1 2757.05    52.8 2756.21   127.3 2755.41   156.2 2753.49
   197.8 2752.27   259.7 2746.64   280.4 2746.26   294.3 2746.81   302.9 2746.48
   323.7 2740.76   332.4 2739.29   345.8 2739.47   354.3 2740.75   365.7  2741.7
   374.4 2743.93   395.6 2744.32   414.4 2743.53   450.4 2744.03   459.8 2743.25
   480.1 2743.04   497.3 2743.76     523 2742.68   558.9 2743.77   602.8 2742.36
   724.8 2746.11   768.6 2745.46   848.5 2748.34   882.3 2748.15     907 2749.43
#Mann= 6 ,-1,0
       0     .06       0    32.1     .05       0   294.3      .1       0
   323.7    .045       0   354.3      .1       0   414.4     .05       0
#XS Ineff= 2 , 0
                          537.63         2748.37
Permanent Ineff=
       F       F
Bank Sta=323.7,354.3
XS Rating Curve= 0 ,0
Exp/Cntr(USF)=0,0
Exp/Cntr=0.3,0.1

Type RM Length L Ch R = 1 ,17098   ,148.6,153.5,154.5
XS GIS Cut Line= 3
2309234.61588799500869.396664366  2308810.291259500919.442218149
2308473.94442683501526.995188891
#Sta/Elev= 30
       0  2757.8    91.1 2752.91   151.5 2751.66   215.9  2749.3     247 2747.31
   260.2 2746.31   304.5 2745.22   344.3 2744.96     377 2744.01   427.3 2744.17
   433.8 2743.39   453.6 2738.54   456.6  2738.1   464.7 2738.41  468.312737.391
     475  2736.2   497.8 2735.78   502.4 2736.27   506.6 2737.43   516.1 2741.02
   520.7  2742.1     592 2739.59     639 2740.77   703.8 2739.82   839.2 2742.48
   877.4 2744.22   918.6 2745.38   986.3 2744.97  1087.6 2745.91  1121.7 2746.13
#Mann= 8 ,-1,0
       0     .05       0     247      .1       0   260.2     .05       0
   344.3      .1       0  468.31    .045       0   506.6      .1       0
     639     .05       0  1087.6     .06       0
#XS Ineff= 2 , 0
                           621.2         2744.28
Permanent Ineff=
       F       F
Bank Sta=468.31,506.6
XS Rating Curve= 0 ,0
Exp/Cntr=0.3,0.1

Type RM Length L Ch R = 1 ,16945   ,141,146.6,157.3
BEGIN DESCRIPTION:
structure xs 4
END DESCRIPTION:
XS GIS Cut Line= 3
2308844.45467627500608.9486980962308478.36257578501153.358722082
2308351.37859996501499.187422183
#Sta/Elev= 30
       0 2753.97    69.5 2752.31   127.2 2749.47   207.5 2744.65   231.7 2745.08
   255.8 2744.28   299.1  2737.3   318.4 2737.11   332.9 2733.73   358.9 2732.46
   366.6 2732.57   372.2 2733.93   380.8 2736.91   390.7 2739.04   405.2 2737.81
   421.2 2738.45   441.3 2737.88     450 2736.67     463 2738.53   487.1 2737.52
   504.7 2737.76   581.1 2736.48   624.1  2739.7   646.2 2740.44   698.1 2740.49
   783.7 2741.96   856.1 2741.33   937.1 2743.22  1018.1 2743.51  1024.5 2743.47
#Mann= 6 ,-1,0
       0     .05       0   127.2      .1       0   332.9    .045       0
   372.2      .1       0   421.2     .05       0  1018.1     .06       0
#XS Ineff= 2 , 0
                          466.36          2741.4
Permanent Ineff=
       F       F
Bank Sta=332.9,372.2
XS Rating Curve= 0 ,0
Exp/Cntr(USF)=0,0
Exp/Cntr=0.5,0.3

Type RM Length L Ch R = 1 ,16798   ,80.8,77.4,76.3
BEGIN DESCRIPTION:
structure xs 3
END DESCRIPTION:
XS GIS Cut Line= 4
2308666.13675278500706.2130199992308248.71070461501096.621200972
2308012.30436665501324.9221787732307900.18021779501420.835607316
#Sta/Elev= 30
       0 2746.68    57.5 2746.14    91.2  2744.1   123.2 2740.37     139 2737.08
   168.3 2737.32   199.9 2731.47   209.3 2730.07   221.8 2729.88   232.6 2730.15
  239.45 2731.61   249.1 2735.57   258.2 2737.08   273.7 2735.47   396.9 2733.91
   419.5 2734.21   450.6 2736.43   490.1 2736.87   558.2 2735.47   664.5 2734.92
   708.1 2735.98   815.6 2736.34   877.8 2737.29   937.5    2737   986.7 2739.18
   999.8  2741.4  1010.9 2745.35  1029.8 2753.42  1042.1 2762.73  1047.7 2764.82
#Mann= 4 ,-1,0
       0     .05       0   199.9    .045       0  239.45     .05       0
  1010.9     .06       0
#XS Ineff= 2 , 0
           185.9 2737.45  256.81        2742.779
Permanent Ineff=
       F       F
Bank Sta=199.9,239.45
XS Rating Curve= 0 ,0
Exp/Cntr(USF)=0,0
Exp/Cntr=0.5,0.3

Type RM Length L Ch R = 1 ,16721   ,146.4,145.8,145.7
BEGIN DESCRIPTION:
structure xs 2
END DESCRIPTION:
XS GIS Cut Line= 3
2308621.55727191500635.966565291 2308343.2732398500910.197917324
2307831.28465645501392.466846761
#Sta/Elev= 30
       0 2748.23    24.5 2746.72    52.7 2745.54     103 2745.95   108.6  2744.8
   120.6 2737.11   126.3 2734.73   132.8 2734.01   163.1 2734.46   218.3 2734.25
   228.1 2733.21  237.84 2729.82   246.8 2728.01   263.9  2728.2   271.5 2729.76
   276.2 2732.27     281 2733.28   309.5 2734.12   383.5 2733.34   482.7 2733.69
   519.5  2735.4   700.6 2733.78   946.8 2735.26    1009 2736.61  1025.1 2737.99
  1037.3 2742.07  1057.1 2744.01    1060 2745.06  1068.5 2751.87  1094.1  2764.1
#Mann= 8 ,-1,0
       0     .06       0    24.5     .05       0   163.1      .1       0
  237.84    .045       0   271.5     .05       0   309.5     .06       0
   383.5     .05       0  1094.1     .06       0
#XS Ineff= 2 , 0
           229.3    2736  315.76        2737.544
Permanent Ineff=
       F       F
Bank Sta=237.84,271.5
XS Rating Curve= 0 ,0
Exp/Cntr(USF)=0,0
Exp/Cntr=0.5,0.3

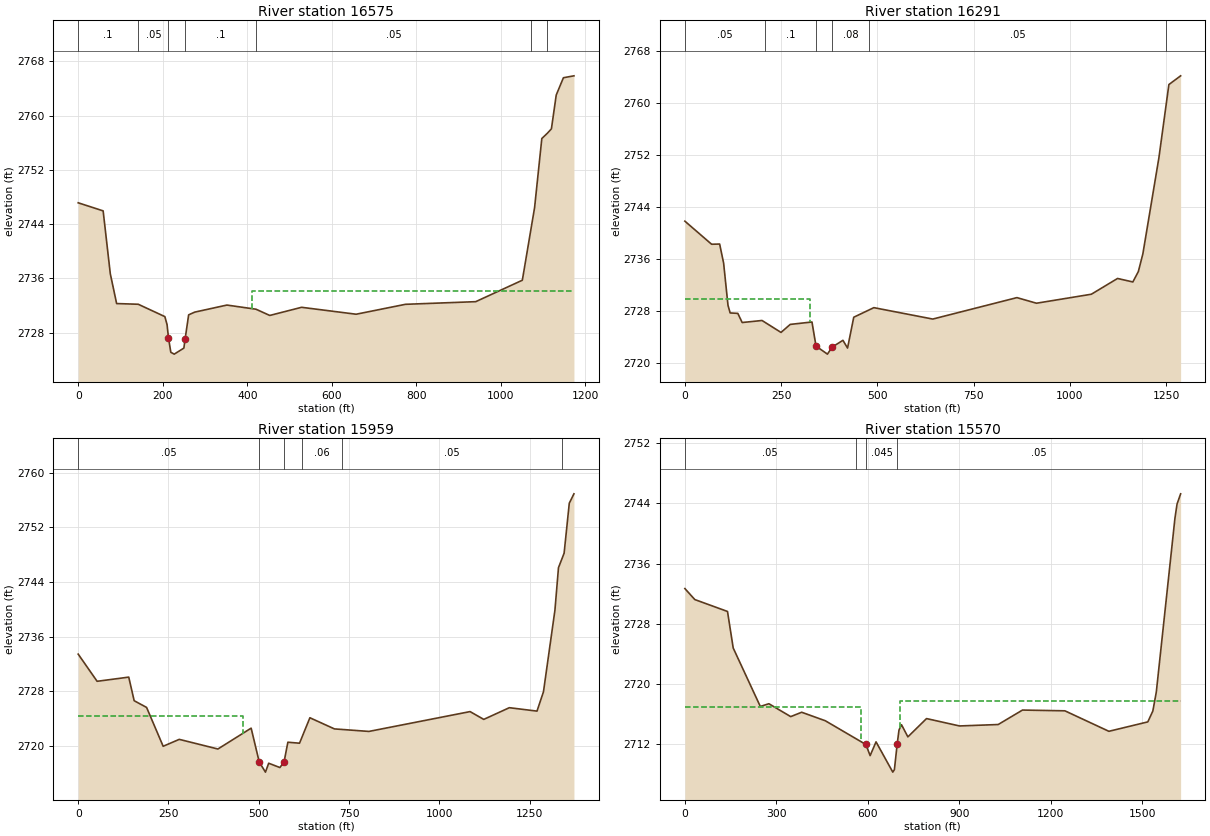
Type RM Length L Ch R = 1 ,16575   ,306.3,284.2,257.5
XS GIS Cut Line= 2
 2308510.1194105500541.2350965322307677.00617919 501366.66817899
#Sta/Elev= 30
       0 2747.14      59 2745.95    75.9  2736.7    90.9 2732.29     142 2732.19
     205 2730.37   210.2  2729.2   213.5 2727.28   219.1 2725.11   227.2 2724.84
     250 2725.73   253.1 2727.14   261.3 2730.63   275.7 2731.03   351.8 2732.07
   420.5 2731.46   453.2 2730.54   528.5 2731.74   657.5 2730.72   774.2 2732.18
   940.4 2732.57  1050.7 2735.73  1070.5 2743.03  1079.7 2746.43  1096.8 2756.61
  1110.1  2757.4  1119.5 2758.04  1130.9 2763.02  1147.9 2765.57  1172.8 2765.85
#Mann= 7 ,-1,0
       0      .1       0     142     .05       0   213.5    .045       0
   253.1      .1       0   420.5     .05       0  1070.5     .07       0
  1110.1     .05       0
#XS Ineff= 2 , 0
                             411         2734.13
Permanent Ineff=
       F       F
Bank Sta=213.5,253.1
XS Rating Curve= 0 ,0
Exp/Cntr=0.3,0.1

Type RM Length L Ch R = 1 ,16291   ,315.6,332.5,367.4
XS GIS Cut Line= 4
2308267.98251639500294.9871001712308119.38424681500425.573458282
2308087.86340175500745.2848867612307597.03881437501336.675979815
#Sta/Elev= 30
       0 2741.83    69.4 2738.29    90.3 2738.32   100.6  2735.4     112 2728.91
   117.6 2727.75   137.5 2727.68   148.8 2726.28   200.4 2726.59   249.7 2724.76
   273.6 2725.99   330.1 2726.36  340.65 2722.65   370.3 2721.43   382.3  2722.5
   410.5 2723.55   422.5 2722.36   438.6 2727.09   490.8 2728.56   643.8 2726.81
   862.5  2730.1   913.2 2729.24  1055.7 2730.62  1123.8 2733.04  1163.5  2732.5
  1177.8  2734.1  1189.5 2736.81  1231.1 2751.53  1257.1 2762.79  1287.6 2764.13
#Mann= 6 ,-1,0
       0     .05       0  207.82      .1       0  340.65    .045       0
   382.3     .08       0  477.82     .05       0 1249.09     .06       0
#XS Ineff= 2 , 0
          324.73 2729.94
Permanent Ineff=
       F       F
Bank Sta=340.65,382.3
XS Rating Curve= 0 ,0
Exp/Cntr(USF)=0,0
Exp/Cntr=0.3,0.1

Type RM Length L Ch R = 1 ,15959   ,375.4,388.3,417
XS GIS Cut Line= 2
     2308090.792      500115.1562307280.78907323501223.736856405
#Sta/Elev= 30
       0 2733.46    52.4 2729.49     140  2730.1     155 2726.65   189.4 2725.67
   235.3 2719.99   279.9    2721   386.9 2719.59     479 2722.64   501.4 2717.69
   518.6 2716.21   527.6 2717.51   558.6 2716.88   570.1 2717.69   580.7 2720.58
     613 2720.44   641.7 2724.16   709.6 2722.53   805.1 2722.16  1085.3 2725.06
  1123.2 2723.92  1194.1 2725.63  1270.7 2725.13  1288.6 2727.96  1320.3 2739.87
  1330.2 2746.11    1340 2747.43  1345.8 2748.23  1360.1 2755.53    1373  2756.9
#Mann= 6 ,-1,0
       0     .05       0   501.4    .045       0   570.1     .05       0
     620     .06       0     730     .05       0    1340     .06       0
#XS Ineff= 2 , 0
           455.1 2724.38
Permanent Ineff=
       F       F
Bank Sta=501.4,570.1
XS Rating Curve= 0 ,0
Exp/Cntr=0.3,0.1

Type RM Length L Ch R = 1 ,15570   ,360.3,374.9,347.9
BEGIN DESCRIPTION:
structure xs 4
END DESCRIPTION:
XS GIS Cut Line= 3
2308103.66997445499891.9399409762307389.90183254500325.006952611
2306840.95202158500894.662391588
#Sta/Elev= 30
       0  2732.7    32.6 2731.24   139.8 2729.66   158.5 2724.81   247.4 2717.05
   275.5 2717.41   347.1  2715.7   383.1 2716.28   460.6 2715.15   593.6    2712
   607.6 2710.52     627 2712.35   681.9 2708.33   687.2 2708.66   696.4 2712.08
   702.3 2713.92   710.6 2714.62   731.4 2713.01   792.6 2715.44   900.8 2714.46
  1027.6 2714.65  1107.3 2716.57  1246.4 2716.47  1390.7 2713.75  1518.4    2715
  1534.9 2716.45  1546.3 2718.98  1607.3 2742.02  1614.2 2743.91    1626 2745.28
#Mann= 4 ,-1,0
       0     .05       0     560     .03       0   593.6    .045       0
   696.4     .05       0
#XS Ineff= 2 , 0
          577.88 2717.02  705.07         2717.82
Permanent Ineff=
       F       F
Bank Sta=593.6,696.4
XS Rating Curve= 0 ,0
Exp/Cntr=0.5,0.3