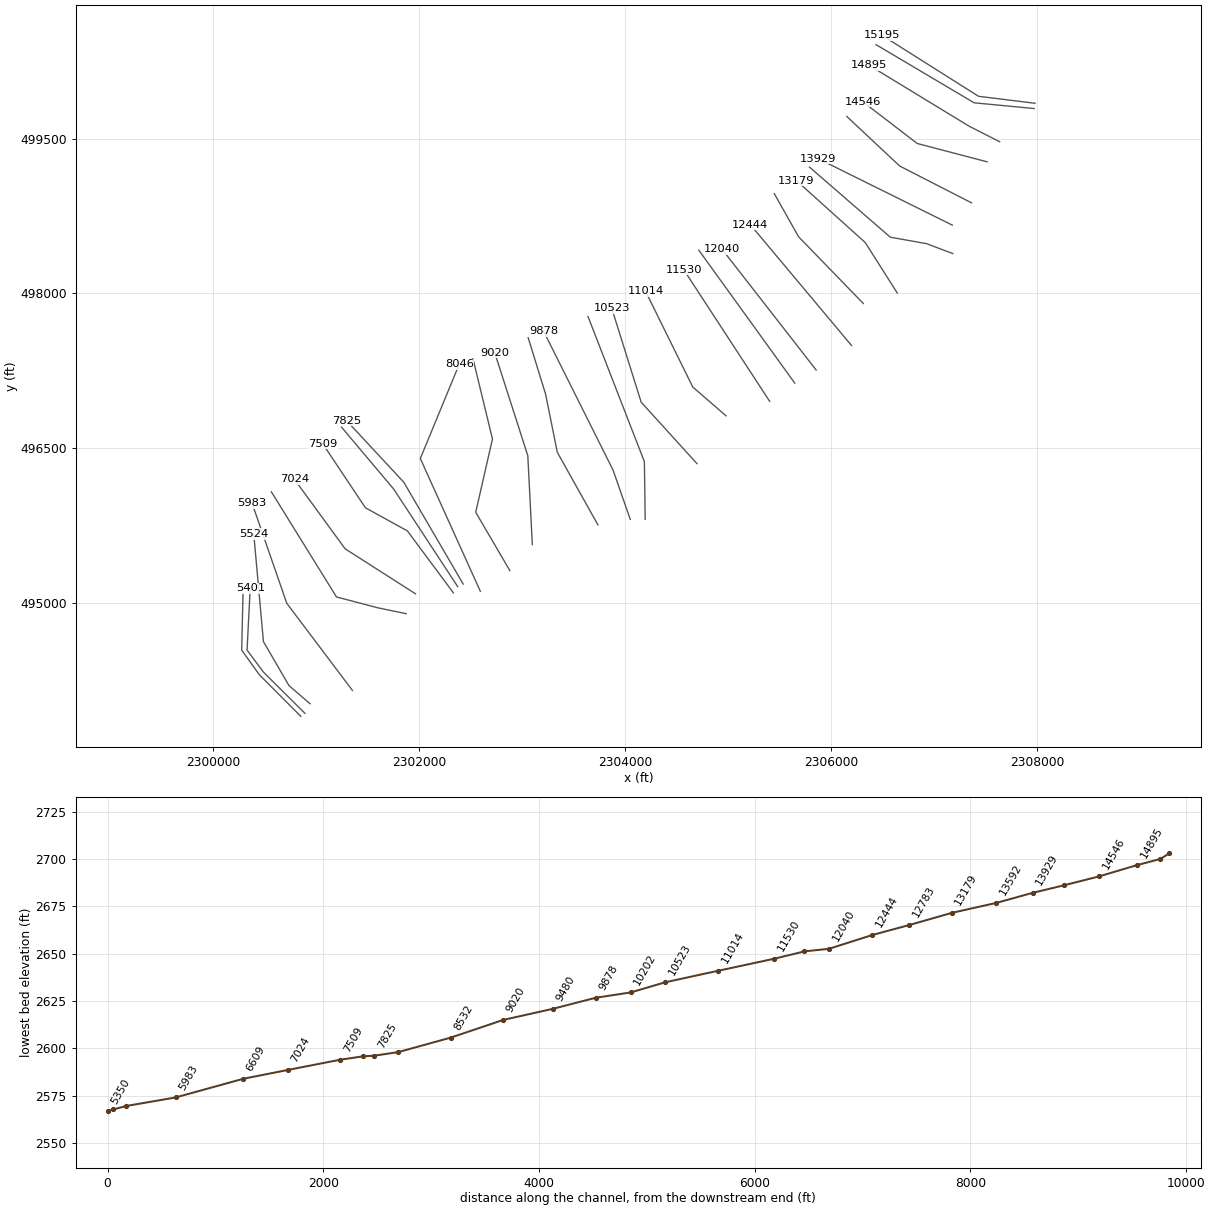
HEC-RAS study GALFRDRN.prj: GALFRDRN

--- GALFRDRN.g01 (geometry) --- (continued)

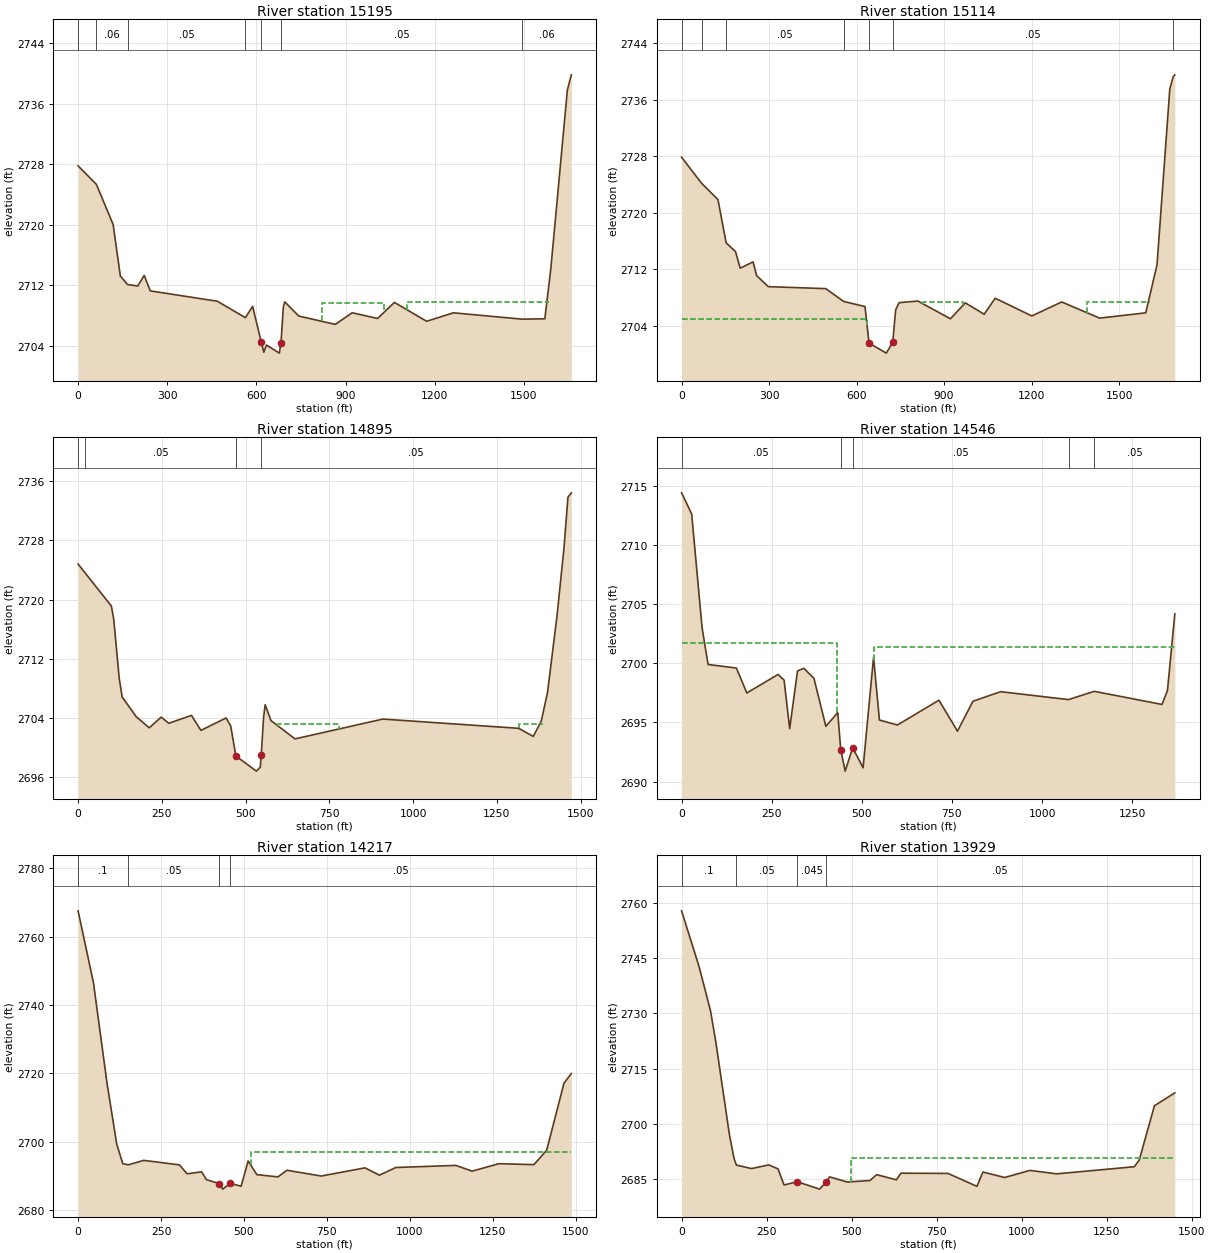
Type RM Length L Ch R = 1 ,15195   ,78.1,81.8,82.1
BEGIN DESCRIPTION:
structure xs 3
END DESCRIPTION:
XS GIS Cut Line= 3
2307981.29292559499846.1903062042307433.43061858499913.734974192
2306496.81122247500505.126067246
#Sta/Elev= 30
       0 2727.77    61.6 2725.33     118 2720.01   142.2 2713.21   166.4 2712.08
     201 2711.89   222.5 2713.29   242.9 2711.24   468.6 2709.87     563  2707.7
   587.3  2709.2   616.3 2704.48     625 2703.13   633.9 2704.08   677.2 2703.01
  682.812704.413   690.7 2709.07   695.4 2709.79   742.7 2707.91   865.6 2706.81
   922.5 2708.35  1007.8 2707.59  1064.4 2709.72  1172.8 2707.22  1262.7 2708.34
  1494.9  2707.5  1570.6 2707.55  1590.6 2714.13  1646.3 2737.78  1659.7 2739.81
#Mann= 7 ,-1,0
       0     .05       0    61.6     .06       0   166.4     .05       0
     563     .03       0   616.3    .045       0  682.81     .05       0
  1494.9     .06       0
#XS Ineff= 4 ,-1
       0   592.3 2708.15  706.81     821 2706.67     821    1031 2709.66
 1105.35 1582.99 2709.75
Permanent Ineff=
       F       F       F       F
Bank Sta=616.3,682.81
XS Rating Curve= 0 ,0
Exp/Cntr(USF)=0,0
Exp/Cntr=0.5,0.3

Type RM Length L Ch R = 1 ,15114   ,218.8,218.1,217.5
BEGIN DESCRIPTION:
structure xs 2
END DESCRIPTION:
XS GIS Cut Line= 3
2307972.28696986499795.1565570572307389.90183254 499850.69328407
2306438.27251021500415.066509929
#Sta/Elev= 30
       0 2727.86    68.4 2724.17   124.7 2721.85   152.8 2715.71   184.9 2714.48
     201 2712.13   245.2 2713.02   257.3 2711.07   297.5 2709.51   494.3 2709.23
   555.9 2707.41   628.9 2706.69   642.8 2701.51     702 2700.09  724.072701.625
   734.1 2706.22   745.7 2707.24   810.3 2707.47   921.9 2704.96     973 2707.21
  1037.7  2705.6  1075.3 2707.87  1200.9 2705.36  1303.5 2707.34  1433.4 2705.05
  1591.6  2705.8  1630.3 2712.61  1674.1 2737.52  1685.7 2739.25  1691.4 2739.53
#Mann= 7 ,-1,0
       0     .05       0    68.4     .06       0   152.8     .05       0
   555.9     .03       0   642.8    .045       0  724.07     .05       0
  1685.7     .06       0
#XS Ineff= 4 ,-1
     .28  636.082704.928  731.32  827.49 2704.18  827.49  966.42 2707.34
 1390.31 1606.31 2707.39
Permanent Ineff=
       F       F       F       F
Bank Sta=642.8,724.07
XS Rating Curve= 0 ,0
Exp/Cntr(USF)=0,0
Exp/Cntr=0.5,0.3

Type RM Length L Ch R = 1 ,14895   ,330.4,349.1,357.3
XS GIS Cut Line= 3
2307637.58990409499472.9565681092307343.37106126499622.542405531
2306367.54152329500216.627535184
#Sta/Elev= 30
       0 2724.81    99.4 2719.13   106.4 2717.37   122.7 2709.39   131.7 2706.82
   173.8 2704.15   212.4 2702.66   248.1  2704.1   270.8 2703.27   338.5 2704.34
   366.6 2702.31     442 2703.99   455.6 2702.91   471.1 2698.85   532.2  2696.8
   543.9 2697.33   546.8 2698.95   553.9 2704.12   558.6 2705.78   575.9 2703.63
   647.6 2701.16   909.8 2703.84  1315.3 2702.59  1358.9 2701.49  1382.8 2703.57
  1401.5 2707.46  1429.6 2717.73  1450.5 2726.93  1462.4 2733.85  1472.5 2734.44
#Mann= 4 ,-1,0
       0      .1       0      20     .05       0   471.1    .045       0
   546.8     .05       0
#XS Ineff= 2 ,-1
  595.83  779.72 2703.13 1316.06 1388.17 2703.19
Permanent Ineff=
       F       F
Bank Sta=471.1,546.8
XS Rating Curve= 0 ,0
Exp/Cntr=0.3,0.1

Type RM Length L Ch R = 1 ,14546   ,336.3,329.6,322.7
XS GIS Cut Line= 3
      2307515.24      499278.1442306837.53654765499455.932224493
2306307.93160103 499862.47923665
#Sta/Elev= 30
       0 2714.42      28 2712.63    56.9 2702.99    73.5  2699.9     152  2699.6
     181 2697.49   267.8 2699.06   284.4 2698.57   299.8 2694.47   321.6 2699.35
   339.1 2699.58   367.1 2698.73   400.2 2694.67   433.2 2695.83   441.5  2692.7
   453.8 2690.88   474.6 2692.86   503.5 2691.16   532.5 2700.51   548.8  2695.2
   598.7 2694.78   713.9 2696.88   765.3 2694.26   808.2 2696.79   885.1  2697.6
  1073.4 2696.93  1144.7 2697.63  1332.7 2696.52  1347.8  2697.7  1368.3 2704.18
#Mann= 5 ,-1,0
       0     .05       0   441.5    .045       0   474.6     .05       0
  1073.4     .06       0  1144.7     .05       0
#XS Ineff= 2 , 0
          432.26 2701.69  533.33         2701.36
Permanent Ineff=
       F       F
Bank Sta=441.5,474.6
XS Rating Curve= 0 ,0
Exp/Cntr=0.3,0.1

Type RM Length L Ch R = 1 ,14217   ,285.1,288,289
XS GIS Cut Line= 3
2307364.39949829 498879.999173662306667.92438137499236.787301686
2306153.91559366499718.226402932
#Sta/Elev= 30
       0 2767.51    46.5 2746.39    87.2 2717.13   116.6 2699.24   134.8 2693.55
   151.7 2693.23     198 2694.53   305.9 2693.21   328.3  2690.6   372.5 2691.18
   386.8  2688.9     426 2687.73   436.2 2686.12   458.7 2687.81   491.4 2686.96
   512.6 2694.35     539 2690.35   602.5  2689.7   629.5 2691.64   732.8 2689.95
     865 2692.34   908.3  2690.2   957.6 2692.44  1138.4 2693.06  1187.8 2691.38
  1268.8 2693.56  1374.1 2693.28  1412.5  2697.5  1464.7 2717.09  1486.8 2719.95
#Mann= 4 ,-1,0
       0      .1       0   151.7     .05       0     426    .045       0
   458.7     .05       0
#XS Ineff= 2 , 0
                          521.04          2697.1
Permanent Ineff=
       F       F
Bank Sta=426,458.7
XS Rating Curve= 0 ,0
Exp/Cntr=0.3,0.1

Type RM Length L Ch R = 1 ,13929   ,316.6,336.8,346.4
XS GIS Cut Line= 2
2307178.26187284498663.4081200952305878.40226222499307.333954918
#Sta/Elev= 30
       0 2757.96    51.4 2742.77    85.1 2730.71   100.5 2722.34   140.7 2696.98
   154.1 2690.55   161.1 2688.71   205.9 2687.76   256.3 2688.76   283.5 2687.69
   301.4 2683.28   340.2 2684.18   405.9 2682.16   423.8 2683.98   435.3 2685.49
   487.2  2684.1   553.7  2684.5   573.7  2686.1   631.7 2684.69   645.1  2686.5
   783.5 2686.44   868.6 2682.91   886.2 2686.82   950.1 2685.33  1024.6 2687.26
  1103.3 2686.32  1331.3 2688.26    1346  2690.1  1390.6 2704.87  1450.6 2708.39
#Mann= 4 ,-1,0
       0      .1       0   161.1     .05       0   340.2    .045       0
   423.8     .05       0
#XS Ineff= 2 , 0
                          498.92         2690.74
Permanent Ineff=
       F       F
Bank Sta=340.2,423.8
XS Rating Curve= 0 ,0
Exp/Cntr(USF)=0,0
Exp/Cntr=0.3,0.1

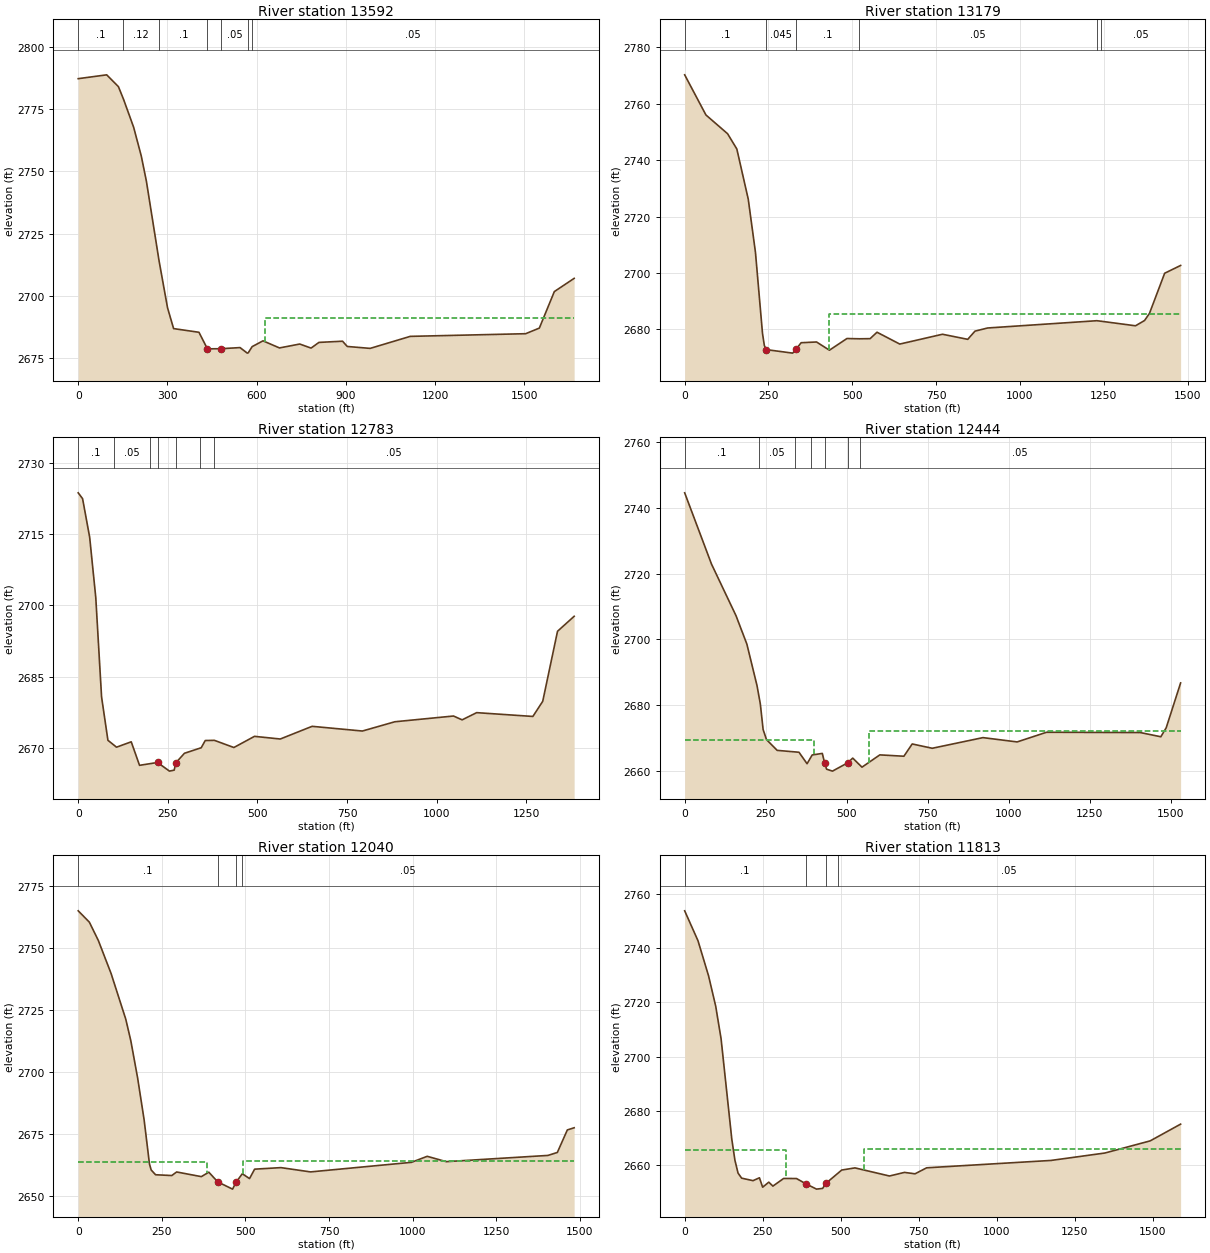
Type RM Length L Ch R = 1 ,13592   ,444.3,413,373.1
XS GIS Cut Line= 4
     2307182.572      498387.244 2306929.0970976498483.289005459
2306576.36383143498546.3306955822305791.68857493499226.621314395
#Sta/Elev= 30
       0 2787.37    95.8 2788.92   135.2 2784.16   152.3 2779.11   186.5 2767.78
   212.2 2756.18   229.3 2746.09     272 2713.96   300.4 2695.11   320.8 2686.73
   406.1 2685.24   434.5 2678.58   479.2 2678.62   544.2 2679.08   568.6 2676.85
   571.7 2676.95   584.9 2679.46   621.4  2681.8   676.9 2678.94     745 2680.51
   783.2 2678.88   809.6 2681.17     889 2681.65   904.9 2679.53   981.8 2678.76
  1116.7  2683.6  1504.9 2684.67  1550.8 2686.93  1601.3 2701.64  1667.9 2706.96
#Mann= 7 ,-1,0
       0      .1       0   152.3     .12       0     272      .1       0
   434.5    .045       0   479.2     .05       0   571.7      .1       0
   584.9     .05       0
#XS Ineff= 2 , 0
                          627.65         2691.14
Permanent Ineff=
       F       F
Bank Sta=434.5,479.2
XS Rating Curve= 0 ,0
Exp/Cntr=0.3,0.1

Type RM Length L Ch R = 1 ,13179   ,383,395.9,393.8
XS GIS Cut Line= 3
2306643.52649092498005.0816719542306333.16925085498494.229376832
2305664.26869298499096.492498846
#Sta/Elev= 30
       0 2770.24    63.4 2756.01     128 2749.36   155.6 2743.95   189.6 2726.19
   211.2 2707.27   232.2 2678.52   237.7 2674.26  243.72 2672.83   322.2 2671.59
   331.7 2672.89   347.4 2675.28   393.3 2675.54   431.8 2672.63   484.1 2676.77
   521.2 2676.67   553.2 2676.72   573.7    2679   641.6  2674.8     769 2678.28
   844.4 2676.48   865.9 2679.38   903.6  2680.5  1229.3 2683.08  1241.3 2682.91
  1344.9 2681.28  1371.9 2683.16  1386.5 2685.68  1431.8 2699.91  1479.4 2702.67
#Mann= 6 ,-1,0
       0      .1       0  243.72    .045       0   331.7      .1       0
   521.2     .05       0  1229.3     .06       0  1241.3     .05       0
#XS Ineff= 2 , 0
                          430.11         2685.37
Permanent Ineff=
       F       F
Bank Sta=243.72,331.7
XS Rating Curve= 0 ,0
Exp/Cntr=0.3,0.1

Type RM Length L Ch R = 1 ,12783   ,341,339.4,332
XS GIS Cut Line= 3
 2306314.6161138497902.343648359 2305685.7002052498550.772461048
2305450.04436355498969.549402577
#Sta/Elev= 30
       0 2723.71    12.2 2722.48      32 2714.35      49 2701.67    65.2 2680.74
    82.9 2671.62   106.9 2670.17     148  2671.3   171.1 2666.35   221.3 2666.95
   254.7 2665.13   267.8 2665.34   272.5 2666.89   296.5 2668.89   343.2 2670.05
   354.5 2671.57     380 2671.61   434.4  2670.1   491.9 2672.45   563.8 2671.89
   652.7 2674.56     793 2673.57   883.5 2675.52  1047.2 2676.73  1071.3 2675.92
  1111.8 2677.44  1268.7 2676.64  1296.2 2679.82  1337.5 2694.57  1383.9 2697.72
#Mann= 7 ,-1,0
       0      .1       0     100     .05       0     200      .1       0
   221.3    .045       0   272.5     .05       0     340     .03       0
     380     .05       0
Bank Sta=221.3,272.5
XS Rating Curve= 0 ,0
Exp/Cntr(USF)=0,0
Exp/Cntr=0.3,0.1

Type RM Length L Ch R = 1 ,12444   ,403.9,403.9,400.1
XS GIS Cut Line= 2
     2306199.419      497495.6892305216.96253067498668.550081711
#Sta/Elev= 30
       0 2744.54    82.9 2722.84   158.5 2707.15   191.9 2698.53   223.1 2685.94
   233.4 2680.33     242 2672.56   252.4  2669.5   285.4 2666.22   352.6 2665.65
   377.6 2662.16   393.3 2664.82   424.6  2665.3   432.1 2662.25   437.8  2660.5
   455.9 2659.91   502.9 2662.43   518.5 2663.87     547 2661.11     602 2664.85
   676.3 2664.44   701.9 2668.17   763.8 2666.86   920.3  2670.1  1025.6 2668.79
  1116.4 2671.73  1405.6 2671.64  1468.9 2670.36  1485.5 2673.08    1530 2686.73
#Mann= 7 ,-1,0
       0      .1       0     230     .05       0     340      .1       0
     390     .07       0   432.1    .045       0   502.9     .07       0
     540     .05       0
#XS Ineff= 2 , 0
          400.23  2669.4  567.74         2672.04
Permanent Ineff=
       F       F
Bank Sta=432.1,502.9
XS Rating Curve= 0 ,0
Exp/Cntr=0.3,0.1

Type RM Length L Ch R = 1 ,12040   ,228.4,226.7,225.2
XS GIS Cut Line= 2
     2305856.642      497257.0362304945.24953463498426.935616895
#Sta/Elev= 30
       0 2765.05    33.3 2760.48    60.3 2753.03    98.4 2739.69   142.2 2721.27
   157.4  2712.5   177.7 2697.47   197.1 2680.59   213.1 2662.73   218.2 2660.33
   231.3  2658.4   279.8 2658.08   294.3 2659.52   368.1 2657.64   390.6 2659.43
   417.3  2655.5   461.6 2652.59   471.7 2655.32   490.7  2658.8   512.3 2656.85
   527.5 2660.66   606.1 2661.28   694.8 2659.55   996.6 2663.42  1043.6 2665.85
  1100.6 2663.69  1404.7 2666.21  1432.7 2667.41  1462.6  2676.5    1483 2677.39
#Mann= 4 ,-1,0
       0      .1       0   417.3    .045       0   471.7      .1       0
     490     .05       0
#XS Ineff= 2 , 0
           385.8 2663.57  493.97         2663.92
Permanent Ineff=
       F       F
Bank Sta=417.3,471.7
XS Rating Curve= 0 ,0
Exp/Cntr=0.3,0.1

Type RM Length L Ch R = 1 ,11813   ,285.5,283.3,280.1
XS GIS Cut Line= 2
  2305648.371191 497130.529496252304718.12191384498419.429097133
#Sta/Elev= 30
       0 2753.69    42.7 2742.67    76.5 2729.78    99.5 2718.55   116.7 2706.56
     151 2669.64   161.1 2661.84     171 2657.15   182.5 2655.27   219.1 2654.35
   239.6 2655.41   249.9 2651.94   269.6  2653.8   282.8 2652.34   317.2 2655.16
   358.4 2655.13   388.22653.207   422.6 2651.23   442.3  2651.5   452.2 2653.32
   503.4 2658.26   545.9 2659.05   656.5 2656.06   704.3 2657.39   738.3 2656.87
   775.6 2659.08  1173.9 2661.79  1346.8 2664.52  1491.9 2668.99  1589.5 2675.16
#Mann= 4 ,-1,0
       0      .1       0   388.2    .045       0   452.2     .07       0
     490     .05       0
#XS Ineff= 2 , 0
          323.61 2665.48   574.2         2666.08
Permanent Ineff=
       F       F
Bank Sta=388.2,452.2
XS Rating Curve= 0 ,0
Exp/Cntr(USF)=0,0
Exp/Cntr=0.3,0.1

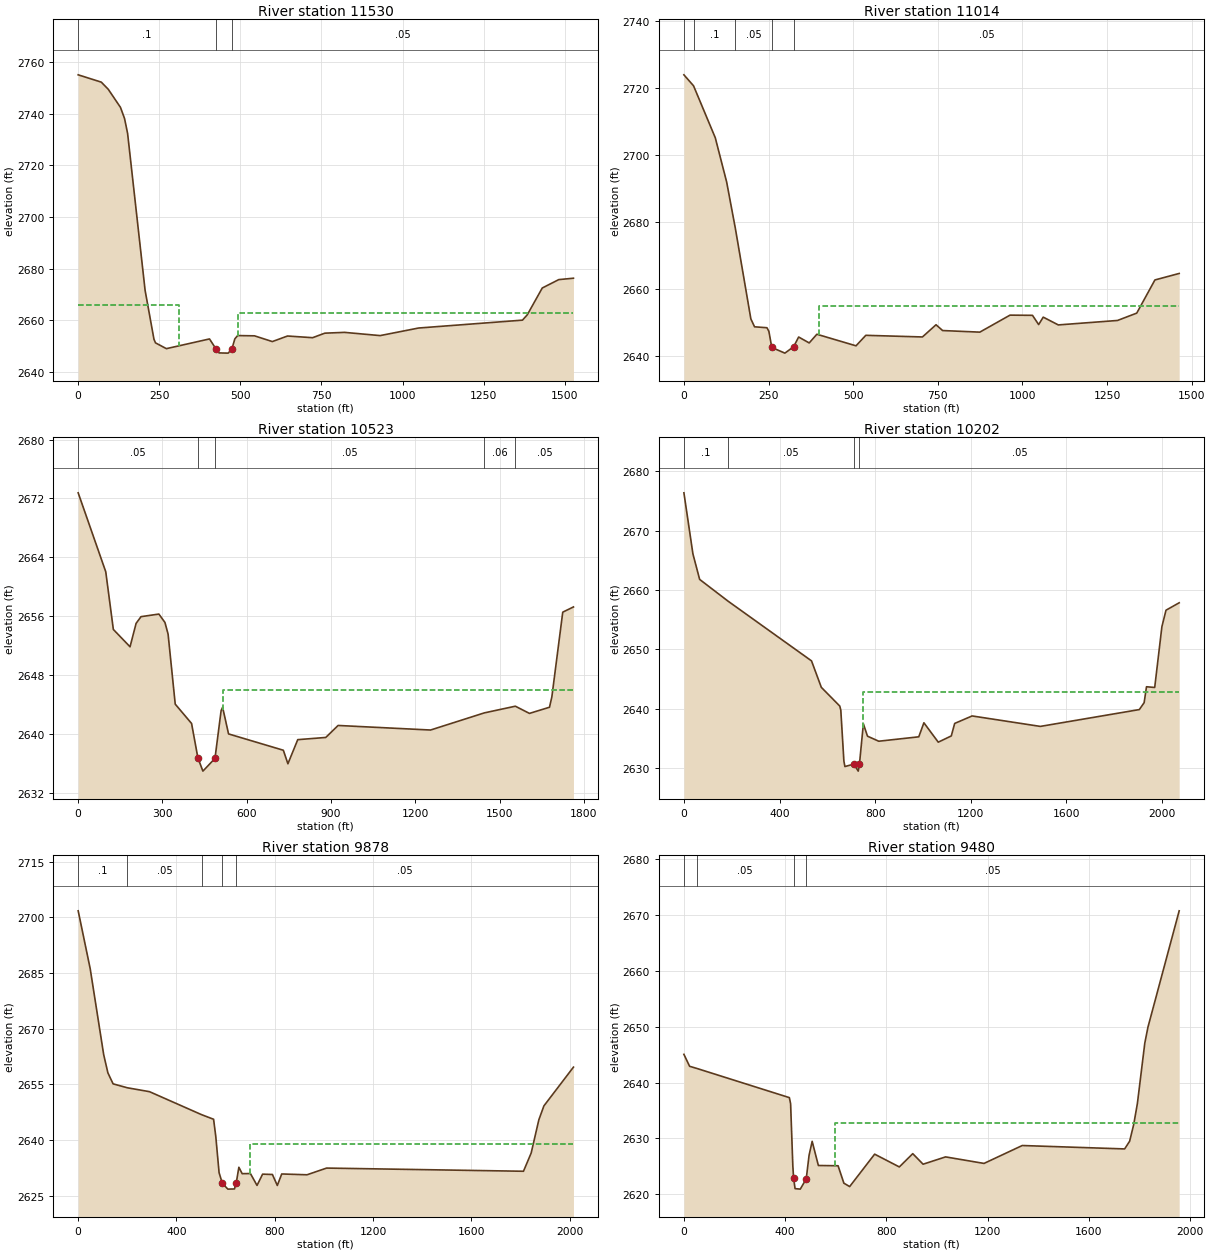
Type RM Length L Ch R = 1 ,11530   ,504,516.4,528.7
XS GIS Cut Line= 2
     2305404.962      496953.5542304570.27459366498232.238417688
#Sta/Elev= 30
       0 2754.97    71.2 2752.15    92.8 2749.37   130.4 2742.38   142.9  2738.1
   152.4  2732.3   206.3 2671.62   233.6 2652.71   238.4 2651.28     272 2649.04
   404.9  2652.8   424.7 2648.97   434.2 2647.39   462.7 2647.31   474.3 2649.05
     483 2652.82   491.6  2654.1   543.7    2654   598.6 2651.78   645.4 2653.93
   722.8 2653.28   760.4 2655.03     821 2655.34     931 2654.09  1049.4 2657.02
  1369.9 2660.07  1384.7 2662.15  1430.9 2672.51  1481.7 2675.75    1527 2676.29
#Mann= 3 ,-1,0
       0      .1       0   424.7    .045       0   474.3     .05       0
#XS Ineff= 2 , 0
          309.68 2666.03  491.55         2662.72
Permanent Ineff=
       F       F
Bank Sta=424.7,474.3
XS Rating Curve= 0 ,0
Exp/Cntr=0.3,0.1

Type RM Length L Ch R = 1 ,11014   ,495.2,490.8,483.5
XS GIS Cut Line= 3
2304981.73466549496812.6230048112304659.02125177497091.807632497
2304200.43232209498021.432086168
#Sta/Elev= 30
       0 2723.98    28.5  2720.7    92.6 2705.24   126.3 2692.01   151.8  2678.3
   197.8 2651.19   208.7 2648.84   245.4 2648.56   251.1 2647.47   259.6 2642.68
   298.3 2640.99  324.152642.892     339 2645.79   370.2 2644.03   392.8 2646.62
   508.5 2643.17   537.4  2646.3   704.7 2645.81   744.9 2649.45   764.4 2647.72
   874.3 2647.25   963.5 2652.32  1029.9 2652.26  1048.1  2649.5  1061.6 2651.72
  1106.2  2649.4  1281.1 2650.73  1337.9 2652.92  1391.6 2662.81  1463.3 2664.75
#Mann= 5 ,-1,0
       0     .12       0    28.5      .1       0   151.8     .05       0
   259.6    .045       0  324.15     .05       0
#XS Ineff= 2 , 0
                          398.16         2655.07
Permanent Ineff=
       F       F
Bank Sta=259.6,324.15
XS Rating Curve= 0 ,0
Exp/Cntr=0.3,0.1

Type RM Length L Ch R = 1 ,10523   ,333.6,320.4,308.4
XS GIS Cut Line= 3
      2304699.62      496348.5152304158.10951811496944.701662095
2303871.74852193497858.548414632
#Sta/Elev= 30
       0 2672.76    98.2 2662.02   125.2 2654.18   184.6 2651.82   206.2 2655.01
   223.8 2655.92   287.3 2656.27   308.9 2655.13   320.1 2653.54   345.5 2644.02
   403.7 2641.39  426.122636.721     444 2634.91     487 2636.64   508.8 2643.13
   514.2 2643.59   535.3 2639.97   730.4 2637.75   746.6 2635.91   781.6 2639.19
   881.4 2639.49   925.3 2641.12  1254.4  2640.5  1445.7 2642.83  1556.2 2643.74
  1606.5 2642.76  1677.8  2643.6  1686.2    2645    1725 2656.53  1763.1 2657.24
#Mann= 5 ,-1,0
       0     .05       0  426.12    .045       0     487     .05       0
  1445.7     .06       0  1556.2     .05       0
#XS Ineff= 2 , 0
                          516.13         2645.99
Permanent Ineff=
       F       F
Bank Sta=426.12,487
XS Rating Curve= 0 ,0
Exp/Cntr=0.3,0.1

Type RM Length L Ch R = 1 ,10202   ,321.7,324.8,328.4
XS GIS Cut Line= 3
2304197.00291772495807.4309204152304189.18807214496367.435629552
2303641.87672949497776.624604829
#Sta/Elev= 30
       0 2676.34   37.75 2666.06   65.85 2661.78  185.77 2658.09   533.8 2648.08
   574.8 2643.63  652.04 2640.48  656.33 2639.78  669.21 2631.23   673.5 2630.31
  710.54 2630.72  729.28 2629.54  734.43 2630.77  750.74  2637.5   767.9 2635.42
   815.1 2634.57  982.46 2635.31 1003.91 2637.67 1063.99 2634.41 1118.52 2635.46
 1132.65 2637.56 1205.59 2638.82 1490.93 2637.06 1905.04 2639.89 1925.19 2641.05
 1935.08 2643.73 1969.41 2643.61 1999.45 2653.82 2016.61  2656.6  2071.8 2657.85
#Mann= 4 ,-1,0
       0      .1       0  185.77     .05       0  710.54    .045       0
  734.43     .05       0
#XS Ineff= 2 , 0
                          748.85         2642.83
Permanent Ineff=
       F       F
Bank Sta=710.54,734.43
XS Rating Curve= 0 ,0
Exp/Cntr=0.3,0.1

Type RM Length L Ch R = 1 ,9878    ,394.8,397.5,399.6
XS GIS Cut Line= 3
2304052.20357349 495807.044498712303885.33154786496285.244930362
2303210.37156361497635.164898878
#Sta/Elev= 30
       0  2701.8    48.9  2686.2   103.9 2662.97   120.9  2658.1   142.1 2655.12
   199.6 2654.07   290.3 2653.01   502.2 2646.81   551.1 2645.57   560.1 2640.91
   573.5 2631.16   586.9 2628.25   609.3 2626.72   636.1 2626.77   643.2 2628.36
     654 2632.62   667.4 2630.89   701.1 2630.92   727.9 2627.72   750.6 2630.76
   790.5 2630.67   810.5  2627.7   828.4 2630.81   931.3 2630.59  1011.2  2632.4
  1812.3 2631.54  1843.6 2636.45  1874.9 2645.43  1895.4 2649.17  2015.7 2659.63
#Mann= 5 ,-1,0
       0      .1       0   199.6     .05       0   502.2      .1       0
   586.9    .045       0   643.2     .05       0
#XS Ineff= 2 , 0
                          698.92         2638.93
Permanent Ineff=
       F       F
Bank Sta=586.9,643.2
XS Rating Curve= 0 ,0
Exp/Cntr(USF)=0,0
Exp/Cntr=0.3,0.1

Type RM Length L Ch R = 1 ,9480    ,477.3,459.9,440.8
BEGIN DESCRIPTION:
IFA placed to uncross 500 and 101 profiles
END DESCRIPTION:
XS GIS Cut Line= 4
     2303738.333      495753.5422303344.45604255496457.553915743
2303229.90591807497023.8205688552303061.26052752497571.093397838
#Sta/Elev= 30
       0 2645.05    22.5 2642.91      50 2642.54   416.7 2637.29   421.6  2636.2
   430.4 2625.06   433.4 2622.86   439.2 2620.97   459.8 2620.88   483.3 2622.71
   494.6 2626.95   506.8 2629.45   531.3 2625.12   609.2 2625.07   632.1 2621.95
     655 2621.34   753.7 2627.15   851.2 2624.86   904.3 2627.24   945.1 2625.35
    1034 2626.66  1185.9 2625.49  1336.9  2628.7  1741.6 2628.09  1761.3 2629.47
  1777.3 2632.45  1791.9 2636.22  1821.2 2647.06  1833.7 2649.93  1957.1 2670.79
#Mann= 4 ,-1,0
       0      .1       0      50     .05       0   433.4    .045       0
   483.3     .05       0
#XS Ineff= 2 , 0
                          596.01         2632.68
Permanent Ineff=
       F       F
Bank Sta=433.4,483.3
XS Rating Curve= 0 ,0
Exp/Cntr=0.3,0.1

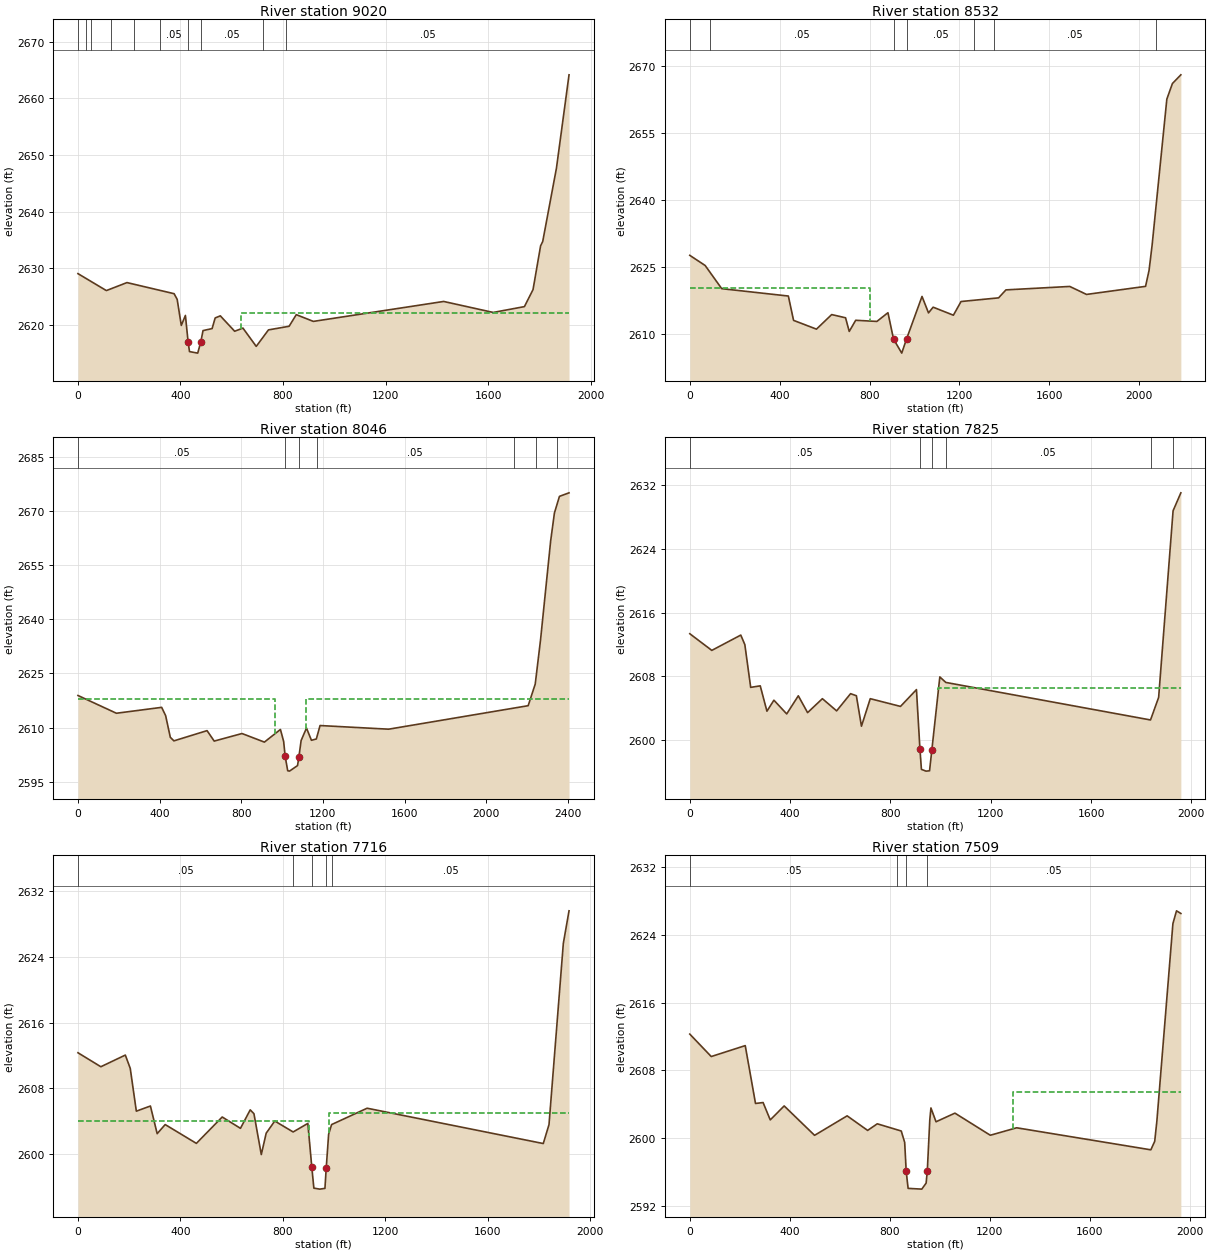
Type RM Length L Ch R = 1 ,9020    ,497.6,488.7,476.6
XS GIS Cut Line= 3
     2303101.508      495562.5482303057.70188031496425.382465042
2302736.02753312497426.872403436
#Sta/Elev= 30
       0 2629.04   110.8 2626.05   191.2 2627.46   375.1  2625.5   387.1 2624.49
   403.1  2619.9   419.2 2621.66   429.8 2616.94   435.2 2615.28   467.2 2615.01
   479.2 2616.99   487.9 2618.99   523.3 2619.34   535.3 2621.22   555.3 2621.59
   611.4 2618.87   643.5 2619.43   695.5  2616.2   743.2 2619.11   823.7 2619.75
   851.7  2621.8   918.3 2620.61  1426.7 2624.13    1620 2622.19  1741.8 2623.22
  1775.4 2626.23  1804.8 2633.93  1813.2 2634.72  1866.7 2647.66  1915.8 2664.13
#Mann= 10 ,-1,0
       0      .1       0      30     .05       0      50      .1       0
     130     .05       0     220     .07       0     320     .05       0
   429.8    .045       0   479.2     .05       0     720     .03       0
     810     .05       0
#XS Ineff= 2 , 0
                          636.62         2622.14
Permanent Ineff=
       F       F
Bank Sta=429.8,479.2
XS Rating Curve= 0 ,0
Exp/Cntr=0.3,0.1

Type RM Length L Ch R = 1 ,8532    ,453.4,485.5,512.4
XS GIS Cut Line= 4
2302883.11621478495310.5125387192302552.10918185495876.322521021
2302714.53941529496587.8126984812302525.76526889497365.858171862
#Sta/Elev= 30
       0 2627.57    68.4 2625.29   142.1 2620.09   438.7 2618.44   461.9 2612.98
   563.8 2611.01   631.6 2614.28   693.3 2613.56   709.7  2610.5   738.5    2613
   832.8 2612.74   882.1  2614.7   906.8 2608.79   943.4 2605.63   964.9 2608.82
  1033.7 2618.35  1062.6 2614.66  1083.1 2615.94  1173.4 2614.14  1207.4 2617.21
  1374.5 2618.03  1407.3 2619.82  1691.3 2620.59    1766  2618.8  2028.8 2620.61
  2044.3 2624.18  2057.9 2629.84  2123.5 2662.62  2148.2 2666.11  2185.9 2668.07
#Mann= 7 ,-1,0
       0      .1       0      90     .05       0   906.8    .045       0
   964.9     .05       0 1265.52     .07       0 1355.52     .05       0
 2075.32      .1       0
#XS Ineff= 2 , 0
          801.41 2620.14
Permanent Ineff=
       F       F
Bank Sta=906.8,964.9
XS Rating Curve= 0 ,0
Exp/Cntr=0.3,0.1

Type RM Length L Ch R = 1 ,8046    ,218.2,221.1,224.5
BEGIN DESCRIPTION:
structure xs 4
END DESCRIPTION:
XS GIS Cut Line= 3
2302597.05346781495108.9000513142302014.48798667496397.929467841
2302392.40495615497314.260413699
#Sta/Elev= 30
       0 2618.91   188.3    2614   410.1 2615.63   429.5 2613.34   452.4 2607.35
     470 2606.36   632.4 2609.19   667.5  2606.3   803.6 2608.39   913.3 2606.02
   991.9 2609.51  1007.6 2606.22 1015.19 2602.05  1027.5  2598.1  1036.2 2597.99
  1075.7 2599.52 1082.55 2602.01  1093.3 2606.45  1119.6 2609.91  1143.7 2606.52
  1167.8 2606.88    1186  2610.6  1521.9 2609.59  2205.6 2616.09  2240.2 2622.07
  2266.1 2634.23  2315.8 2661.69  2334.3  2669.4  2358.8 2673.99  2405.8 2674.97
#Mann= 7 ,-1,0
       0     .05       0 1015.19    .045       0 1082.55    .025       0
    1170     .05       0 2134.56     .07       0 2244.56     .05       0
 2344.56      .1       0
#XS Ineff= 2 , 0
          963.38 2617.81  1116.9         2618.07
Permanent Ineff=
       F       F
Bank Sta=1015.19,1082.55
XS Rating Curve= 0 ,0
Exp/Cntr=0.5,0.3

Type RM Length L Ch R = 1 ,7825    ,106.2,108.8,110.9
BEGIN DESCRIPTION:
structure xs 3
END DESCRIPTION:
XS GIS Cut Line= 3
2302430.61823049495179.4739420672301853.56995582496168.461302986
2301299.87045527496763.855043033
#Sta/Elev= 30
       0 2613.36    87.8 2611.27   203.3 2613.19   219.5 2611.99   242.8 2606.63
   280.9 2606.82   307.6 2603.64   335.4 2605.02   386.4  2603.3   432.7 2605.57
   469.7 2603.46   528.7 2605.21   585.5 2603.68   641.1 2605.84   664.2 2605.58
   684.5 2601.76   719.6 2605.21   840.2 2604.24   903.8 2606.35  917.692598.886
   923.6 2596.34   941.8 2596.12     956 2596.16   965.2 2598.78     997 2607.94
  1020.8 2607.25  1837.1 2602.54  1869.5 2605.37  1927.1 2628.79  1958.1 2631.04
#Mann= 6 ,-1,0
       0     .05       0  917.69    .045       0   965.2    .025       0
  1020.8     .05       0  1837.1     .07       0  1927.1     .05       0
#XS Ineff= 2 , 0
          891.39 2604.06   991.5         2606.59
Permanent Ineff=
       F       F
Bank Sta=917.69,965.2
XS Rating Curve= 0 ,0
Exp/Cntr(USF)=0,0
Exp/Cntr=0.5,0.3

Type RM Length L Ch R = 1 ,7716    ,184.6,207.2,227.6
BEGIN DESCRIPTION:
structure xs 2
END DESCRIPTION:
XS GIS Cut Line= 3
2302377.24960393495154.4573983682301756.83932018496100.082750207
2301249.83736787496702.147568574
#Sta/Elev= 30
       0 2612.33    89.4 2610.63     185 2612.05   204.2 2610.43     228 2605.22
     283 2605.85   309.4 2602.48   340.7 2603.59   462.5  2601.3   563.4 2604.51
   634.7 2603.13   672.8 2605.38   687.4 2604.91   716.1 2599.94   735.2 2602.54
   768.7 2604.02   840.4 2602.69   897.9 2603.73  913.362598.403   921.4 2595.85
   944.5 2595.73   964.7 2595.82   969.6 2598.26   979.1 2602.41   990.7 2603.59
  1129.4 2605.58  1817.5 2601.28  1839.9 2603.59  1895.8 2625.64  1918.1 2629.61
#Mann= 5 ,-1,0
       0     .05       0   840.4     .03       0  913.36    .045       0
   969.6     .03       0   990.7     .05       0
#XS Ineff= 2 , 0
          902.36    2604   980.6            2605
Permanent Ineff=
       F       F
Bank Sta=913.36,969.6
XS Rating Curve= 0 ,0
Exp/Cntr(USF)=0,0
Exp/Cntr=0.5,0.3

Type RM Length L Ch R = 1 ,7509    ,479,484.4,473.6
XS GIS Cut Line= 4
2302335.26148274 495094.148794552301888.66174949495695.590289447
2301481.44229101495919.7897665892301065.66152846496543.602944954
#Sta/Elev= 30
       0 2612.29    85.7 2609.64   221.7 2610.93   262.8  2604.1   293.1 2604.21
   321.7 2602.16   377.4 2603.81     499 2600.34   629.2 2602.64   711.2 2600.92
   749.7  2601.7   845.6 2600.85   859.3  2599.5  865.392596.087     873 2594.08
   927.8 2593.99     945  2594.7  949.772596.135   959.7 2602.15   964.3 2603.57
   984.6 2601.94  1060.2 2602.96  1201.7 2600.35    1307 2601.23  1843.7 2598.63
  1859.1 2599.63  1867.8 2602.03  1931.9 2625.33  1946.3 2626.84  1963.7 2626.53
#Mann= 4 ,-1,0
       0     .05       0  829.12     .03       0  865.39    .045       0
  949.77     .05       0
#XS Ineff= 2 , 0
                         1293.52         2605.48
Permanent Ineff=
       F       F
Bank Sta=865.39,949.77
XS Rating Curve= 0 ,0
Exp/Cntr=0.3,0.1

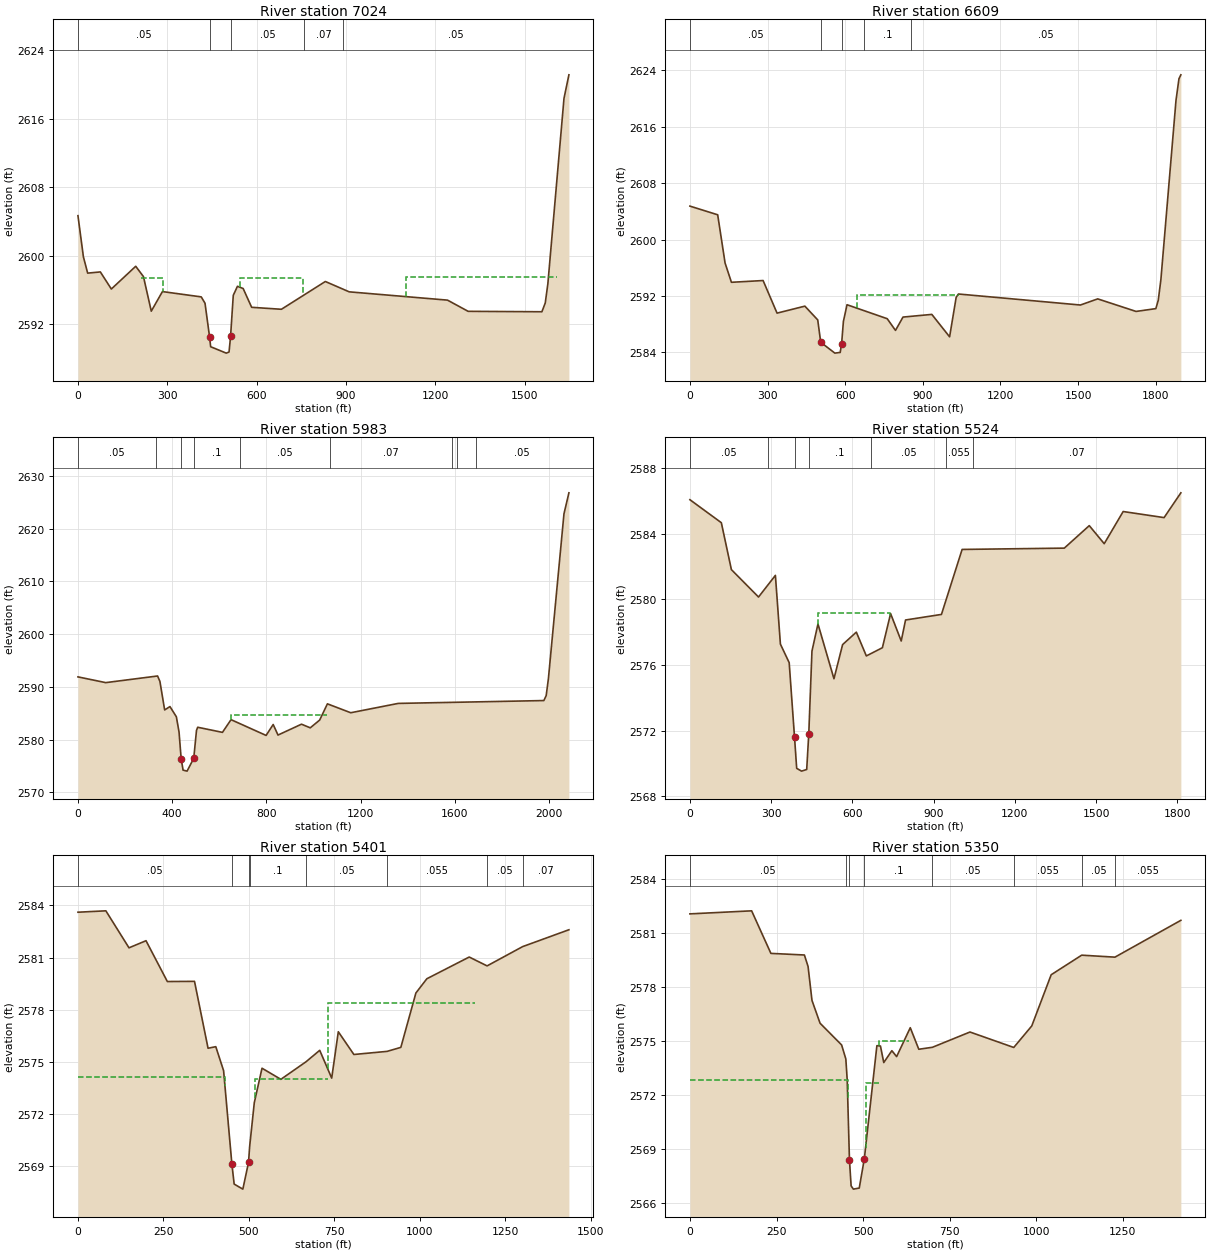
Type RM Length L Ch R = 1 ,7024    ,382.4,415.9,418.1
XS GIS Cut Line= 3
      2301967.63      495084.8082301284.86052905 495521.36670596
2300790.48306585496198.428127107
#Sta/Elev= 30
       0 2604.67    18.3 2599.85    32.6 2597.95    75.2 2598.09   112.1 2596.09
     194 2598.75     220 2597.54   246.2  2593.5   283.7 2595.79     414 2595.17
   426.7 2594.43  442.172590.443   445.6 2589.34     498 2588.59   507.4 2588.72
   512.5 2590.54   521.6 2595.35   535.6 2596.41   554.8 2596.15   583.3 2593.95
   683.3 2593.72   830.8 2596.97     911 2595.76  1241.1 2594.79  1310.4 2593.48
  1558.1 2593.43  1569.4 2594.46  1578.1  2596.7  1632.3  2618.4  1648.8 2621.15
#Mann= 5 ,-1,0
       0     .05       0  442.17    .045       0   512.5     .05       0
     760     .07       0  890.41     .05       0
#XS Ineff= 3 ,-1
  212.96  284.96 2597.41  544.56  756.51 2597.41  1101.3 1610.37 2597.51
Permanent Ineff=
       F       F       F
Bank Sta=442.17,512.5
XS Rating Curve= 0 ,0
Exp/Cntr=0.3,0.1

Type RM Length L Ch R = 1 ,6609    ,650,625.8,588.9
XS GIS Cut Line= 4
2301877.20483543494891.7369356982301600.06897967494949.321740033
2301200.49481268495054.3879909652300568.04190587496075.396649515
#Sta/Elev= 30
       0 2604.74   107.3 2603.51   135.9 2596.67   160.4 2593.94   282.8 2594.19
   336.7 2589.57   444.2 2590.56   493.9 2588.61   505.5 2585.44   560.1  2583.9
   580.7    2584   586.1 2585.18   593.1 2588.39   607.1 2590.76   762.4 2588.78
   794.4 2587.12   823.4 2589.01   934.8 2589.39  1003.5 2586.21  1028.9 2591.81
  1037.7 2592.28  1509.1 2590.72  1575.9 2591.59  1724.1 2589.81  1800.5 2590.21
  1809.9  2591.4    1820 2594.32  1878.4 2619.74  1889.9  2622.8  1897.2 2623.35
#Mann= 5 ,-1,0
       0     .05       0   505.5    .045       0   586.1     .05       0
  673.06      .1       0  856.21     .05       0
#XS Ineff= 1 ,-1
  646.76 1038.87 2592.19
Permanent Ineff=
       F
Bank Sta=505.5,586.1
XS Rating Curve= 0 ,0
Exp/Cntr=0.3,0.1

Type RM Length L Ch R = 1 ,5983    ,461.3,458.4,450.9
XS GIS Cut Line= 3
     2301355.165      494147.2422300718.31880797 494992.52600879
2300382.03283351495961.667422221
#Sta/Elev= 30
       0 2591.91     118 2590.82     338 2592.08     348 2591.04     368 2585.64
   390.5 2586.28   417.7 2584.35   429.1 2581.46437.99532576.431   446.2 2574.23
   463.2 2574.04491.49482576.464   503.2 2581.76   508.3 2582.36   613.4 2581.39
   649.8  2583.8   798.7 2580.81   828.8 2582.88   849.2 2580.88   948.9 2582.94
   986.1 2582.25  1026.1 2583.72    1059  2586.8    1158 2585.11  1359.6 2586.88
  1977.8 2587.42  1987.8 2588.37  1997.2 2591.59  2063.2 2622.82  2084.2 2626.81
#Mann= 9 ,-1,0
       0     .05       0     330      .1       0437.9953    .045       0
491.4948      .1       0     690     .05       0 1068.34     .07       0
 1588.34     .05       0 1608.34     .07       0 1688.34     .05       0
#XS Ineff= 1 ,-1
   650.7 1056.34 2584.77
Permanent Ineff=
       F
Bank Sta=437.9953,491.4948
XS Rating Curve= 0 ,0
Exp/Cntr=0.3,0.1

Type RM Length L Ch R = 1 ,5524    ,114.3,123.1,135.2
BEGIN DESCRIPTION:
structure xs 4
END DESCRIPTION:
XS GIS Cut Line= 4
 2300944.3380521494017.6059072352300739.78203221494193.362282606
2300491.46967253494621.4231414632300397.57427501495665.802690998
#Sta/Elev= 30
       0 2586.07     116 2584.67   153.2 2581.81   253.4 2580.14   315.7 2581.46
   334.2 2577.27   366.6 2576.14   386.3 2571.61   394.3  2569.7   412.4 2569.53
   431.3 2569.63     439 2571.81   450.7 2576.84   472.9  2578.5     532 2575.16
   563.9 2577.24   614.6    2578   651.6 2576.55   710.8 2577.05   741.2 2579.13
   780.4 2577.46   796.4 2578.74     929 2579.08  1005.3 2583.04  1382.7 2583.12
  1474.9 2584.49  1530.1 2583.39  1600.1 2585.35  1751.2 2584.98  1813.2 2586.49
#Mann= 7 ,-1,0
       0     .05       0  289.69      .1       0   386.3    .045       0
     439      .1       0  669.69     .05       0  944.56    .055       0
 1044.56     .07       0
#XS Ineff= 1 ,-1
  474.37  738.03 2579.18
Permanent Ineff=
       F
Bank Sta=386.3,439
XS Rating Curve= 0 ,0
Exp/Cntr=0.5,0.3

Type RM Length L Ch R = 1 ,5401    ,50.5,50.9,48.5
BEGIN DESCRIPTION:
structure xs 3
END DESCRIPTION:
XS GIS Cut Line= 4
2300894.07165813493924.8280314572300492.85633028494323.611751262
2300332.67108113494538.2460593762300363.12871356495140.252029459
#Sta/Elev= 30
       0 2583.61   81.63 2583.69  149.31 2581.56  199.09 2581.97  261.51 2579.62
  340.95 2579.63   380.6 2575.78  403.23 2575.87  426.06 2574.49  450.142569.145
  456.97 2567.96  482.42 2567.67     4992569.208  502.22 2570.11  515.89 2572.65
  538.45 2574.63  593.58 2573.99  667.14    2575  707.27 2575.66  742.33 2574.06
  761.65 2576.73  807.22 2575.42  904.53  2575.6  944.58 2575.83  988.64 2578.96
 1020.68 2579.78 1144.62 2581.03  1196.9 2580.52 1300.92 2581.63 1436.28  2582.6
#Mann= 8 ,-1,0
       0     .05       0  450.14    .045       0     499     .05       0
  502.22      .1       0  667.14     .05       0  904.53    .055       0
  1196.9     .05       0 1300.92     .07       0
#XS Ineff= 3 ,-1
       0  430.04 2574.11  519.04     731 2574.02     731 1161.92 2578.41
Permanent Ineff=
       F       F       F
Bank Sta=450.14,499
XS Rating Curve= 0 ,0
Exp/Cntr(USF)=0,0
Exp/Cntr=0.5,0.3

Type RM Length L Ch R = 1 ,5350    ,352.7,328.3,299.4
BEGIN DESCRIPTION:
structure xs 2
END DESCRIPTION:
XS GIS Cut Line= 4
2300853.95012535493895.6487348862300452.73479749494298.079866762
2300280.37986393494538.2460593762300293.51520007495091.424440922
#Sta/Elev= 30
       0 2582.08  178.14 2582.25  233.74 2579.88  330.44 2579.79  341.06 2579.15
  352.36 2577.26  375.69 2575.99  437.92 2574.78  450.08    2574  454.03 2572.84
  460.54 2568.37  465.32 2566.93  471.86 2566.75  488.83 2566.81  503.53 2568.45
  539.74 2574.74  550.05 2574.72  559.54  2573.8  582.95 2574.46  596.68 2574.13
  636.08 2575.74   660.7 2574.54  700.09 2574.65   808.4  2575.5  934.83 2574.64
  986.84 2575.84 1042.86 2578.69 1130.88 2579.78 1226.91 2579.67 1417.21 2581.72
#Mann= 8 ,-1,0
       0     .05       0  450.08      .1       0  460.54    .045       0
  503.53      .1       0  700.09     .05       0  934.83    .055       0
 1130.88     .05       0 1226.91    .055       0
#XS Ineff= 3 ,-1
     .35  455.472572.852  506.96  544.412572.666  544.41  633.76 2575.02
Permanent Ineff=
       F       F       F
Bank Sta=460.54,503.53
XS Rating Curve= 0 ,0
Exp/Cntr(USF)=0,0
Exp/Cntr=0.5,0.3