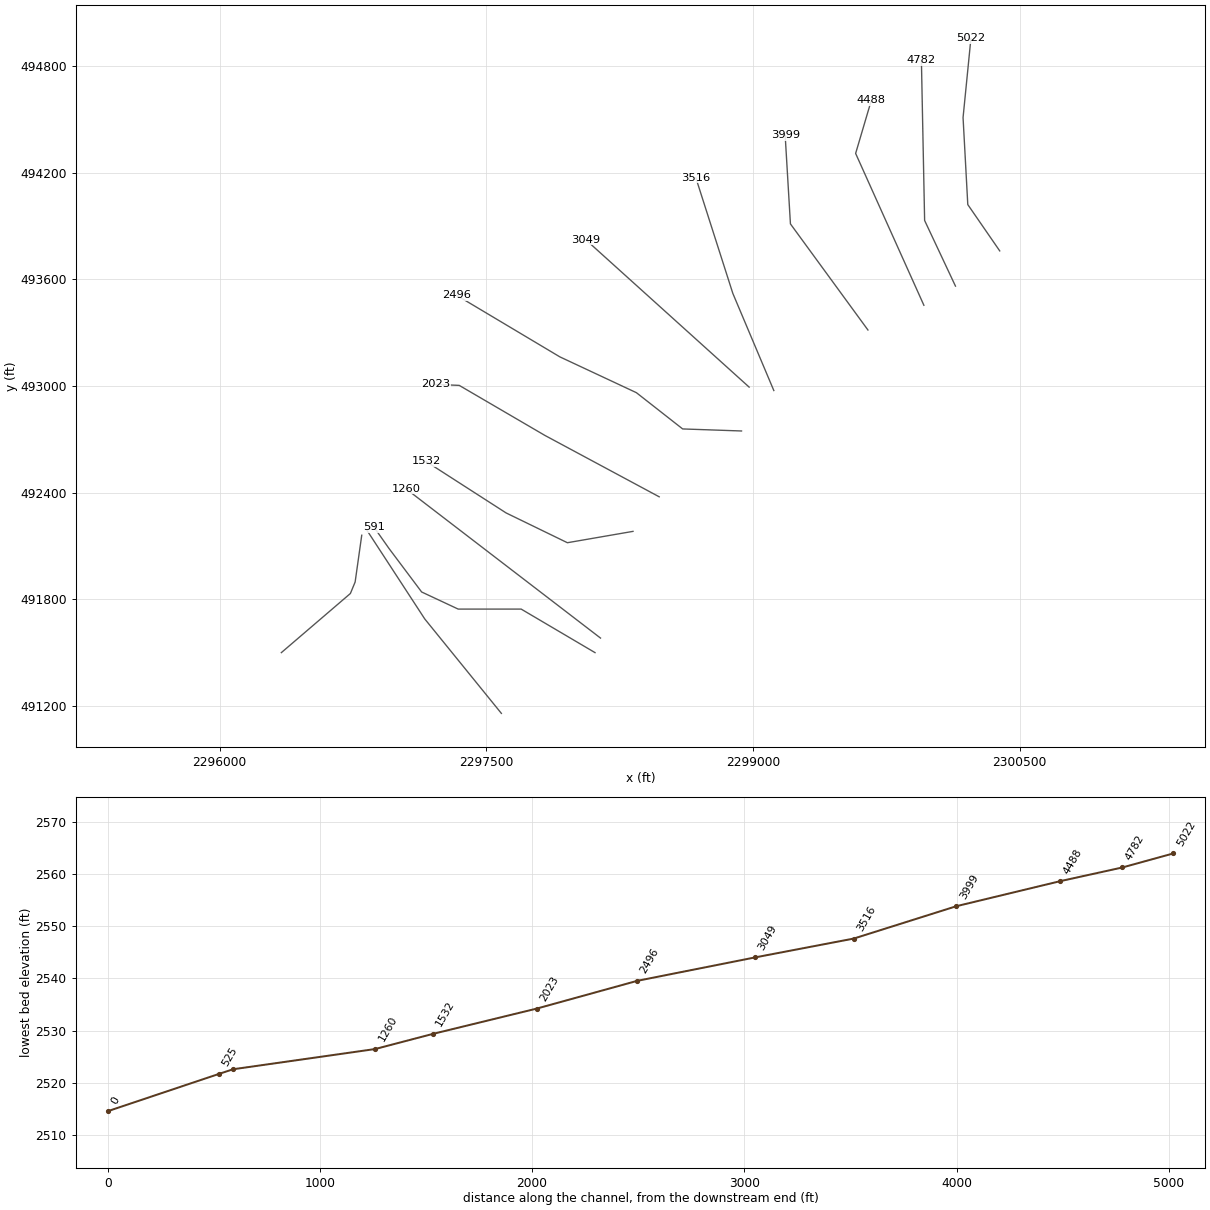
HEC-RAS study GALFRDRN.prj: GALFRDRN

--- GALFRDRN.g01 (geometry) --- (continued)

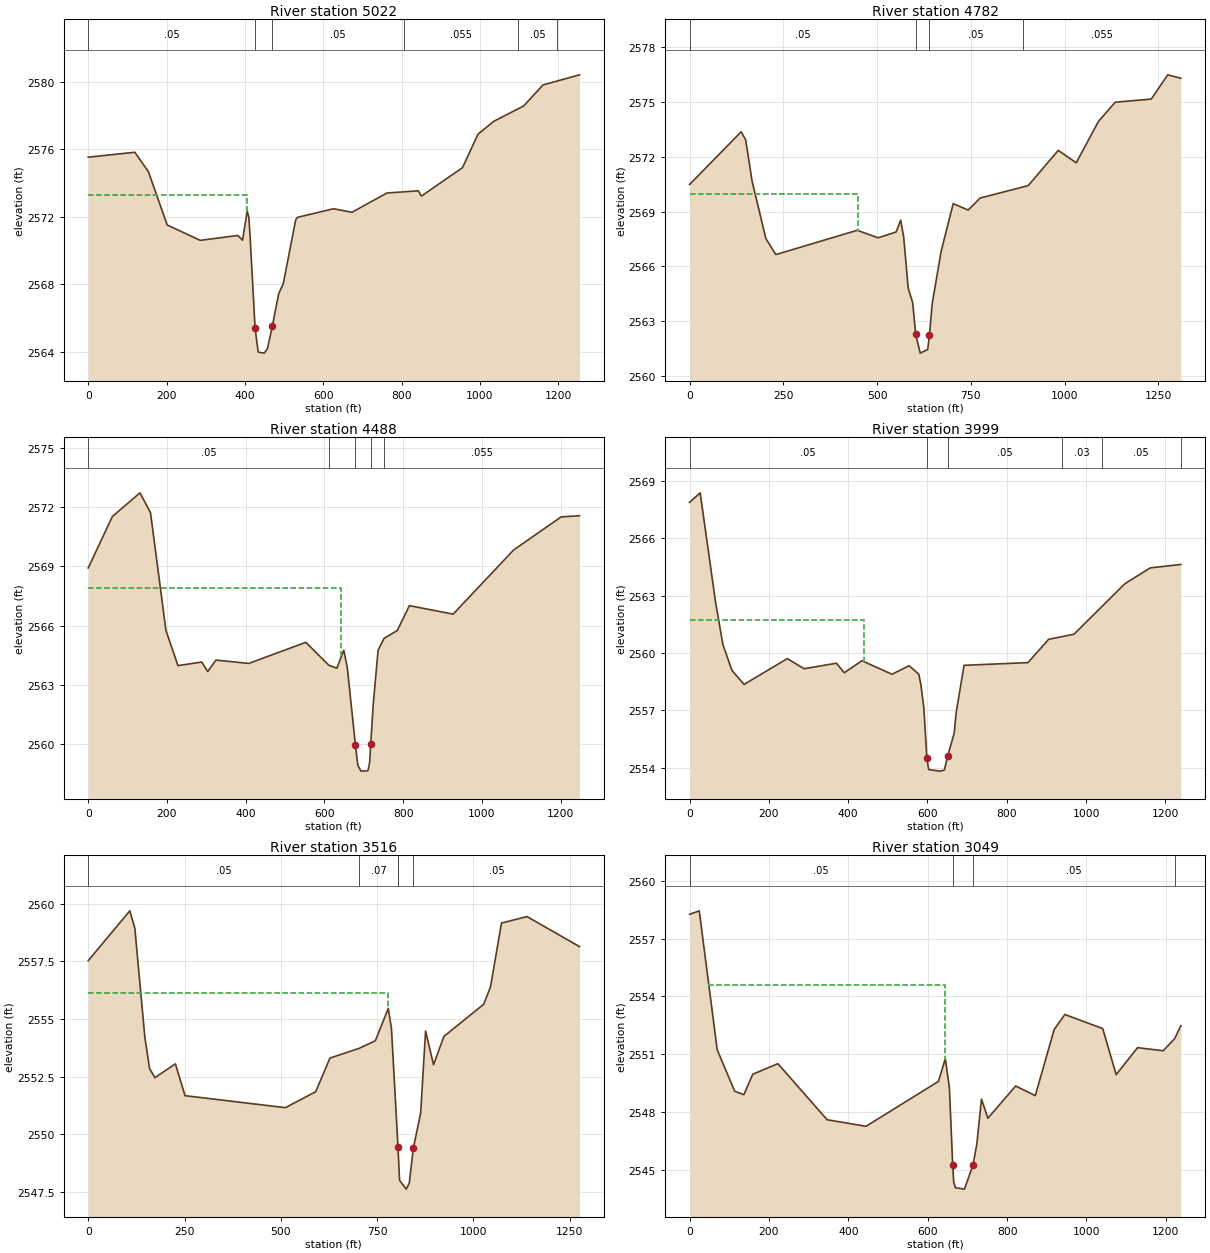
Type RM Length L Ch R = 1 ,5022    ,241.3,240.3,238.9
XS GIS Cut Line= 4
2300387.99915126493759.2182213092300208.35818871494019.660745313
2300181.76714941494509.3196101072300226.05957527494954.875572257
#Sta/Elev= 30
       0 2575.53     119 2575.82   153.7 2574.67   201.6 2571.52     286 2570.61
     382  2570.9     394 2570.62     406 2572.34     410 2571.99     413 2570.98
   426.1  2565.4   434.1    2564   449.1 2563.94   457.6  2564.2     470 2565.52
   486.2 2567.44   498.2 2568.06   529.6 2571.81   534.2 2571.97   626.4 2572.48
   673.6 2572.27   762.6 2573.41   842.8 2573.54   850.8 2573.23   955.7 2574.91
   995.3 2576.89  1035.5 2577.65  1112.1 2578.56    1161  2579.8  1254.5  2580.4
#Mann= 6 ,-1,0
       0     .05       0   426.1    .045       0     470     .05       0
  806.39    .055       0 1096.77     .05       0 1196.77    .055       0
#XS Ineff= 2 , 0
          404.62 2573.28
Permanent Ineff=
       F       F
Bank Sta=426.1,470
XS Rating Curve= 0 ,0
Exp/Cntr=0.3,0.1

Type RM Length L Ch R = 1 ,4782    ,278.8,293.5,306.1
XS GIS Cut Line= 3
2300139.05260023493561.0626999992299965.55550613493930.248376982
2299947.39883349494832.029784696
#Sta/Elev= 30
       0 2570.49   137.6 2573.38   149.6 2572.94   166.6 2570.68   203.4 2567.53
     230 2566.65   446.9 2567.98   502.9 2567.57   550.9 2567.89   562.9 2568.54
   570.9 2567.61   582.9 2564.82   594.9 2564.01   602.9 2562.29   614.9 2561.25
   634.9 2561.45   639.6 2562.23   646.9 2563.96   670.8 2566.83   702.9 2569.44
   742.9 2569.09   774.9 2569.75     903 2570.43     983 2572.36    1031 2571.68
  1090.6 2573.96    1135    2575    1231 2575.17    1275  2576.5  1309.9 2576.31
#Mann= 4 ,-1,0
       0     .05       0   602.9    .045       0   639.6     .05       0
  887.92    .055       0
#XS Ineff= 2 , 0
          448.79 2569.97
Permanent Ineff=
       F       F
Bank Sta=602.9,639.6
XS Rating Curve= 0 ,0
Exp/Cntr(USF)=0,0
Exp/Cntr=0.3,0.1

Type RM Length L Ch R = 1 ,4488    ,482,489.7,496.2
XS GIS Cut Line= 3
2299961.39271693493453.2462162352299577.44349574494307.386546394
2299665.62101138494605.733976137
#Sta/Elev= 30
       0 2568.92    61.3 2571.53   131.5 2572.73   158.2 2571.72   197.3 2565.76
   227.8 2563.97   288.3 2564.15   303.4 2563.67   324.5 2564.25   407.8 2564.08
   552.5 2565.15   610.9 2563.99   631.4 2563.84     649 2564.75   657.8 2563.89
   678.6 2559.93   684.6 2558.92   692.8 2558.62   710.4 2558.64   714.8 2559.08
  717.32 2559.98   723.5 2561.94   736.1 2564.75   751.2 2565.35   784.9 2565.75
   815.6 2567.01   926.7 2566.58  1080.2 2569.83  1200.9 2571.51  1247.6 2571.57
#Mann= 5 ,-1,0
       0     .05       0   610.9     .03       0   678.6    .045       0
  717.32     .03       0   751.2    .055       0
#XS Ineff= 2 , 0
          640.86 2567.88
Permanent Ineff=
       F       F
Bank Sta=678.6,717.32
XS Rating Curve= 0 ,0
Exp/Cntr=0.3,0.1

Type RM Length L Ch R = 1 ,3999    ,494.7,482.6,465.4
XS GIS Cut Line= 3
  2299646.668999493314.1606680062299210.69452536493911.050577806
2299180.99273857 494410.14723344
#Sta/Elev= 30
       0 2567.89    26.8 2568.39    65.3  2562.7    84.1 2560.44     107 2559.09
   137.5 2558.36   246.5 2559.71   289.1 2559.18   370.4 2559.47   390.1 2558.97
   434.7  2559.6   510.6 2558.89   553.6 2559.34   578.3 2558.89   583.3 2558.36
   590.8 2557.16598.50012554.508   603.1  2553.9   632.8 2553.82   642.7 2553.88
650.79972554.595   667.5 2555.81   672.4 2556.88   692.3 2559.36   853.5  2559.5
   905.6 2560.72   969.7 2560.99  1097.9 2563.63    1162 2564.46  1239.1 2564.64
#Mann= 6 ,-1,0
       0     .05       0598.5001    .045       0650.7997     .05       0
  939.16     .03       0 1039.16     .05       0 1239.14    .055       0
#XS Ineff= 2 , 0
           440.9 2561.72
Permanent Ineff=
       F       F
Bank Sta=598.5001,650.7997
XS Rating Curve= 0 ,0
Exp/Cntr=0.3,0.1

Type RM Length L Ch R = 1 ,3516    ,448.8,467.3,487
XS GIS Cut Line= 3
2299117.24717526492973.6578653352298886.59660495493520.145307003
      2298678.65      494170.154
#Sta/Elev= 30
       0 2557.53     108 2559.69     121 2558.94   147.1  2554.2   159.2 2552.86
   173.1 2552.46   226.4 2553.06   251.3 2551.68   511.8 2551.16   590.6 2551.85
   627.7 2553.31   703.4 2553.73   745.5 2554.06     779 2555.46   787.4 2554.58
   804.2 2549.48  804.212549.476   808.4 2548.01   825.7 2547.63   833.6 2547.89
  844.112549.404   863.2 2550.93   875.9 2554.48   896.6 2553.02   923.6 2554.25
  1026.8 2555.64  1044.6  2556.4    1073 2559.16  1139.3 2559.44  1275.6 2558.14
#Mann= 5 ,-1,0
       0     .05       0   703.4     .07       0   804.2     .05       0
  804.21    .045       0  844.11     .05       0
#XS Ineff= 2 , 0
          778.49 2556.14
Permanent Ineff=
       F       F
Bank Sta=804.21,844.11
XS Rating Curve= 0 ,0
Exp/Cntr=0.3,0.1

Type RM Length L Ch R = 1 ,3049    ,528.7,553.1,557.8
XS GIS Cut Line= 2
2298978.27103632492993.0134290632298059.18998638493822.254704879
#Sta/Elev= 30
       0 2558.26    24.4 2558.44    69.6 2551.23   113.7 2549.08   136.8  2548.9
   159.1 2549.96   222.5 2550.51   346.6  2547.6   444.6 2547.26   627.2 2549.59
   644.5 2550.77   654.7 2549.25     663 2545.26   665.5 2544.37     670 2544.07
   692.6    2544     714 2545.24   723.8 2546.33   735.5 2548.67   751.7 2547.68
   821.7 2549.35   871.1 2548.85   918.7 2552.28   945.6 2553.06    1041 2552.33
  1074.9 2549.94  1128.8 2551.34  1193.5 2551.18  1222.3 2551.81  1237.9 2552.48
#Mann= 4 ,-1,0
       0     .05       0     663    .045       0     714     .05       0
  1222.3      .1       0
#XS Ineff= 1 ,-1
   46.54  643.532554.604
Permanent Ineff=
       F
Bank Sta=663,714
XS Rating Curve= 0 ,0
Exp/Cntr=0.3,0.1

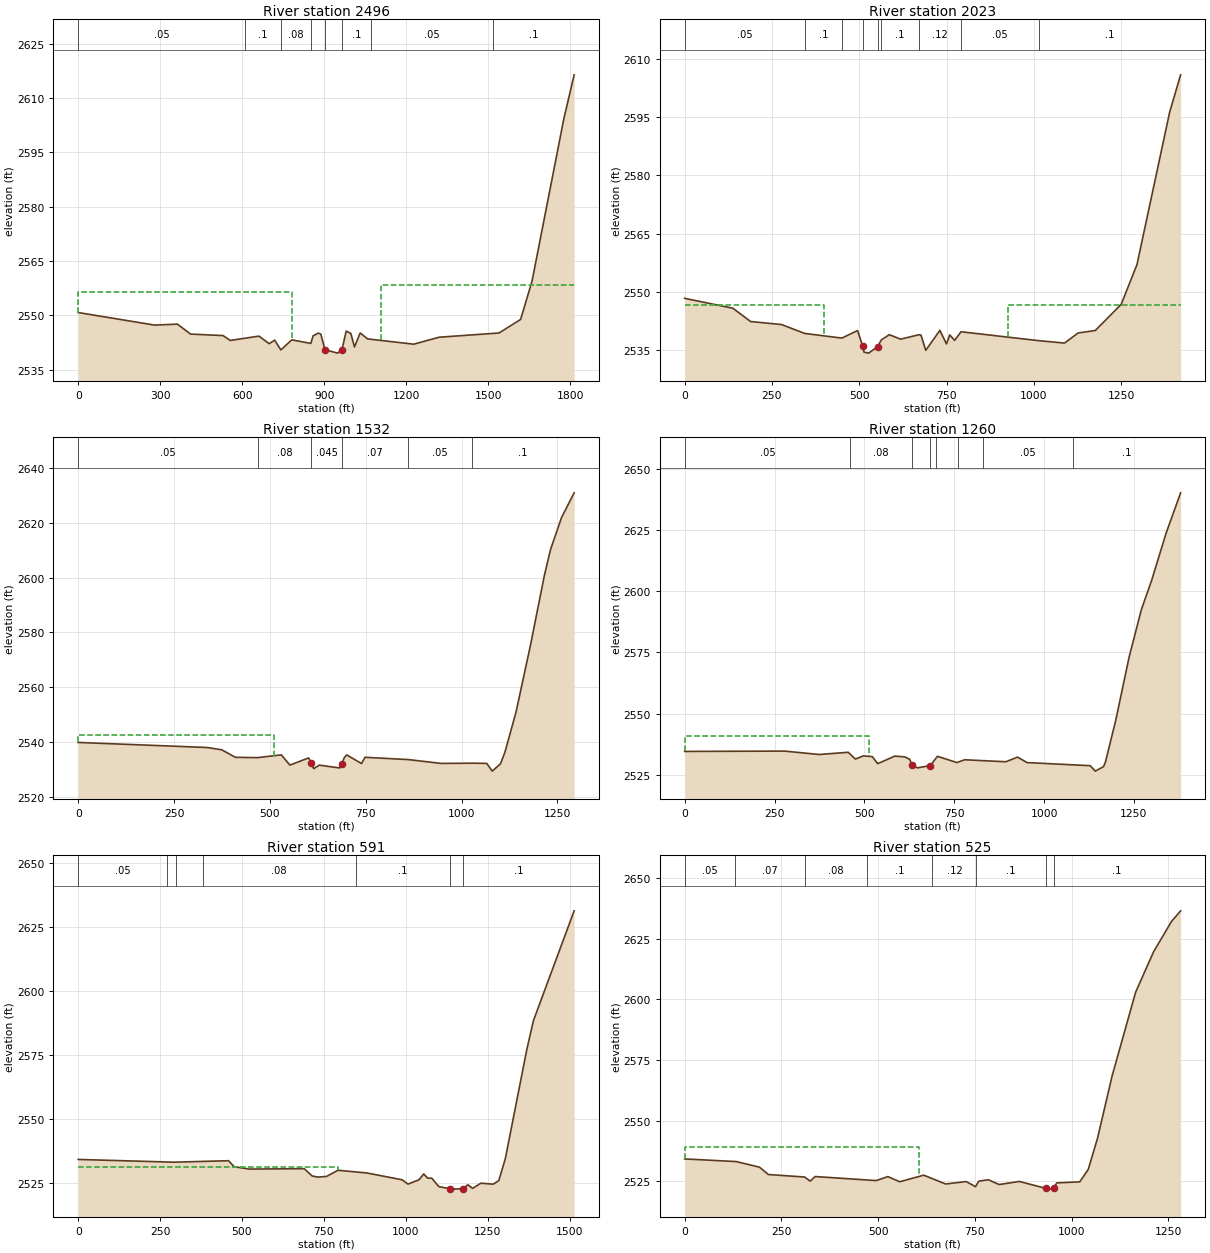
Type RM Length L Ch R = 1 ,2496    ,464.2,473,466.2
XS GIS Cut Line= 5
2298935.57375985492746.1395576842298604.38363399492757.631197234
2298344.21348495492961.561833219 2297913.6062773493163.055507881
2297331.97393921493509.945298644
#Sta/Elev= 30
       0 2550.74   279.6 2547.27   363.1 2547.54     411 2544.79   529.9 2544.38
   556.3 2543.03   661.3 2544.23   698.8 2542.14   718.9 2543.11   741.5 2540.41
   781.2 2543.19   851.2 2542.22   859.3  2544.3   878.4 2545.06   887.6 2544.79
903.06022540.475   949.1 2539.53965.14042540.525   980.6 2545.61   997.6 2544.96
  1010.9 2541.24  1031.7  2545.1  1058.8 2543.46  1227.7    2542  1320.8 2543.93
  1539.7 2545.09  1618.8 2548.84  1660.7 2559.47  1777.1 2604.35  1814.6  2616.4
#Mann= 8 ,-1,0
       0     .05       0  611.39      .1       0  741.96     .08       0
  851.96     .07       0903.0602    .045       0965.1404      .1       0
 1071.96     .05       0 1517.38      .1       0
#XS Ineff= 2 , 0
          783.41  2556.4 1109.06         2558.24
Permanent Ineff=
       F       F
Bank Sta=903.0602,965.1404
XS Rating Curve= 0 ,0
Exp/Cntr=0.3,0.1

Type RM Length L Ch R = 1 ,2023    ,491.4,490.6,502.5
XS GIS Cut Line= 4
 2298472.4346311 492375.848995462297829.23069125  492721.2836782
2297347.44971516493002.6502182842297215.25104819493008.136346781
#Sta/Elev= 30
       0 2548.33   138.1 2545.78   188.8 2542.36   277.3 2541.58   343.8 2539.29
   450.2 2538.09   495.2 2540.04   509.32536.133   513.4 2534.49     527 2534.22
   552.3 2535.88   563.3 2537.62     586 2538.97   618.5 2537.81   670.7 2538.96
   676.8 2538.86   690.4 2534.94   730.8 2540.08   749.8  2536.6   759.1 2538.91
     773  2537.5   791.5 2539.72  1013.9 2537.43    1088 2536.81  1126.5  2539.4
    1176 2540.05  1250.1 2546.78  1295.3    2557    1389  2596.3  1420.3 2605.88
#Mann= 9 ,-1,0
       0     .05       0   343.8      .1       0   450.2     .08       0
   509.3    .045       0   552.3     .08       0   563.3      .1       0
   670.7     .12       0   791.5     .05       0  1013.9      .1       0
#XS Ineff= 2 , 0
          400.23 2546.58  926.57         2546.62
Permanent Ineff=
       F       F
Bank Sta=509.3,552.3
XS Rating Curve= 0 ,0
Exp/Cntr=0.3,0.1

Type RM Length L Ch R = 1 ,1532    ,277.9,272.1,264.7
XS GIS Cut Line= 4
 2298325.0871101492181.4252531182297955.98117933492117.551090253
 2297611.2382815492285.0950919382297160.47842452492575.079792278
#Sta/Elev= 30
       0 2539.82   336.7 2537.98   374.6 2537.13   410.1  2534.4   467.8 2534.28
     530 2535.29   552.3 2531.56   601.2 2534.18  607.91 2532.18   614.5 2530.24
   628.6 2531.55   682.4 2530.52   688.4 2532.13     694 2534.23   700.4 2535.28
   739.1 2532.13   748.3 2534.41   861.2 2533.57     947 2532.17  1027.9 2532.25
  1065.9 2532.18  1080.2 2529.36  1101.7 2532.02  1113.3 2536.27  1142.2 2550.87
  1180.1  2575.4  1216.4 2600.86  1232.4 2610.25  1260.9 2621.85  1293.9  2630.9
#Mann= 6 ,-1,0
       0     .05       0   467.8     .08       0  607.91    .045       0
   688.4     .07       0   861.2     .05       0  1027.9      .1       0
#XS Ineff= 2 , 0
          510.31 2542.46
Permanent Ineff=
       F       F
Bank Sta=607.91,688.4
XS Rating Curve= 0 ,0
Exp/Cntr=0.3,0.1

Type RM Length L Ch R = 1 ,1260    ,654.5,669,636.4
XS GIS Cut Line= 2
2298142.26845097491581.1945990022297047.52346503492421.347727748
#Sta/Elev= 30
       0 2534.52   278.2 2534.65   374.5 2533.26   455.1 2534.17     475 2531.39
   496.8 2532.69     522 2532.39   537.1 2529.51   584.7  2532.6   612.7 2532.29
   626.2 2531.28   632.9 2528.78     648  2527.8   683.6 2528.76   703.3 2532.52
   757.5 2529.97   779.1 2531.11   893.5 2530.29   926.4 2532.19   952.6 2529.95
  1128.3 2528.69  1142.6 2526.46  1165.4 2528.29  1171.1 2530.31  1199.7  2547.4
  1236.7 2573.11    1271 2592.62  1299.5 2604.55  1339.4 2623.69    1380  2640.3
#Mann= 8 ,-1,0
       0     .05       0     460     .08       0   632.9    .045       0
   683.6     .08       0     700      .1       0     760     .07       0
     830     .05       0    1080      .1       0
#XS Ineff= 2 , 0
          512.68 2540.75
Permanent Ineff=
       F       F
Bank Sta=632.9,683.6
XS Rating Curve= 0 ,0
Exp/Cntr(USF)=0,0
Exp/Cntr=0.3,0.1

Type RM Length L Ch R = 1 ,591     ,74.9,65.7,60.8
XS GIS Cut Line= 6
2298111.47847627491499.2757946112297695.95943734491744.213333351
2297341.67478309491744.2133333512297136.10220593491840.438794999
2296952.39905188492085.3763337392296869.29524409492203.471218488
#Sta/Elev= 30
       0 2534.18   291.7 2533.11   458.9 2533.68   476.4 2531.33   523.1 2530.42
   690.1 2530.58   714.1 2527.75   731.1 2527.29   758.1 2527.54   793.2 2529.95
   880.6 2528.91   988.9 2526.24  1006.9 2524.55    1040 2526.21  1055.1 2528.52
  1066.9 2526.87  1079.5 2526.87  1101.2 2523.55  1135.5 2522.75  1144.5 2522.59
 1174.97 2522.76  1189.8 2524.28  1204.1 2522.88  1229.5 2524.91  1266.9 2524.52
  1284.1 2525.91  1304.1 2534.49  1369.8 2577.17  1389.9 2588.38  1514.2 2631.25
#Mann= 7 ,-1,0
       0     .05       0     270     .07       0     300     .05       0
     380     .08       0  846.62      .1       0  1135.5    .045       0
 1174.97      .1       0
#XS Ineff= 2 , 0
          793.39 2531.05
Permanent Ineff=
       F       F
Bank Sta=1135.5,1174.97
XS Rating Curve= 0 ,0
Exp/Cntr(USF)=0,0
Exp/Cntr=0.3,0.1

Type RM Length L Ch R = 1 ,525     ,567.3,525.3,467.1
XS GIS Cut Line= 3
2297584.62944145491157.5714809352297153.76395346491688.544954605
2296827.34190806492189.115507383
#Sta/Elev= 30
       0 2534.16   133.4 2533.07   193.4 2530.75   216.2 2527.73     310 2526.71
   324.2 2525.01   337.2  2526.9   494.8 2525.23   524.9 2526.88   555.8 2524.74
   617.6 2527.47   674.3 2523.83   727.5 2524.83   751.4 2522.73   759.9    2525
   784.8 2525.56   812.6  2523.6   864.6 2524.88   932.9 2522.03   942.4 2521.71
   953.2  2522.2   961.5 2524.29  1020.7  2524.7  1042.7 2529.83  1066.6  2542.6
  1104.5 2568.46  1165.2 2602.92  1211.5 2619.54  1257.7 2632.05  1281.4 2636.46
#Mann= 8 ,-1,0
       0     .05       0     130     .07       0     310     .08       0
     470      .1       0     640     .12       0   753.8      .1       0
   932.9    .045       0   953.2      .1       0
#XS Ineff= 2 , 0
          606.45 2539.19
Permanent Ineff=
       F       F
Bank Sta=932.9,953.2
XS Rating Curve= 0 ,0
Exp/Cntr=0.3,0.1

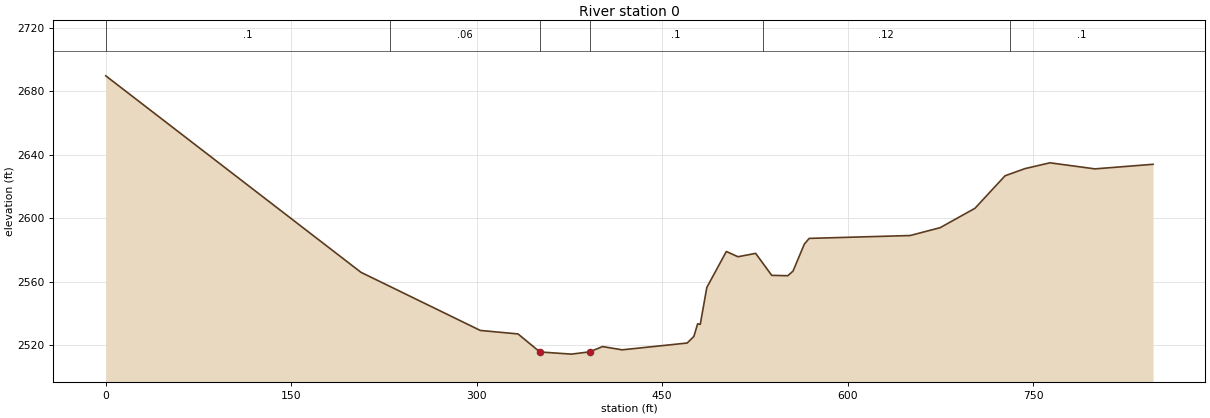
Type RM Length L Ch R = 1 ,0       ,,,
XS GIS Cut Line= 4
2296346.99048354491499.3293536552296735.33771585491831.962494566
 2296761.9989848  491896.51639342296799.15611267 492159.69261564
#Sta/Elev= 30
       0 2689.73   206.4 2566.04   302.9 2529.46   333.4 2527.26   351.1 2515.91
   376.6 2514.55   391.3 2515.99   401.8 2519.31   417.6 2517.25   470.2 2521.54
   475.6 2525.66   478.7 2533.64   480.8 2533.28   486.1 2556.51   501.9 2579.16
   511.3 2575.85   525.6 2577.97   538.6 2564.13   551.6 2563.91   555.8 2566.79
     565 2583.84   568.9  2587.4   650.5  2589.2   674.8 2594.14     703 2606.36
   727.3 2626.81   743.4 2631.32   763.6 2634.98     800 2631.16     847 2634.04
#Mann= 6 ,-1,0
       0      .1       0     230     .06       0   351.1    .045       0
   391.3      .1       0  531.33     .12       0  731.17      .1       0
Bank Sta=351.1,391.3
XS Rating Curve= 0 ,0
Exp/Cntr=0.3,0.1
LCMann Table=0

Chan Stop Cuts=-1
Use User Specified Reach Order=0
Composite Channel Slope=5